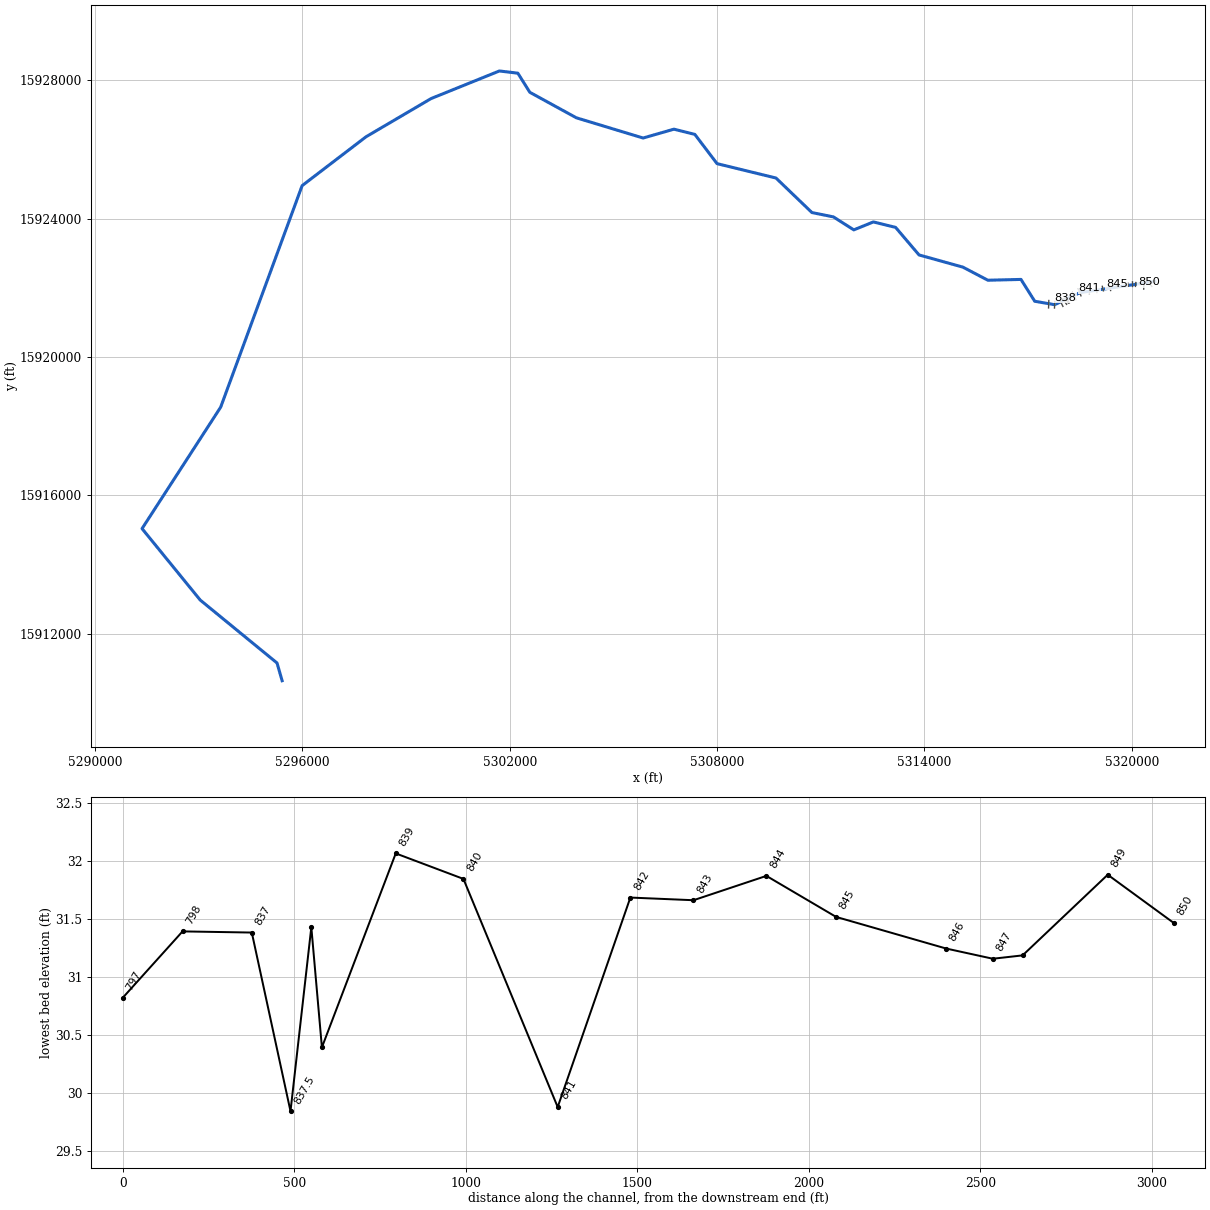
--- ozz_def.prj (project) ---

Proj Title=ozzeri
Current Plan=p07
Default Exp/Contr=.3,.1
English Units
Geom File=g04
Geom File=g03
Geom File=g01
Unsteady File=u01
Unsteady File=u04
Plan File=p06
Plan File=p05
Plan File=p01
Plan File=p04
Plan File=p07
Y Axis Title=Elevation
X Axis Title(PF)=Main Channel Distance
X Axis Title(XS)=Station
BEGIN DESCRIPTION:
END DESCRIPTION:
DSS Start Date=01/20/2000
DSS Start Time=0000
DSS End Date=01/20/2000
DSS End Time=2400
DSS File=dss
DSS Export Rating Curves= 0
DSS Export Rating Curve Sorted= 0
DSS Export Volume Flow Curves= 0
DXF OffsetX= 0
DXF OffsetY= 0
DXF ScaleX= 1
DXF ScaleY= 10

--- ozz_def.p07 (plan) ---

Plan Title=Plan 07
Version=Version 3.0.1  Mar 2001
Short Identifier=Plan 07
Simulation Date=01/20/2000,0000,01/20/2000,2400
Geom File=g04
Flow File=u04
Subcritical Flow
K Sum by GR= 0
Std Step Tol= 0.01
Critical Tol= 0.01
Num of Std Step Trials= 20
Max Error Tol= 0.3
Flow Tol Ratio= 0.001
Split Flow NTrial= 30
Split Flow Tol= 0.02
Split Flow Ratio= 0.02
Log Output Level= 0
Friction Slope Method= 1
Unsteady Friction Slope Method= 2
Parabolic Critical Depth
Global Vel Dist= 0 , 0 , 0
Global Log Level= 0
CheckData=True
Encroach Param=-1 ,0,0, 0
Computation Interval=1MIN
Output Interval=1HOUR
Run HTab= 1
Run UNet= 1
Run PostProcess= 1
UNET Theta= 1
UNET ZTol= 0.0656
UNET ZSATol= 0.3281
UNET MxIter= 20
UNET MaxInSteps= 20
UNET DtIC= 0
UNET DtMin= 0
UNET MaxCRTS= 20
UNET WFStab= 2
UNET SFStab= 1
UNET WFX= 1
UNET SFX= 1
UNET Convert EG Bridges=-1
UNET Use Existing IB Tables=-1
Instantaneous Interval=1HOUR
DSS File=dss
Write IC File= 1
Write Velocity= 1
Write Detailed= 1
Stage Flow Hydrograph=OZZERI          ,tronco_1        ,850
Stage Flow Hydrograph=OZZERI          ,tronco_1        ,849
Stage Flow Hydrograph=OZZERI          ,tronco_1        ,848
Stage Flow Hydrograph=OZZERI          ,tronco_1        ,847
Stage Flow Hydrograph=OZZERI          ,tronco_1        ,846
Stage Flow Hydrograph=OZZERI          ,tronco_1        ,845
Stage Flow Hydrograph=OZZERI          ,tronco_1        ,844
Stage Flow Hydrograph=OZZERI          ,tronco_1        ,843
Stage Flow Hydrograph=OZZERI          ,tronco_1        ,842
Stage Flow Hydrograph=OZZERI          ,tronco_1        ,841
Stage Flow Hydrograph=OZZERI          ,tronco_1        ,840
Stage Flow Hydrograph=OZZERI          ,tronco_1        ,839
Stage Flow Hydrograph=OZZERI          ,tronco_1        ,838.5
Stage Flow Hydrograph=OZZERI          ,tronco_1        ,838
Stage Flow Hydrograph=OZZERI          ,tronco_1        ,837.5
Stage Flow Hydrograph=OZZERI          ,tronco_1        ,837
Stage Flow Hydrograph=OZZERI          ,tronco_1        ,798
Stage Flow Hydrograph=OZZERI          ,tronco_1        ,797
Stage Flow Hydrograph=OZZERI          ,tronco_1        ,796
Stage Flow Hydrograph=OZZERI          ,tronco_1        ,795
Stage Flow Hydrograph=OZZERI          ,tronco_1        ,794
Stage Flow Hydrograph=OZZERI          ,tronco_1        ,793
Stage Flow Hydrograph=OZZERI          ,tronco_1        ,792
Stage Flow Hydrograph=OZZERI          ,tronco_1        ,791
Stage Flow Hydrograph=OZZERI          ,tronco_1        ,790
Stage Flow Hydrograph=OZZERI          ,tronco_1        ,788
Stage Flow Hydrograph=OZZERI          ,tronco_1        ,786
Stage Flow Hydrograph=OZZERI          ,tronco_1        ,785
Stage Flow Hydrograph=OZZERI          ,tronco_1        ,784
Stage Flow Hydrograph=OZZERI          ,tronco_1        ,783
Stage Flow Hydrograph=OZZERI          ,tronco_1        ,782
Stage Flow Hydrograph=OZZERI          ,tronco_1        ,781
Stage Flow Hydrograph=OZZERI          ,tronco_1        ,780
Stage Flow Hydrograph=OZZERI          ,tronco_1        ,779.3
Stage Flow Hydrograph=OZZERI          ,tronco_1        ,779
Stage Flow Hydrograph=OZZERI          ,tronco_1        ,778.5
Stage Flow Hydrograph=OZZERI          ,tronco_1        ,778
Stage Flow Hydrograph=OZZERI          ,tronco_1        ,777
Stage Flow Hydrograph=OZZERI          ,tronco_1        ,776
Stage Flow Hydrograph=OZZERI          ,tronco_1        ,775
Stage Flow Hydrograph=OZZERI          ,tronco_1        ,773
Stage Flow Hydrograph=OZZERI          ,tronco_1        ,772.5
Stage Flow Hydrograph=OZZERI          ,tronco_1        ,772
Stage Flow Hydrograph=OZZERI          ,tronco_1        ,771.3
Stage Flow Hydrograph=OZZERI          ,tronco_1        ,771
Stage Flow Hydrograph=OZZERI          ,tronco_1        ,770
Stage Flow Hydrograph=OZZERI          ,tronco_1        ,769
Stage Flow Hydrograph=OZZERI          ,tronco_1        ,768
Stage Flow Hydrograph=OZZERI          ,tronco_1        ,767
Stage Flow Hydrograph=OZZERI          ,tronco_1        ,766
Stage Flow Hydrograph=OZZERI          ,tronco_1        ,765
Stage Flow Hydrograph=OZZERI          ,tronco_1        ,764
Stage Flow Hydrograph=OZZERI          ,tronco_1        ,763
Stage Flow Hydrograph=OZZERI          ,tronco_1        ,762
Stage Flow Hydrograph=OZZERI          ,tronco_1        ,761
Stage Flow Hydrograph=OZZERI          ,tronco_1        ,760
Stage Flow Hydrograph=OZZERI          ,tronco_1        ,693
Stage Flow Hydrograph=OZZERI          ,tronco_1        ,692
Stage Flow Hydrograph=OZZERI          ,tronco_1        ,691
Stage Flow Hydrograph=OZZERI          ,tronco_1        ,690
Stage Flow Hydrograph=OZZERI          ,tronco_1        ,689
Stage Flow Hydrograph=OZZERI          ,tronco_1        ,688
Stage Flow Hydrograph=OZZERI          ,tronco_1        ,687
Stage Flow Hydrograph=OZZERI          ,tronco_1        ,686
Stage Flow Hydrograph=OZZERI          ,tronco_1        ,685
Stage Flow Hydrograph=OZZERI          ,tronco_1        ,684
Stage Flow Hydrograph=OZZERI          ,tronco_1        ,683.2
Stage Flow Hydrograph=OZZERI          ,tronco_1        ,683
Stage Flow Hydrograph=OZZERI          ,tronco_1        ,682
Stage Flow Hydrograph=OZZERI          ,tronco_1        ,681
Stage Flow Hydrograph=OZZERI          ,tronco_1        ,680
Stage Flow Hydrograph=OZZERI          ,tronco_1        ,679
Stage Flow Hydrograph=OZZERI          ,tronco_1        ,678
Stage Flow Hydrograph=OZZERI          ,tronco_1        ,677
Stage Flow Hydrograph=OZZERI          ,tronco_1        ,676
Stage Flow Hydrograph=OZZERI          ,tronco_1        ,675
Stage Flow Hydrograph=OZZERI          ,tronco_1        ,674
Stage Flow Hydrograph=OZZERI          ,tronco_1        ,673
Stage Flow Hydrograph=OZZERI          ,tronco_1        ,672
Stage Flow Hydrograph=OZZERI          ,tronco_1        ,671.5
Stage Flow Hydrograph=OZZERI          ,tronco_1        ,671.2
Stage Flow Hydrograph=OZZERI          ,tronco_1        ,671
Stage Flow Hydrograph=OZZERI          ,tronco_1        ,670
Stage Flow Hydrograph=OZZERI          ,tronco_1        ,669
Stage Flow Hydrograph=OZZERI          ,tronco_1        ,668
Stage Flow Hydrograph=OZZERI          ,tronco_1        ,667
Stage Flow Hydrograph=OZZERI          ,tronco_1        ,666
Stage Flow Hydrograph=OZZERI          ,tronco_1        ,665
Stage Flow Hydrograph=OZZERI          ,tronco_1        ,664
Stage Flow Hydrograph=OZZERI          ,tronco_1        ,663
Stage Flow Hydrograph=OZZERI          ,tronco_1        ,662
Stage Flow Hydrograph=OZZERI          ,tronco_1        ,661
Stage Flow Hydrograph=OZZERI          ,tronco_1        ,660
Stage Flow Hydrograph=OZZERI          ,tronco_1        ,659
Stage Flow Hydrograph=OZZERI          ,tronco_1        ,658
Stage Flow Hydrograph=OZZERI          ,tronco_1        ,657
Stage Flow Hydrograph=OZZERI          ,tronco_1        ,656
Stage Flow Hydrograph=OZZERI          ,tronco_1        ,655
Stage Flow Hydrograph=OZZERI          ,tronco_1        ,654
Stage Flow Hydrograph=OZZERI          ,tronco_1        ,653
Stage Flow Hydrograph=OZZERI          ,tronco_1        ,652
Stage Flow Hydrograph=OZZERI          ,tronco_1        ,651
Stage Flow Hydrograph=OZZERI          ,tronco_1        ,650
Stage Flow Hydrograph=OZZERI          ,tronco_1        ,649
Stage Flow Hydrograph=OZZERI          ,tronco_1        ,648
Stage Flow Hydrograph=OZZERI          ,tronco_1        ,647
Stage Flow Hydrograph=OZZERI          ,tronco_1        ,646
Stage Flow Hydrograph=OZZERI          ,tronco_1        ,645
Stage Flow Hydrograph=OZZERI          ,tronco_1        ,644
Stage Flow Hydrograph=OZZERI          ,tronco_1        ,643
Stage Flow Hydrograph=OZZERI          ,tronco_1        ,642
Stage Flow Hydrograph=OZZERI          ,tronco_1        ,498.8
Stage Flow Hydrograph=OZZERI          ,tronco_1        ,498.5
Stage Flow Hydrograph=OZZERI          ,tronco_1        ,498
Stage Flow Hydrograph=OZZERI          ,tronco_1        ,497
Stage Flow Hydrograph=OZZERI          ,tronco_1        ,496.5
Stage Flow Hydrograph=OZZERI          ,tronco_1        ,496
Stage Flow Hydrograph=OZZERI          ,tronco_1        ,495
Stage Flow Hydrograph=OZZERI          ,tronco_1        ,494
Stage Flow Hydrograph=OZZERI          ,tronco_1        ,493
Stage Flow Hydrograph=OZZERI          ,tronco_1        ,492
Stage Flow Hydrograph=OZZERI          ,tronco_1        ,491
Stage Flow Hydrograph=OZZERI          ,tronco_1        ,490
Stage Flow Hydrograph=OZZERI          ,tronco_1        ,489
Stage Flow Hydrograph=OZZERI          ,tronco_1        ,488
Stage Flow Hydrograph=OZZERI          ,tronco_1        ,487
Stage Flow Hydrograph=OZZERI          ,tronco_1        ,486
Stage Flow Hydrograph=OZZERI          ,tronco_1        ,485
Stage Flow Hydrograph=OZZERI          ,tronco_1        ,484
Stage Flow Hydrograph=OZZERI          ,tronco_1        ,483
Stage Flow Hydrograph=OZZERI          ,tronco_1        ,482
Stage Flow Hydrograph=OZZERI          ,tronco_1        ,481
Stage Flow Hydrograph=OZZERI          ,tronco_1        ,480
Stage Flow Hydrograph=OZZERI          ,tronco_1        ,479
Stage Flow Hydrograph=OZZERI          ,tronco_1        ,478
Stage Flow Hydrograph=OZZERI          ,tronco_1        ,477
Stage Flow Hydrograph=OZZERI          ,tronco_1        ,476
Stage Flow Hydrograph=OZZERI          ,tronco_1        ,475
Stage Flow Hydrograph=OZZERI          ,tronco_1        ,474
Stage Flow Hydrograph=OZZERI          ,tronco_1        ,473.5
Stage Flow Hydrograph=OZZERI          ,tronco_1        ,473
Stage Flow Hydrograph=OZZERI          ,tronco_1        ,472.9
Stage Flow Hydrograph=OZZERI          ,tronco_1        ,472.7
Stage Flow Hydrograph=OZZERI          ,tronco_1        ,472
Stage Flow Hydrograph=OZZERI          ,tronco_1        ,471
Stage Flow Hydrograph=OZZERI          ,tronco_1        ,470
Stage Flow Hydrograph=OZZERI          ,tronco_1        ,469
Stage Flow Hydrograph=OZZERI          ,tronco_1        ,468
Stage Flow Hydrograph=OZZERI          ,tronco_1        ,467
Stage Flow Hydrograph=OZZERI          ,tronco_1        ,466
Stage Flow Hydrograph=OZZERI          ,tronco_1        ,465
Stage Flow Hydrograph=OZZERI          ,tronco_1        ,464
Stage Flow Hydrograph=OZZERI          ,tronco_1        ,463
Stage Flow Hydrograph=OZZERI          ,tronco_1        ,462
Stage Flow Hydrograph=OZZERI          ,tronco_1        ,461
Stage Flow Hydrograph=OZZERI          ,tronco_1        ,460
Stage Flow Hydrograph=OZZERI          ,tronco_1        ,459
Stage Flow Hydrograph=OZZERI          ,tronco_1        ,458
Stage Flow Hydrograph=OZZERI          ,tronco_1        ,457
Stage Flow Hydrograph=OZZERI          ,tronco_1        ,456
Stage Flow Hydrograph=OZZERI          ,tronco_1        ,455
Stage Flow Hydrograph=OZZERI          ,tronco_1        ,454
Stage Flow Hydrograph=OZZERI          ,tronco_1        ,453
Stage Flow Hydrograph=OZZERI          ,tronco_1        ,452
Stage Flow Hydrograph=OZZERI          ,tronco_1        ,451
Stage Flow Hydrograph=OZZERI          ,tronco_1        ,450.2
Stage Flow Hydrograph=OZZERI          ,tronco_1        ,450
Stage Flow Hydrograph=OZZERI          ,tronco_1        ,449
Stage Flow Hydrograph=OZZERI          ,tronco_1        ,448
Stage Flow Hydrograph=OZZERI          ,tronco_1        ,447.8
Stage Flow Hydrograph=OZZERI          ,tronco_1        ,447.5
Stage Flow Hydrograph=OZZERI          ,tronco_1        ,447
Stage Flow Hydrograph=OZZERI          ,tronco_1        ,446
Stage Flow Hydrograph=OZZERI          ,tronco_1        ,398
Stage Flow Hydrograph=OZZERI          ,tronco_1        ,397
Stage Flow Hydrograph=OZZERI          ,tronco_1        ,396
Stage Flow Hydrograph=OZZERI          ,tronco_1        ,395.5
Stage Flow Hydrograph=OZZERI          ,tronco_1        ,395
Stage Flow Hydrograph=OZZERI          ,tronco_1        ,394
Stage Flow Hydrograph=OZZERI          ,tronco_1        ,393
Stage Flow Hydrograph=OZZERI          ,tronco_1        ,392
Stage Flow Hydrograph=OZZERI          ,tronco_1        ,391
Stage Flow Hydrograph=OZZERI          ,tronco_1        ,390
Stage Flow Hydrograph=OZZERI          ,tronco_1        ,388
Stage Flow Hydrograph=OZZERI          ,tronco_1        ,387
Stage Flow Hydrograph=OZZERI          ,tronco_1        ,386
Stage Flow Hydrograph=OZZERI          ,tronco_1        ,385
Stage Flow Hydrograph=OZZERI          ,tronco_1        ,384
Stage Flow Hydrograph=OZZERI          ,tronco_1        ,383
Stage Flow Hydrograph=OZZERI          ,tronco_1        ,382
Stage Flow Hydrograph=OZZERI          ,tronco_1        ,381
Stage Flow Hydrograph=OZZERI          ,tronco_1        ,380
Stage Flow Hydrograph=OZZERI          ,tronco_1        ,379
Stage Flow Hydrograph=OZZERI          ,tronco_1        ,378
Stage Flow Hydrograph=OZZERI          ,tronco_1        ,377
Stage Flow Hydrograph=OZZERI          ,tronco_1        ,376
Stage Flow Hydrograph=OZZERI          ,tronco_1        ,375
Stage Flow Hydrograph=OZZERI          ,tronco_1        ,374
Stage Flow Hydrograph=OZZERI          ,tronco_1        ,373
Stage Flow Hydrograph=OZZERI          ,tronco_1        ,372
Stage Flow Hydrograph=OZZERI          ,tronco_1        ,371
Stage Flow Hydrograph=OZZERI          ,tronco_1        ,369
Stage Flow Hydrograph=OZZERI          ,tronco_1        ,368
Stage Flow Hydrograph=OZZERI          ,tronco_1        ,367
Stage Flow Hydrograph=OZZERI          ,tronco_1        ,366
Stage Flow Hydrograph=OZZERI          ,tronco_1        ,365
Stage Flow Hydrograph=OZZERI          ,tronco_1        ,364
Stage Flow Hydrograph=OZZERI          ,tronco_1        ,363
Stage Flow Hydrograph=OZZERI          ,tronco_1        ,362
Stage Flow Hydrograph=OZZERI          ,tronco_1        ,361
Stage Flow Hydrograph=OZZERI          ,tronco_1        ,360.5
Stage Flow Hydrograph=OZZERI          ,tronco_1        ,360.49
Stage Flow Hydrograph=OZZERI          ,tronco_1        ,360.48
Stage Flow Hydrograph=OZZERI          ,tronco_1        ,360.47
Stage Flow Hydrograph=OZZERI          ,tronco_1        ,360.33
Stage Flow Hydrograph=OZZERI          ,tronco_1        ,360.32
Stage Flow Hydrograph=OZZERI          ,tronco_1        ,360.31
Stage Flow Hydrograph=OZZERI          ,tronco_1        ,360.2
Stage Flow Hydrograph=OZZERI          ,tronco_1        ,360
Stage Flow Hydrograph=OZZERI          ,tronco_1        ,359.2
Stage Flow Hydrograph=OZZERI          ,tronco_1        ,359
Stage Flow Hydrograph=OZZERI          ,tronco_1        ,358.99
Stage Flow Hydrograph=OZZERI          ,tronco_1        ,358.98
Stage Flow Hydrograph=OZZERI          ,tronco_1        ,358.97
Stage Flow Hydrograph=OZZERI          ,tronco_1        ,358.96
Stage Flow Hydrograph=OZZERI          ,tronco_1        ,358.95
Stage Flow Hydrograph=OZZERI          ,tronco_1        ,358.94
Stage Flow Hydrograph=OZZERI          ,tronco_1        ,358.93
Stage Flow Hydrograph=OZZERI          ,tronco_1        ,358.33
Stage Flow Hydrograph=OZZERI          ,tronco_1        ,358.32
Stage Flow Hydrograph=OZZERI          ,tronco_1        ,358.31
Stage Flow Hydrograph=OZZERI          ,tronco_1        ,358.2
Stage Flow Hydrograph=OZZERI          ,tronco_1        ,358
Stage Flow Hydrograph=OZZERI          ,tronco_1        ,357.99
Stage Flow Hydrograph=OZZERI          ,tronco_1        ,357.98
Stage Flow Hydrograph=OZZERI          ,tronco_1        ,357.97
Stage Flow Hydrograph=OZZERI          ,tronco_1        ,357.96
Stage Flow Hydrograph=OZZERI          ,tronco_1        ,357.34
Stage Flow Hydrograph=OZZERI          ,tronco_1        ,357.33
Stage Flow Hydrograph=OZZERI          ,tronco_1        ,357.32
Stage Flow Hydrograph=OZZERI          ,tronco_1        ,357.31
Stage Flow Hydrograph=OZZERI          ,tronco_1        ,357.2
Stage Flow Hydrograph=OZZERI          ,tronco_1        ,357
Stage Flow Hydrograph=OZZERI          ,tronco_1        ,356.99
Stage Flow Hydrograph=OZZERI          ,tronco_1        ,356.98
Stage Flow Hydrograph=OZZERI          ,tronco_1        ,356.97
Stage Flow Hydrograph=OZZERI          ,tronco_1        ,356.96
Stage Flow Hydrograph=OZZERI          ,tronco_1        ,356.95
Stage Flow Hydrograph=OZZERI          ,tronco_1        ,356.35
Stage Flow Hydrograph=OZZERI          ,tronco_1        ,356.34
Stage Flow Hydrograph=OZZERI          ,tronco_1        ,356.33
Stage Flow Hydrograph=OZZERI          ,tronco_1        ,356.32
Stage Flow Hydrograph=OZZERI          ,tronco_1        ,356.31
Stage Flow Hydrograph=OZZERI          ,tronco_1        ,356.2
Stage Flow Hydrograph=OZZERI          ,tronco_1        ,356
Stage Flow Hydrograph=OZZERI          ,tronco_1        ,355.99
Stage Flow Hydrograph=OZZERI          ,tronco_1        ,355.98
Stage Flow Hydrograph=OZZERI          ,tronco_1        ,355.97
Stage Flow Hydrograph=OZZERI          ,tronco_1        ,355.96
Stage Flow Hydrograph=OZZERI          ,tronco_1        ,355.95
Stage Flow Hydrograph=OZZERI          ,tronco_1        ,355.35
Stage Flow Hydrograph=OZZERI          ,tronco_1        ,355.34
Stage Flow Hydrograph=OZZERI          ,tronco_1        ,355.33
Stage Flow Hydrograph=OZZERI          ,tronco_1        ,355.32
Stage Flow Hydrograph=OZZERI          ,tronco_1        ,355.31
Stage Flow Hydrograph=OZZERI          ,tronco_1        ,355.2
Stage Flow Hydrograph=OZZERI          ,tronco_1        ,355
Stage Flow Hydrograph=OZZERI          ,tronco_1        ,354.99
Stage Flow Hydrograph=OZZERI          ,tronco_1        ,354.98
Stage Flow Hydrograph=OZZERI          ,tronco_1        ,354.97
Stage Flow Hydrograph=OZZERI          ,tronco_1        ,354.96
Stage Flow Hydrograph=OZZERI          ,tronco_1        ,354.95
Stage Flow Hydrograph=OZZERI          ,tronco_1        ,354.35
Stage Flow Hydrograph=OZZERI          ,tronco_1        ,354.34
Stage Flow Hydrograph=OZZERI          ,tronco_1        ,354.33
Stage Flow Hydrograph=OZZERI          ,tronco_1        ,354.32
Stage Flow Hydrograph=OZZERI          ,tronco_1        ,354.31
Stage Flow Hydrograph=OZZERI          ,tronco_1        ,354
Stage Flow Hydrograph=OZZERI          ,tronco_1        ,353.2
Stage Flow Hydrograph=OZZERI          ,tronco_1        ,353
Stage Flow Hydrograph=OZZERI          ,tronco_1        ,352
Stage Flow Hydrograph=OZZERI          ,tronco_1        ,351

--- ozz_def.p01 (plan) ---

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Plan Title=Plan 01
Short Identifier=Plan 01
Geom File=g01
Flow File=u01
Computation Interval=30MIN
Run HTab= 0
Instantaneous Interval=3HOUR
Write IC File= 0
Write Velocity= 0
Write Detailed= 0
Stage Flow Hydrograph=OZZERI          ,tronco_1        ,789
Stage Flow Hydrograph=OZZERI          ,tronco_1        ,787
Stage Flow Hydrograph=OZZERI          ,tronco_1        ,774
Stage Flow Hydrograph=OZZERI          ,tronco_1        ,389
Stage Flow Hydrograph=OZZERI          ,tronco_1        ,370

--- ozz_def.p02 (plan) ---

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Plan Title=plan 01 mod
Short Identifier=11
Geom File=g01
Flow File=u02
Std Step Tol= 0.0098
Critical Tol= 0.0098
Max Error Tol= 0.3281
Computation Interval=5MIN
Instantaneous Interval=3HOUR
Write IC File= 0
Write Velocity= 0
Write Detailed= 0
Stage Flow Hydrograph=OZZERI          ,tronco_1        ,789
Stage Flow Hydrograph=OZZERI          ,tronco_1        ,787
Stage Flow Hydrograph=OZZERI          ,tronco_1        ,774
Stage Flow Hydrograph=OZZERI          ,tronco_1        ,389
Stage Flow Hydrograph=OZZERI          ,tronco_1        ,370

--- ozz_def.p03 (plan) ---

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Plan Title=Plan 03
Short Identifier=Plan 03
Geom File=g01
Flow File=u03
Std Step Tol= 0.0098
Critical Tol= 0.0098
Max Error Tol= 0.3281
Computation Interval=5MIN
Run UNet= 0
Run PostProcess= 0
Instantaneous Interval=3HOUR
Write IC File= 0
Write Velocity= 0
Write Detailed= 0
Stage Flow Hydrograph=OZZERI          ,tronco_1        ,789
Stage Flow Hydrograph=OZZERI          ,tronco_1        ,787
Stage Flow Hydrograph=OZZERI          ,tronco_1        ,774
Stage Flow Hydrograph=OZZERI          ,tronco_1        ,389
Stage Flow Hydrograph=OZZERI          ,tronco_1        ,370

--- ozz_def.p04 (plan) ---

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Plan Title=Plan 04
Short Identifier=Plan 04
Geom File=g03
Flow File=u01
Computation Interval=30MIN
Write IC File= 0
Write Velocity= 0
Write Detailed= 0
Stage Flow Hydrograph=OZZERI          ,tronco_1        ,789
Stage Flow Hydrograph=OZZERI          ,tronco_1        ,787
Stage Flow Hydrograph=OZZERI          ,tronco_1        ,774
Stage Flow Hydrograph=OZZERI          ,tronco_1        ,389
Stage Flow Hydrograph=OZZERI          ,tronco_1        ,370

--- ozz_def.p05 (plan) ---

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Plan Title=Plan 05
Short Identifier=Plan 04
Geom File=g03
Flow File=u01

--- ozz_def.p06 (plan) ---

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Plan Title=Plan 06
Short Identifier=Plan 06
Geom File=g04
Flow File=u01

--- ozz_def.f01 (steady flow) ---

Flow Title=Flow 01
Version=Version 3.0.1  Mar 2001
Number of Profiles= 1
Profile Names=PF 1
DSS Import GetInterval= 0
DSS Import GetPeak= 0
DSS Import FillOption= 0

--- ozz_def.u04 (unsteady flow) ---

Flow Title=ozzoretto+bottacci+livelli serchio 30a
Version=Version 3.0.1  Mar 2001
Use Restart= 0
Initial Flow Loc=OZZERI          ,tronco_1        ,850     ,706.293
Initial Storage Elev=c01             ,27.887
Initial Storage Elev=c02             ,30
Initial Storage Elev=c04             ,30
Initial Storage Elev=c03             ,30
Initial Storage Elev=c05             ,30
Initial Storage Elev=c07             ,30
Initial Storage Elev=c06             ,34
Initial Storage Elev=c08             ,37
Initial Storage Elev=c10             ,33
Initial Storage Elev=c09             ,33
Initial Storage Elev=c11             ,33
Initial Storage Elev=c13             ,33
Initial Storage Elev=c15             ,30
Initial Storage Elev=c12             ,30
Initial Storage Elev=c14             ,33
Initial Storage Elev=c20             ,30
Initial Storage Elev=c18             ,33
Initial Storage Elev=c16             ,33
Initial Storage Elev=c22             ,33
Boundary Location=OZZERI          ,tronco_1        ,850     ,        ,                ,
Interval=1HOUR
Flow Hydrograph= 73
  706.29  921.91 1137.53 1353.15 1568.76 1784.38    2000 1784.38 1568.76 1353.15
 1137.53  921.91  706.29  706.29  706.29  706.29  706.29  706.29  706.29  706.29
  706.29  706.29  706.29  706.29  706.29  706.29  706.29  706.29  706.29  706.29
  706.29  706.29  706.29  706.29  706.29  706.29  706.29  706.29  706.29  706.29
  706.29  706.29  706.29  706.29  706.29  706.29  706.29  706.29  706.29  706.29
  706.29  706.29  706.29  706.29  706.29  706.29  706.29  706.29  706.29  706.29
  706.29  706.29  706.29  706.29  706.29  706.29  706.29  706.29  706.29  706.29
  706.29  706.29  706.29
Use DSS=False
Use Fixed Start Time=False
Is Critical Boundary=False
Boundary Location=OZZERI          ,tronco_1        ,771     ,770     ,                ,
Interval=1HOUR
Uniform Lateral Inflow Hydrograph= 25
       0  333.33  666.67    1000 1333.33 1666.67    2000 1666.67 1333.33    1000
  666.67  333.33       0       0       0       0       0       0       0       0
       0       0       0       0       0
Use DSS=False
Use Fixed Start Time=False
Is Critical Boundary=False
Boundary Location=OZZERI          ,tronco_1        ,351     ,        ,                ,
Interval=1HOUR
Stage Hydrograph= 25
      28   28.45   28.91   29.36   29.81   30.26   30.72   31.17   31.62   32.07
   32.53   32.98   33.43   32.98   32.53   32.07   31.62   31.17   30.72   30.26
   29.81   29.36   28.91   28.45      28
Use DSS=False
Use Fixed Start Time=False
Is Critical Boundary=False

--- ozz_def.u01 (unsteady flow) ---

Flow Title=Unsteady Flow 01
Version=Version 3.0.1  Mar 2001
Use Restart= 0
Initial Flow Loc=OZZERI          ,tronco_1        ,850     ,706.293
Initial Storage Elev=c01             ,27.887
Initial Storage Elev=c02             ,30
Initial Storage Elev=c04             ,30
Initial Storage Elev=c03             ,30
Initial Storage Elev=c05             ,30
Initial Storage Elev=c07             ,30
Initial Storage Elev=c06             ,34
Initial Storage Elev=c08             ,37
Initial Storage Elev=c10             ,33
Initial Storage Elev=c09             ,33
Initial Storage Elev=c11             ,33
Initial Storage Elev=c13             ,33
Initial Storage Elev=c15             ,30
Initial Storage Elev=c12             ,30
Initial Storage Elev=c14             ,33
Initial Storage Elev=c20             ,30
Initial Storage Elev=c18             ,33
Initial Storage Elev=c16             ,33
Initial Storage Elev=c22             ,33
Boundary Location=OZZERI          ,tronco_1        ,850     ,        ,                ,
Interval=1HOUR
Flow Hydrograph= 73
  706.29  921.91 1137.53 1353.15 1568.76 1784.38    2000 1784.38 1568.76 1353.15
 1137.53  921.91  706.29  706.29  706.29  706.29  706.29  706.29  706.29  706.29
  706.29  706.29  706.29  706.29  706.29  706.29  706.29  706.29  706.29  706.29
  706.29  706.29  706.29  706.29  706.29  706.29  706.29  706.29  706.29  706.29
  706.29  706.29  706.29  706.29  706.29  706.29  706.29  706.29  706.29  706.29
  706.29  706.29  706.29  706.29  706.29  706.29  706.29  706.29  706.29  706.29
  706.29  706.29  706.29  706.29  706.29  706.29  706.29  706.29  706.29  706.29
  706.29  706.29  706.29
Use DSS=False
Use Fixed Start Time=False
Is Critical Boundary=False
Boundary Location=OZZERI          ,tronco_1        ,771     ,770     ,                ,
Interval=1HOUR
Uniform Lateral Inflow Hydrograph= 25
       0  333.33  666.67    1000 1333.33 1666.67    2000 1666.67 1333.33    1000
  666.67  333.33       0       0       0       0       0       0       0       0
       0       0       0       0       0
Use DSS=False
Use Fixed Start Time=False
Is Critical Boundary=False
Boundary Location=OZZERI          ,tronco_1        ,351     ,        ,                ,
Friction Slope=.0005

--- ozz_def.u02 (unsteady flow) ---

Flow Title=Flow_mod
Version=Version 3.0.1  Mar 2001
Use Restart= 0
Initial Flow Loc=OZZERI          ,tronco_1        ,850     ,706.293
Initial Storage Elev=c01             ,27.887
Initial Storage Elev=c02             ,31.168

--- ozz_def.u03 (unsteady flow) ---

Flow Title=flow_mod_2
Version=Version 3.0.1  Mar 2001
Use Restart= 0
Initial Flow Loc=OZZERI          ,tronco_1        ,850     ,706.293
Boundary Location=OZZERI          ,tronco_1        ,850     ,        ,                ,
Interval=1HOUR
Flow Hydrograph= 73
 706.293 882.867 1059.441236.0131412.587 1589.161765.7331942.307 2118.882295.453
2472.027  2648.62825.173  2648.62472.0272295.453 2118.881942.3071765.733 1589.16
1412.5871236.013 1059.44 882.867 706.293 706.293 706.293 706.293 706.293 706.293
 706.293 706.293 706.293 706.293 706.293 706.293 706.293 706.293 706.293 706.293
 706.293 706.293 706.293 706.293 706.293 706.293 706.293 706.293 706.293 706.293
 706.293 706.293 706.293 706.293 706.293 706.293 706.293 706.293 706.293 706.293
 706.293 706.293 706.293 706.293 706.293 706.293 706.293 706.293 706.293 706.293
 706.293 706.293 706.293
Use DSS=False
Use Fixed Start Time=False
Is Critical Boundary=False
Boundary Location=OZZERI          ,tronco_1        ,351     ,        ,                ,
Friction Slope=.001

--- ozz_def.g04 (geometry) ---

Geom Title=studio_ozz_mod3
Version=Version 3.0.1  Mar 2001

River Reach=OZZERI          ,tronco_1
Reach XY= 30
      5320661.84     15922184.12      5318495.83     15921858.83
      5317765.22     15921510.14      5317189.24     15921610.14
      5316790.81      15922241.6      5315833.96     15922218.21
       5315110.3     15922597.11      5313841.54     15922949.93
      5313163.85     15923746.75      5312520.77      15923904.2
      5311955.15     15923674.57       5311364.5     15924050.16
       5310743.9      15924175.2      5309703.12     15925174.64
      5307998.29     15925590.06      5307356.04     15926436.29
      5306751.61     15926587.17      5305859.19      15926331.2
      5303929.46     15926915.81      5302582.78     15927653.31
       5302235.6     15928206.23       5301701.8     15928270.41
      5299727.85     15927473.06      5297844.39     15926367.36
      5295995.28     15924953.87      5293639.44     15918548.23
      5291364.37     15915034.22      5293047.74     15912967.68
       5295268.9      15911148.1      5295416.57     15910634.74

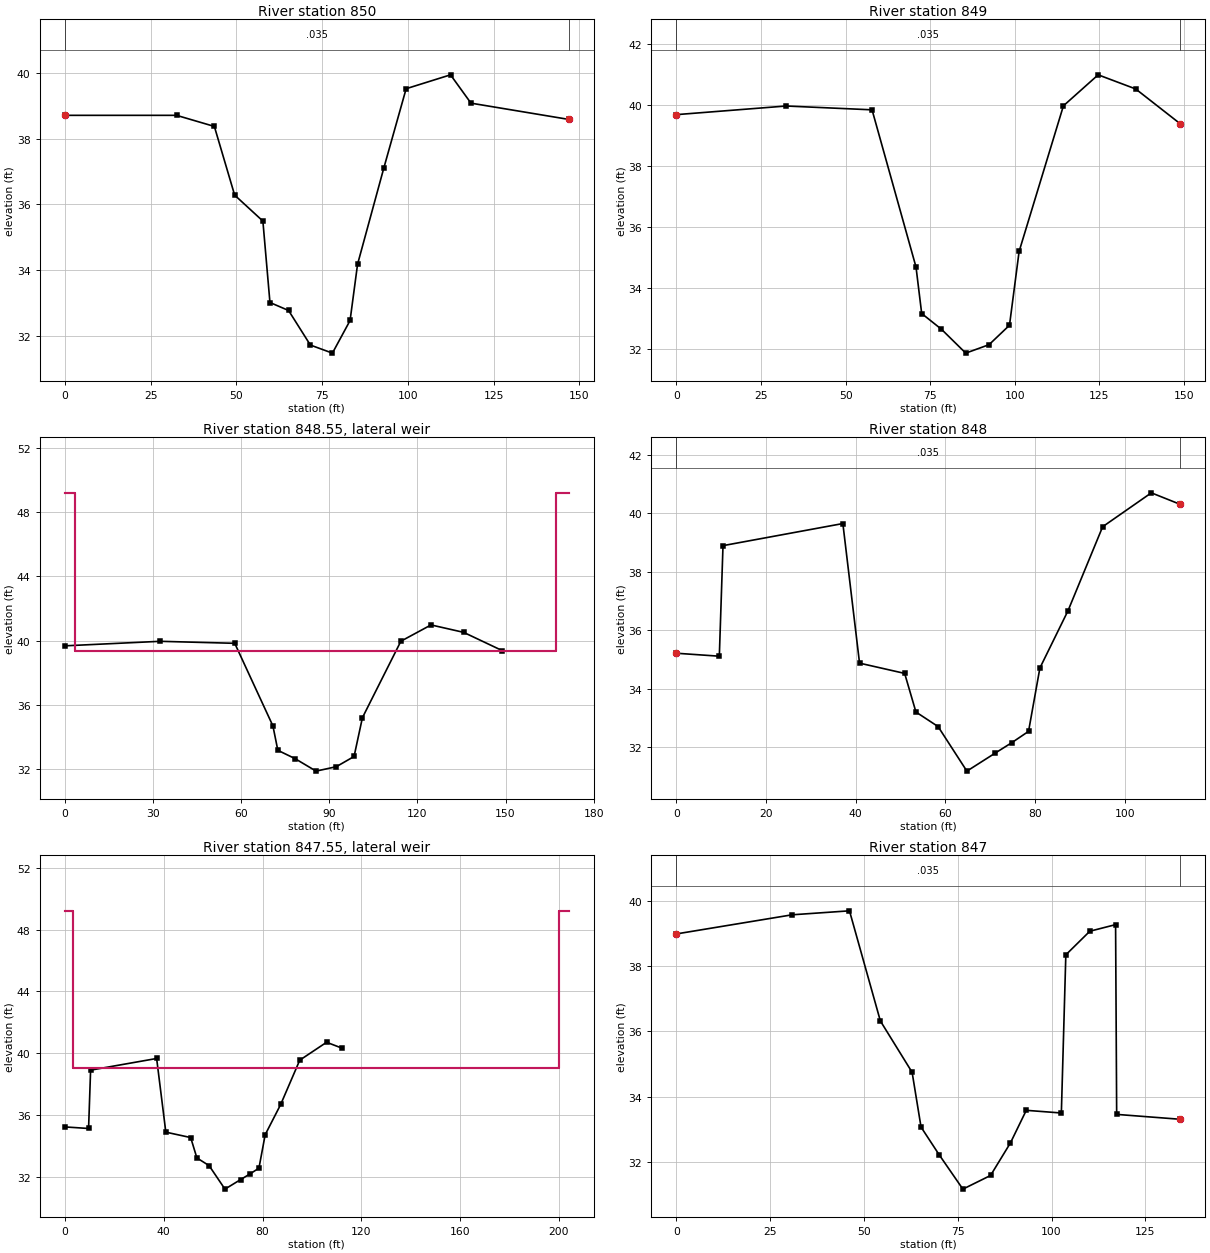
Type RM Length L Ch R = 1 ,850     ,192.913,192.913,192.913
XS GIS Cut Line= 4
       5320574.7     15922040.94      5320488.85     15922160.04
      5320488.85     15922160.04      5320488.85     15922160.04
#Sta/Elev= 16
       0  38.707   32.53  38.707   43.56  38.369  49.478  36.276   57.71  35.486
   59.77  33.005  65.203  32.762  71.558  31.709  77.986  31.463  83.136  32.457
  85.318   34.17  92.986  37.106  99.485  39.518 112.428  39.941 118.389  39.078
 146.893  38.583
#Mann= 3 , 0 , 0
       0    .035       0       0    .035       0 146.893    .035       0
Bank Sta=0,146.893
XS Rating Curve= 0
Exp/Cntr=.3,.1

Type RM Length L Ch R = 1 ,849     ,248.196,248.196,248.196
XS GIS Cut Line= 2
      5320340.88     15921961.98      5320348.85      15922110.2
#Sta/Elev= 14
       0  39.682  32.428  39.964  57.799  39.839  70.794  34.695  72.467  33.176
  78.307  32.661  85.489   31.88  92.372  32.156  98.419  32.792 101.263  35.207
 114.357   39.97 124.626  40.984 135.715  40.522 148.881  39.383
#Mann= 3 , 0 , 0
       0    .035       0       0    .035       0 148.881    .035       0
Bank Sta=0,148.881
XS Rating Curve= 0
Exp/Cntr=.3,.1

Type RM Length L Ch R = 6 ,848.55  ,,,
Lateral Weir Pos= 3
Lateral Weir End=                ,                ,        ,c15
Lateral Weir Distance=3.281
Lateral Weir WD=9.843
Lateral Weir Coef=3.01
Lateral Weir Is Ogee= 0
Lateral Weir WSCriteria=-1
Lateral Weir SE= 6
       0   49.21    3.28   49.21    3.28   39.34  167.25   39.34  167.25   49.21
   171.5   49.21

Type RM Length L Ch R = 1 ,848     ,86.778,86.778,86.778
XS GIS Cut Line= 2
      5320102.53     15922040.32      5320113.16     15922151.35
#Sta/Elev= 17
       0  35.213   9.557  35.112  10.377  38.891  37.119  39.646   40.84  34.875
  50.906  34.524  53.419  33.205  58.363  32.707   64.79  31.184  71.112  31.801
  74.803  32.156  78.547  32.543  81.076  34.708  87.362   36.67  95.079  39.537
 105.945  40.696 112.388  40.302
#Mann= 3 , 0 , 0
       0    .035       0       0    .035       0 112.388    .035       0
Bank Sta=0,112.388
XS Rating Curve= 0
Exp/Cntr=.3,.1

Type RM Length L Ch R = 6 ,847.55  ,,,
Lateral Weir Pos= 3
Lateral Weir End=                ,                ,        ,c15
Lateral Weir Distance=3.281
Lateral Weir WD=9.843
Lateral Weir Coef=3.01
Lateral Weir Is Ogee= 0
Lateral Weir WSCriteria=-1
Lateral Weir SE= 6
       0   49.21    3.28   49.21    3.28   39.02     200   39.02     200   49.21
     204   49.21

Type RM Length L Ch R = 1 ,847     ,136.056,136.056,136.056
XS GIS Cut Line= 3
      5320019.29     15922037.73      5320016.77     15922171.82
      5320016.77     15922171.82
#Sta/Elev= 17
       0  38.996  30.843  39.583  46.129  39.705  54.364  36.322  62.831  34.744
  65.213  33.061      70  32.218  76.371  31.155  83.753  31.575  89.049  32.575
  93.274  33.576 102.628  33.494 103.822  38.353 110.217  39.078  117.09  39.281
 117.379  33.451 134.327  33.301
#Mann= 3 , 0 , 0
       0    .035       0       0    .035       0 134.327    .035       0
Bank Sta=0,134.327
XS Rating Curve= 0
Exp/Cntr=.3,.1

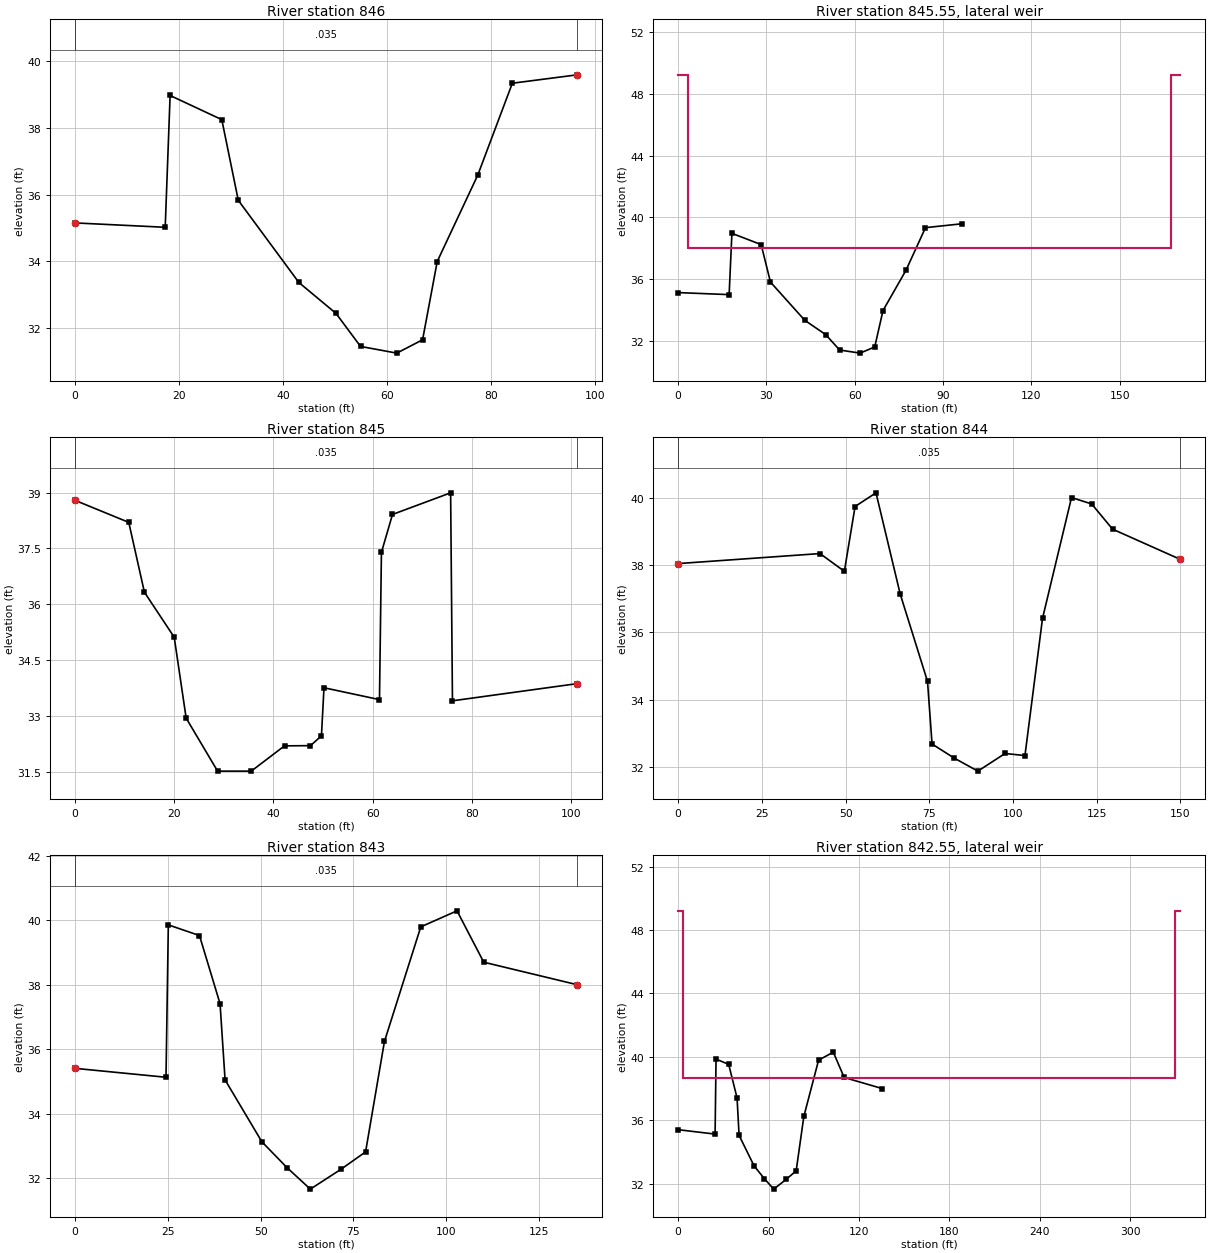
Type RM Length L Ch R = 1 ,846     ,321.03,321.03,321.03
XS GIS Cut Line= 2
      5319890.55     15922042.29      5319879.56     15922138.02
#Sta/Elev= 14
       0  35.151   17.31   35.02  18.251  38.976  28.186  38.251  31.352   35.83
  43.002  33.363  50.144  32.434  54.849  31.444  61.818  31.243  66.778  31.644
   69.59  33.993  77.395  36.591  84.026  39.344  96.506  39.596
#Mann= 3 , 0 , 0
       0    .035       0       0    .035       0  96.506    .035       0
Bank Sta=0,96.506
XS Rating Curve= 0
Exp/Cntr=.3,.1

Type RM Length L Ch R = 6 ,845.55  ,,,
Lateral Weir Pos= 0
Lateral Weir End=                ,                ,        ,c22
Lateral Weir Distance=3.281
Lateral Weir WD=9.843
Lateral Weir Coef=3.01
Lateral Weir Is Ogee= 0
Lateral Weir WSCriteria=-1
Lateral Weir SE= 6
       0   49.21    3.28   49.21    3.28   38.03  167.32   38.03  167.32   49.21
   170.6   49.21

Type RM Length L Ch R = 1 ,845     ,203.248,203.248,203.248
XS GIS Cut Line= 2
      5319569.95      15922006.1      5319565.85     15922106.96
#Sta/Elev= 17
       0  38.793  10.814  38.202  13.967  36.325   19.98  35.115  22.388   32.94
  28.727  31.516  35.518  31.516  42.221  32.195  47.461  32.201  49.669  32.464
  50.184  33.757  61.375  33.438  61.768  37.395  63.999  38.415  75.722  38.996
  76.093  33.406 101.263  33.868
#Mann= 3 , 0 , 0
       0    .035       0       0    .035       0 101.263    .035       0
Bank Sta=0,101.263
XS Rating Curve= 0
Exp/Cntr=.3,.1

Type RM Length L Ch R = 1 ,844     ,212.598,212.598,212.598
XS GIS Cut Line= 2
      5319383.92     15921920.96      5319356.86     15922068.21
#Sta/Elev= 17
       0  38.048  42.349  38.346  49.629  37.818  52.831  39.747  59.075  40.154
  66.312  37.139  74.462  34.541   75.82  32.677  82.451  32.257  89.505   31.87
  97.621  32.395 103.563  32.333 108.809  36.417  117.47  40.013 123.481  39.823
 129.741  39.072 149.961  38.173
#Mann= 3 , 0 , 0
       0    .035       0       0    .035       0 149.961    .035       0
Bank Sta=0,149.961
XS Rating Curve= 0
Exp/Cntr=.3,.1

Type RM Length L Ch R = 1 ,843     ,184.055,184.055,184.055
XS GIS Cut Line= 2
      5319174.51      15921910.6      5319144.32     15922042.29
#Sta/Elev= 16
       0  35.407  24.498  35.131  25.125  39.859  33.524  39.528  39.075  37.411
  40.427  35.049  50.344   33.13  57.133  32.326  63.419   31.66  71.654  32.274
  78.314  32.815  83.402  36.243  93.196  39.797 102.966  40.295 110.174  38.701
 135.394  38.002
#Mann= 3 , 0 , 0
       0    .035       0       0    .035       0 135.394    .035       0
Bank Sta=0,135.394
XS Rating Curve= 0
Exp/Cntr=.3,.1

Type RM Length L Ch R = 6 ,842.55  ,,,
Lateral Weir Pos= 0
Lateral Weir End=                ,                ,        ,c22
Lateral Weir Distance=3.281
Lateral Weir WD=9.843
Lateral Weir Coef=3.01
Lateral Weir Is Ogee= 0
Lateral Weir WSCriteria=-1
Lateral Weir SE= 6
       0   49.21    3.28   49.21    3.28   38.69     330   38.69     330   49.21
  333.28   49.21

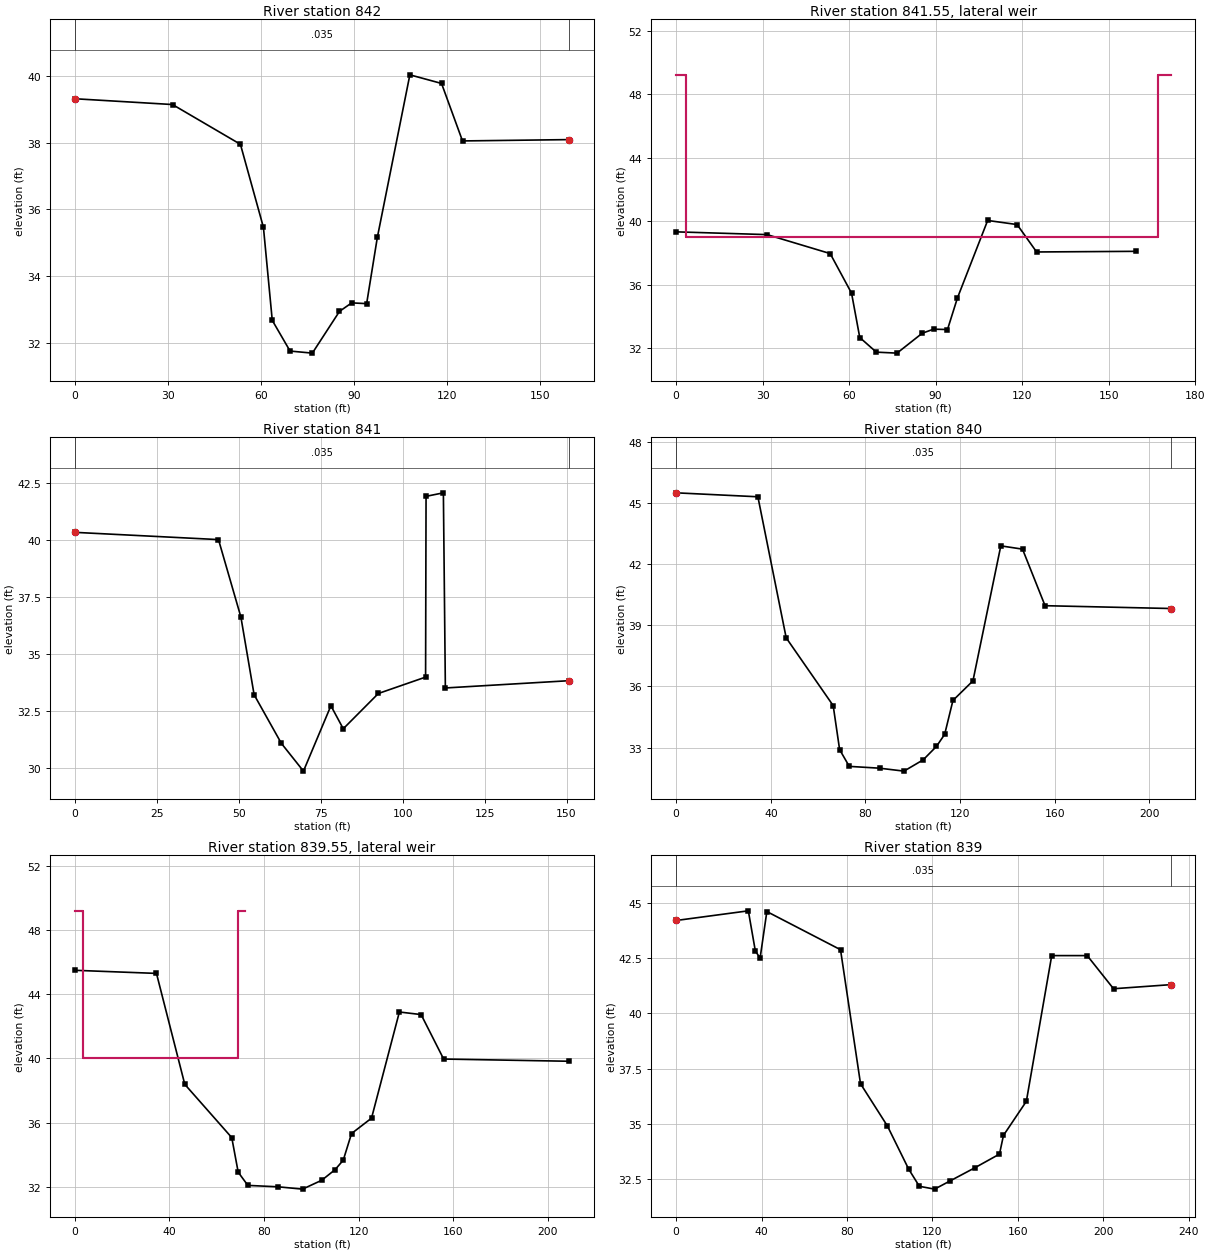
Type RM Length L Ch R = 1 ,842     ,211.909,211.909,211.909
XS GIS Cut Line= 2
      5318988.91     15921863.29       5318964.3     15922020.73
#Sta/Elev= 15
       0  39.321  31.516  39.147  53.415  37.953  60.833  35.459  63.678  32.667
  69.423  31.745  76.604  31.683  85.351  32.936  89.288  33.192  94.111  33.169
  97.559  35.157 108.045  40.039 118.261   39.78 125.023  38.054 159.416  38.094
#Mann= 3 , 0 , 0
       0    .035       0       0    .035       0 159.416    .035       0
Bank Sta=0,159.416
XS Rating Curve= 0
Exp/Cntr=.3,.1

Type RM Length L Ch R = 6 ,841.55  ,,,
Lateral Weir Pos= 3
Lateral Weir End=                ,                ,        ,c15
Lateral Weir Distance=3.281
Lateral Weir WD=9.843
Lateral Weir Coef=3.01
Lateral Weir Is Ogee= 0
Lateral Weir WSCriteria=-1
Lateral Weir SE= 6
       0   49.21    3.28   49.21    3.28   39.02  167.25   39.02  167.25   49.21
   171.5   49.21

Type RM Length L Ch R = 1 ,841     ,274.869,274.869,274.869
XS GIS Cut Line= 2
      5318769.32     15921833.56       5318768.9     15921983.92
#Sta/Elev= 14
       0  40.341  43.839  40.023  50.673  36.627  54.708  33.222  63.012  31.093
  69.754  29.875  78.127   32.74  81.896  31.732  92.602  33.278 107.008  33.996
 107.149  41.919 112.434  42.073 113.038   33.52 150.804  33.839
#Mann= 3 , 0 , 0
       0    .035       0       0    .035       0 150.804    .035       0
Bank Sta=0,150.804
XS Rating Curve= 0
Exp/Cntr=.3,.1

Type RM Length L Ch R = 1 ,840     ,197.343,197.343,197.343
XS GIS Cut Line= 2
      5318526.12     15921767.49      5318455.97     15921964.11
#Sta/Elev= 17
       0  45.499  34.531  45.305  46.496  38.383  66.355  35.059  69.072    32.9
  73.156  32.077  85.974  31.988   96.27  31.844 104.393  32.398 110.013  33.058
 113.468  33.648 116.969  35.312 125.423  36.273 137.195  42.897 146.375  42.736
 155.899  39.961 208.957  39.823
#Mann= 3 , 0 , 0
       0    .035       0       0    .035       0 208.957    .035       0
Bank Sta=0,208.957
XS Rating Curve= 0
Exp/Cntr=.3,.1

Type RM Length L Ch R = 6 ,839.55  ,,,
Lateral Weir Pos= 3
Lateral Weir End=                ,                ,        ,c13
Lateral Weir Distance=3.281
Lateral Weir WD=9.843
Lateral Weir Coef=3.01
Lateral Weir Is Ogee= 0
Lateral Weir WSCriteria=-1
Lateral Weir SE= 6
       0   49.21    3.28   49.21    3.28      40    68.8      40    68.8   49.21
      72   49.21

Type RM Length L Ch R = 1 ,839     ,215.322,215.322,215.322
XS GIS Cut Line= 3
      5318380.25     15921656.53      5318273.59     15921861.29
      5318273.59     15921861.29
#Sta/Elev= 20
       0   44.19  33.786  44.626  37.057  42.818  39.291   42.49  42.457  44.593
  76.949  42.871  86.312  36.821  98.901  34.915 108.835  32.972 113.862  32.192
 121.001  32.064 128.323  32.438 139.734  33.022 151.378  33.645 153.251  34.491
 163.963  36.027  175.84  42.605 192.461  42.605 204.783  41.109 231.506  41.293
#Mann= 3 , 0 , 0
       0    .035       0       0    .035       0 231.506    .035       0
Bank Sta=0,231.506
XS Rating Curve= 0
Exp/Cntr=.3,.1

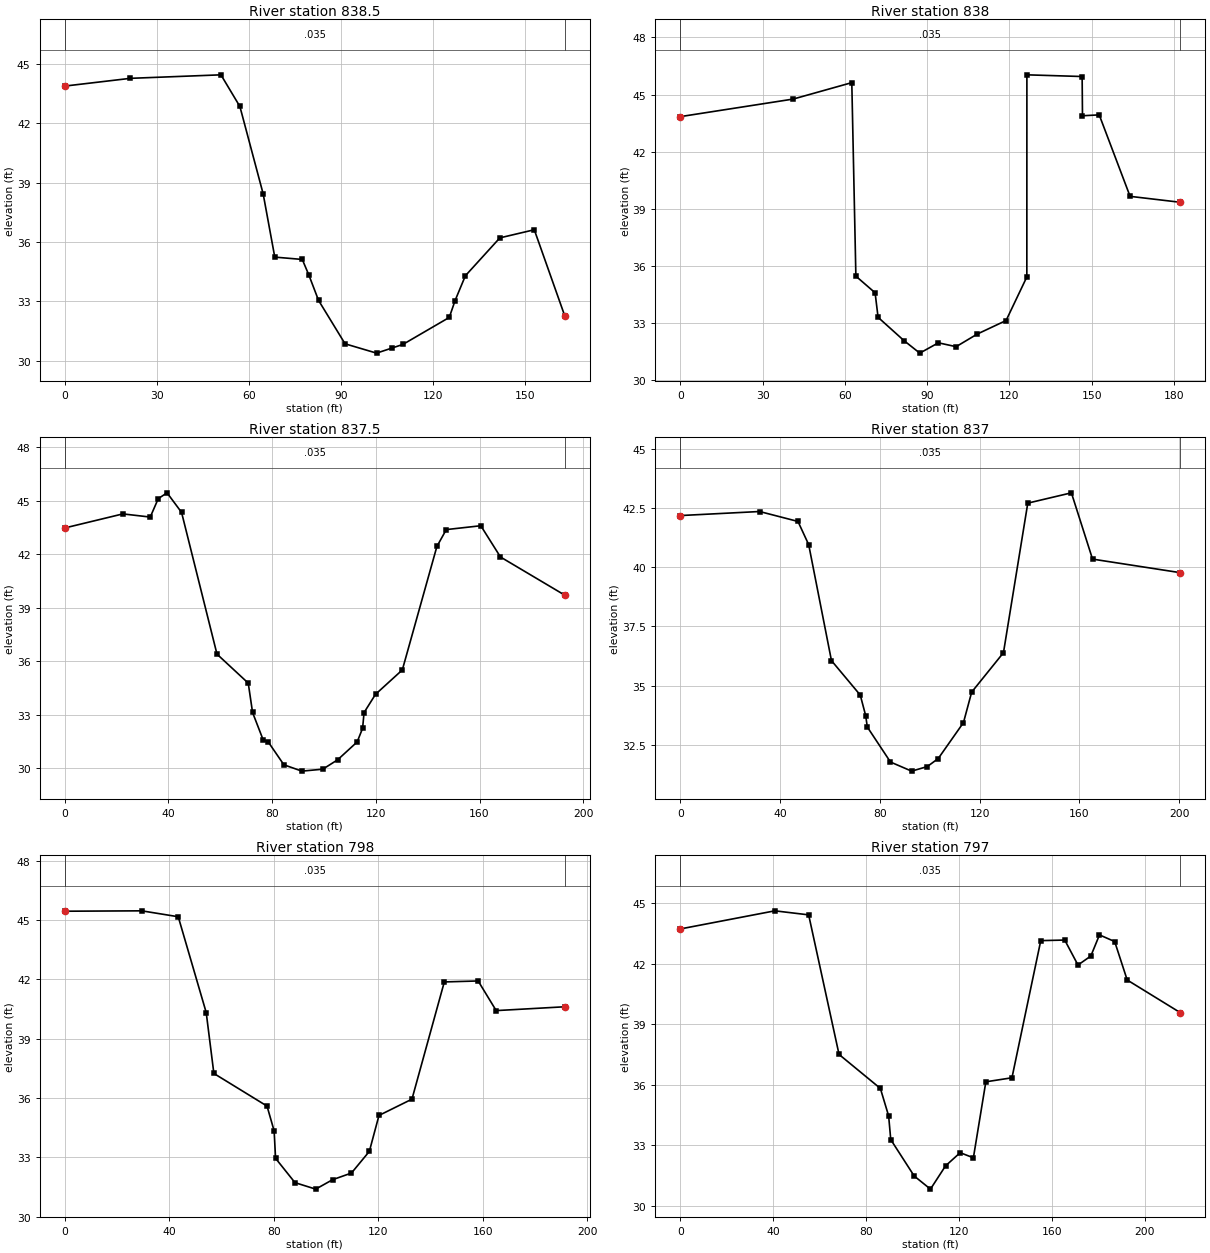
Type RM Length L Ch R = 1 ,838.5   ,30.84,30.84,30.84
XS GIS Cut Line= 3
      5318188.39     15921561.09       5318114.6     15921705.45
       5318114.6     15921705.45
#Sta/Elev= 19
       0  43.868  21.378  44.259  50.879  44.436  57.057  42.838  64.649  38.422
  68.425  35.236  77.388  35.118  79.551  34.324   82.69  33.051  91.332   30.86
 101.588   30.39 106.683   30.65 110.184   30.83 125.289  32.192 127.185  33.045
 130.535  34.295 141.768  36.207 152.989  36.617 162.963  32.251
#Mann= 3 , 0 , 0
       0    .035       0       0    .035       0 162.963    .035       0
Bank Sta=0,162.963
XS Rating Curve= 0
Exp/Cntr=.3,.1

Type RM Length L Ch R = 1 ,838     ,60.728,60.728,60.728
XS GIS Cut Line= 2
       5318160.2      15921556.2      5318065.42     15921708.37
#Sta/Elev= 19
       0  43.845  41.148  44.767  62.536   45.63  64.026  35.469   71.03  34.596
  72.123  33.307  81.522   32.09  87.326  31.427  94.114  31.969 100.571  31.765
 108.284  32.428 118.802   33.14 126.368  35.427 126.388   46.04 146.535  45.951
  146.66  43.891 152.766  43.937 164.019  39.659 182.372  39.347
#Mann= 3 , 0 , 0
       0    .035       0       0    .035       0 182.372    .035       0
Bank Sta=0,182.372
XS Rating Curve= 0
Exp/Cntr=.3,.1

Type RM Length L Ch R = 1 ,837.5   ,112.861,112.861,112.861
XS GIS Cut Line= 3
      5318109.61     15921521.33       5318006.1      15921683.5
       5318006.1      15921683.5
#Sta/Elev= 25
       0  43.465  22.408  44.252  32.966  44.075  36.053  45.108  39.446  45.433
  45.043  44.337  58.707  36.394  70.768   34.77  72.428  33.127  76.506  31.594
  78.451   31.48  84.514  30.194   91.46  29.839  99.524  29.948 105.269  30.476
 112.766  31.473 114.875  32.238  115.44   33.12 119.865  34.144   130.2  35.509
  143.54  42.428 147.162  43.373 160.472  43.589 168.064  41.837 192.913  39.695
#Mann= 3 , 0 , 0
       0    .035       0       0    .035       0 192.913    .035       0
Bank Sta=0,192.913
XS Rating Curve= 0
Exp/Cntr=.3,.1

Type RM Length L Ch R = 1 ,837     ,201.903,201.903,201.903
XS GIS Cut Line= 3
      5318004.43     15921461.61      5317915.16     15921641.08
      5317915.16     15921641.08
#Sta/Elev= 19
       0  42.185  31.788  42.356  47.172  41.936   51.47  40.955  60.597  36.053
  72.146  34.596  74.314  33.727  74.974  33.245  84.262  31.765  92.733  31.381
  98.996  31.572 103.399  31.913 113.517  33.432 116.808  34.721 129.554  36.388
 139.304   42.71 156.791  43.146 165.266  40.344 200.495   39.77
#Mann= 3 , 0 , 0
       0    .035       0       0    .035       0 200.495    .035       0
Bank Sta=0,200.495
XS Rating Curve= 0
Exp/Cntr=.3,.1

Type RM Length L Ch R = 1 ,798     ,173.819,173.819,173.819
XS GIS Cut Line= 3
       5317760.4     15921414.34      5317770.01     15921605.31
      5317770.01     15921605.31
#Sta/Elev= 19
       0  45.446  29.429  45.466  43.406  45.167  54.108  40.322  57.041  37.241
  77.379  35.591  80.098  34.337  80.646  32.949  88.077  31.719  96.007  31.391
 102.454  31.867 109.688  32.205 116.532  33.301 120.213  35.118 132.835  35.942
 145.213   41.87 158.159  41.919 165.062   40.42 191.352  40.614
#Mann= 3 , 0 , 0
       0    .035       0       0    .035       0 191.352    .035       0
Bank Sta=0,191.352
XS Rating Curve= 0
Exp/Cntr=.3,.1

Type RM Length L Ch R = 1 ,797     ,287.041,287.041,287.041
XS GIS Cut Line= 3
      5317588.81     15921417.36      5317596.36     15921632.38
      5317596.36     15921632.38
#Sta/Elev= 22
       0   43.73  40.722  44.629  55.272  44.429   68.36  37.503  86.155  35.817
  89.715  34.452  90.623  33.278 100.728   31.47 107.723   30.82 114.232  31.975
 120.518  32.628 126.211  32.375 131.575  36.145 142.818  36.345 155.223   43.15
 165.554  43.179 171.253  41.939 176.795  42.388 180.509  43.435  187.06  43.104
 192.441  41.198 215.364  39.573
#Mann= 3 , 0 , 0
       0    .035       0       0    .035       0 215.364    .035       0
Bank Sta=0,215.364
XS Rating Curve= 0
Exp/Cntr=.3,.1