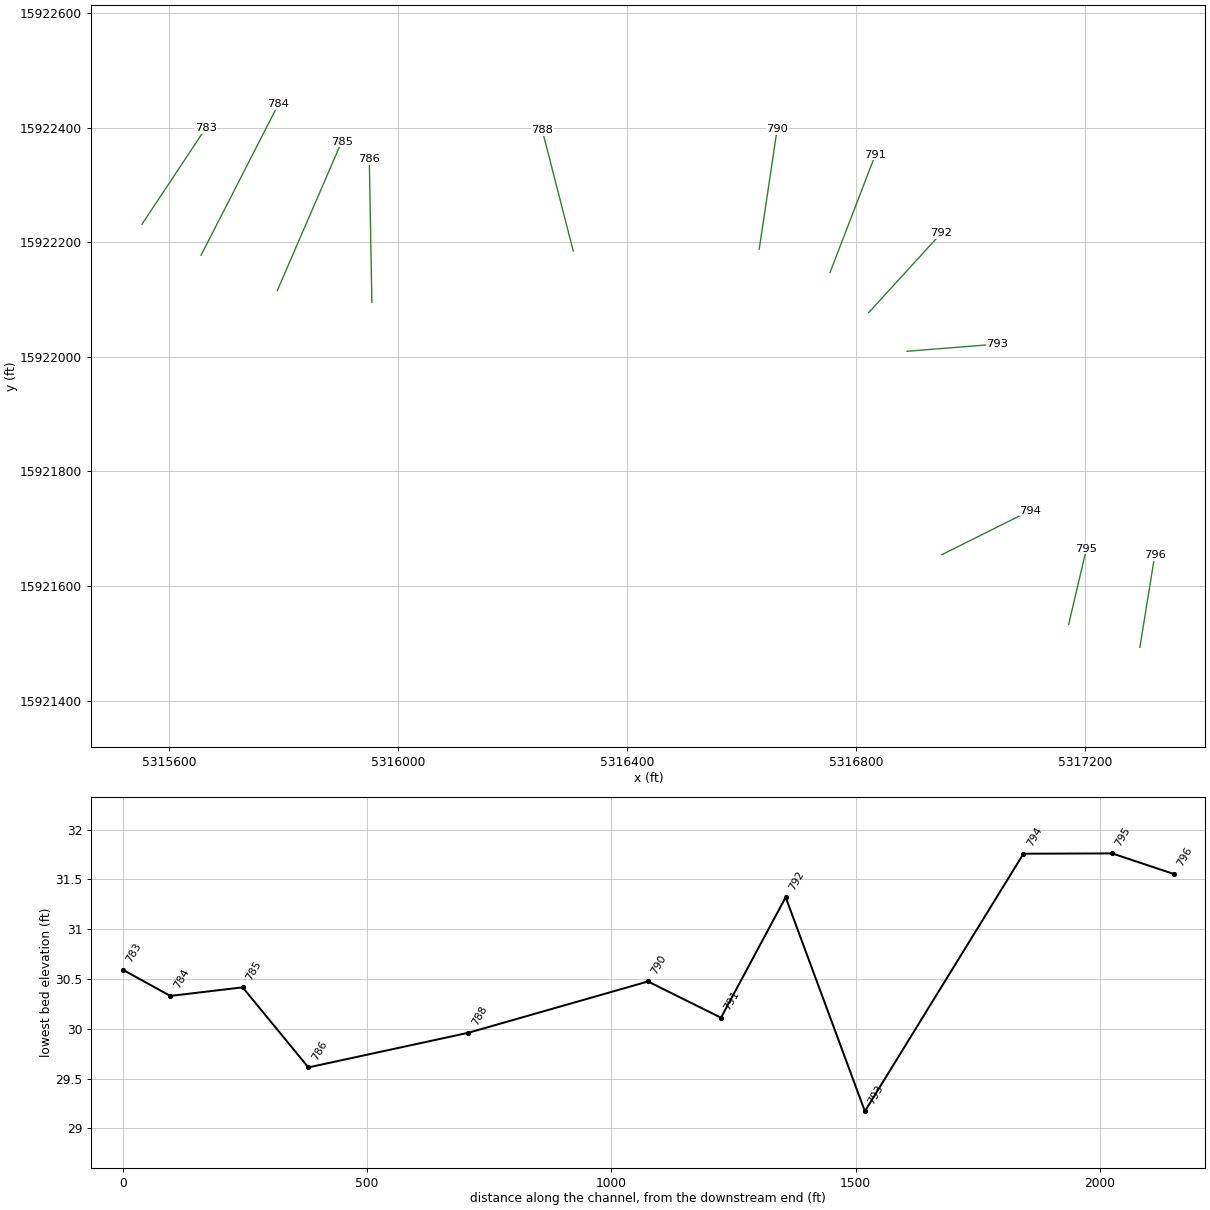
HEC-RAS study ozz_def.prj: ozzeri

--- ozz_def.g04 (geometry) --- (continued)

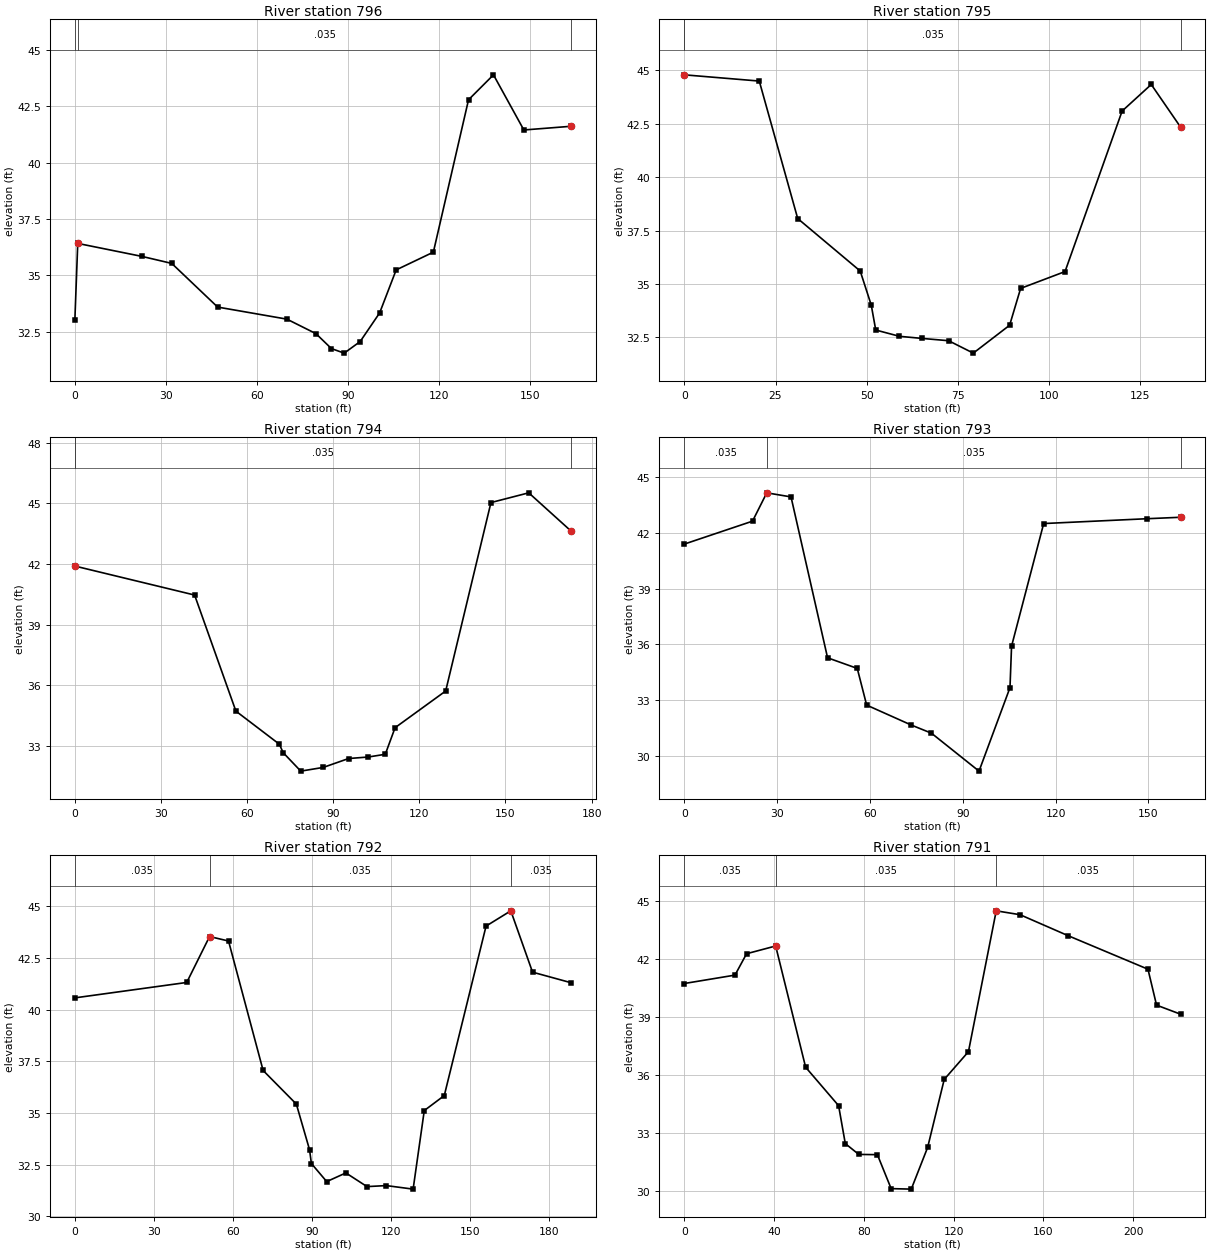
Type RM Length L Ch R = 1 ,796     ,126.345,126.345,126.345
XS GIS Cut Line= 2
      5317295.51     15921493.01      5317321.52     15921653.67
#Sta/Elev= 17
       0  33.018    .951  36.417  22.051  35.843  31.932  35.531  47.054  33.596
  69.885  33.061  79.459  32.418  84.567  31.755  88.776  31.555  94.039   32.07
 100.449  33.337 105.896  35.243 118.156   36.03 129.741  42.782 137.963  43.888
 147.976  41.444  163.57  41.608
#Mann= 3 , 0 , 0
       0    .035       0    .951    .035       0  163.57    .035       0
Bank Sta=.951,163.57
XS Rating Curve= 0
Exp/Cntr=.3,.1

Type RM Length L Ch R = 1 ,795     ,181.463,181.463,181.463
XS GIS Cut Line= 2
      5317171.19     15921533.14      5317202.26     15921665.35
#Sta/Elev= 16
       0  44.793  20.545  44.501  31.076  38.064  48.202  35.607  51.234  34.006
  52.457  32.844  58.963  32.549  65.141  32.451  72.425  32.343   79.19  31.762
  89.144  33.068  92.156  34.793 104.327  35.581 119.967  43.097 127.949  44.341
 135.991  42.343
#Mann= 3 , 0 , 0
       0    .035       0       0    .035       0 135.991    .035       0
Bank Sta=0,135.991
XS Rating Curve= 0
Exp/Cntr=.3,.1

Type RM Length L Ch R = 1 ,794     ,324.639,324.639,324.639
XS GIS Cut Line= 2
       5316949.7     15921654.69      5317104.13     15921731.63
#Sta/Elev= 15
       0  41.903  41.713  40.469  56.093  34.728   71.23  33.091  72.569  32.671
  78.694  31.759  86.509  31.942  95.351  32.382 102.182  32.457 108.133  32.592
 111.542  33.907 129.167  35.722 144.938  45.043 158.104  45.525 172.881  43.629
#Mann= 3 , 0 , 0
       0    .035       0       0    .035       0 172.881    .035       0
Bank Sta=0,172.881
XS Rating Curve= 0
Exp/Cntr=.3,.1

Type RM Length L Ch R = 1 ,793     ,162.106,162.106,162.106
XS GIS Cut Line= 3
      5316888.78     15922009.84      5317046.19     15922022.34
      5317046.19     15922022.34
#Sta/Elev= 15
       0  41.391  22.044  42.625   26.65   44.15  34.491   43.93  46.299  35.272
  55.892  34.701   58.93  32.726  73.297  31.657  79.872  31.214   95.24  29.173
 105.246  33.668 105.751  35.896 116.129  42.497 149.449  42.756 160.377  42.835
#Mann= 3 , 0 , 0
       0    .035       0   26.65    .035       0 160.377    .035       0
Bank Sta=26.65,160.377
XS Rating Curve= 0
Exp/Cntr=.3,.1

Type RM Length L Ch R = 1 ,792     ,132.415,132.415,132.415
XS GIS Cut Line= 3
      5316822.01     15922077.36      5316948.98     15922216.37
      5316948.98     15922216.37
#Sta/Elev= 19
       0  40.571  42.484  41.316  51.152  43.537  58.356   43.32  71.486   37.06
  84.108  35.433  89.114  33.228  89.823  32.559  95.636  31.686  102.91  32.106
 110.935  31.444 118.261  31.493 128.448  31.322  132.68  35.121 140.276  35.846
 156.142  44.042 165.541   44.78 173.793  41.814 188.458  41.302
#Mann= 3 , 0 , 0
       0    .035       0  51.152    .035       0 165.541    .035       0
Bank Sta=51.152,165.541
XS Rating Curve= 0
Exp/Cntr=.3,.1

Type RM Length L Ch R = 1 ,791     ,149.377,149.377,149.377
XS GIS Cut Line= 2
       5316754.4     15922147.38      5316833.73     15922353.35
#Sta/Elev= 20
       0  40.741  22.585  41.175   27.74   42.28  40.705   42.68  54.052  36.414
  68.743  34.426  71.719  32.467  77.733  31.906  86.027  31.893  92.146  30.138
 101.115  30.112 108.412   32.27 115.797  35.784 126.588  37.218  138.96  44.498
  149.56  44.298 170.948  43.215 206.562   41.48 210.381  39.623 221.096  39.154
#Mann= 3 , 0 , 0
       0    .035       0  40.705    .035       0  138.96    .035       0
Bank Sta=40.705,138.96
XS Rating Curve= 0
Exp/Cntr=.3,.1

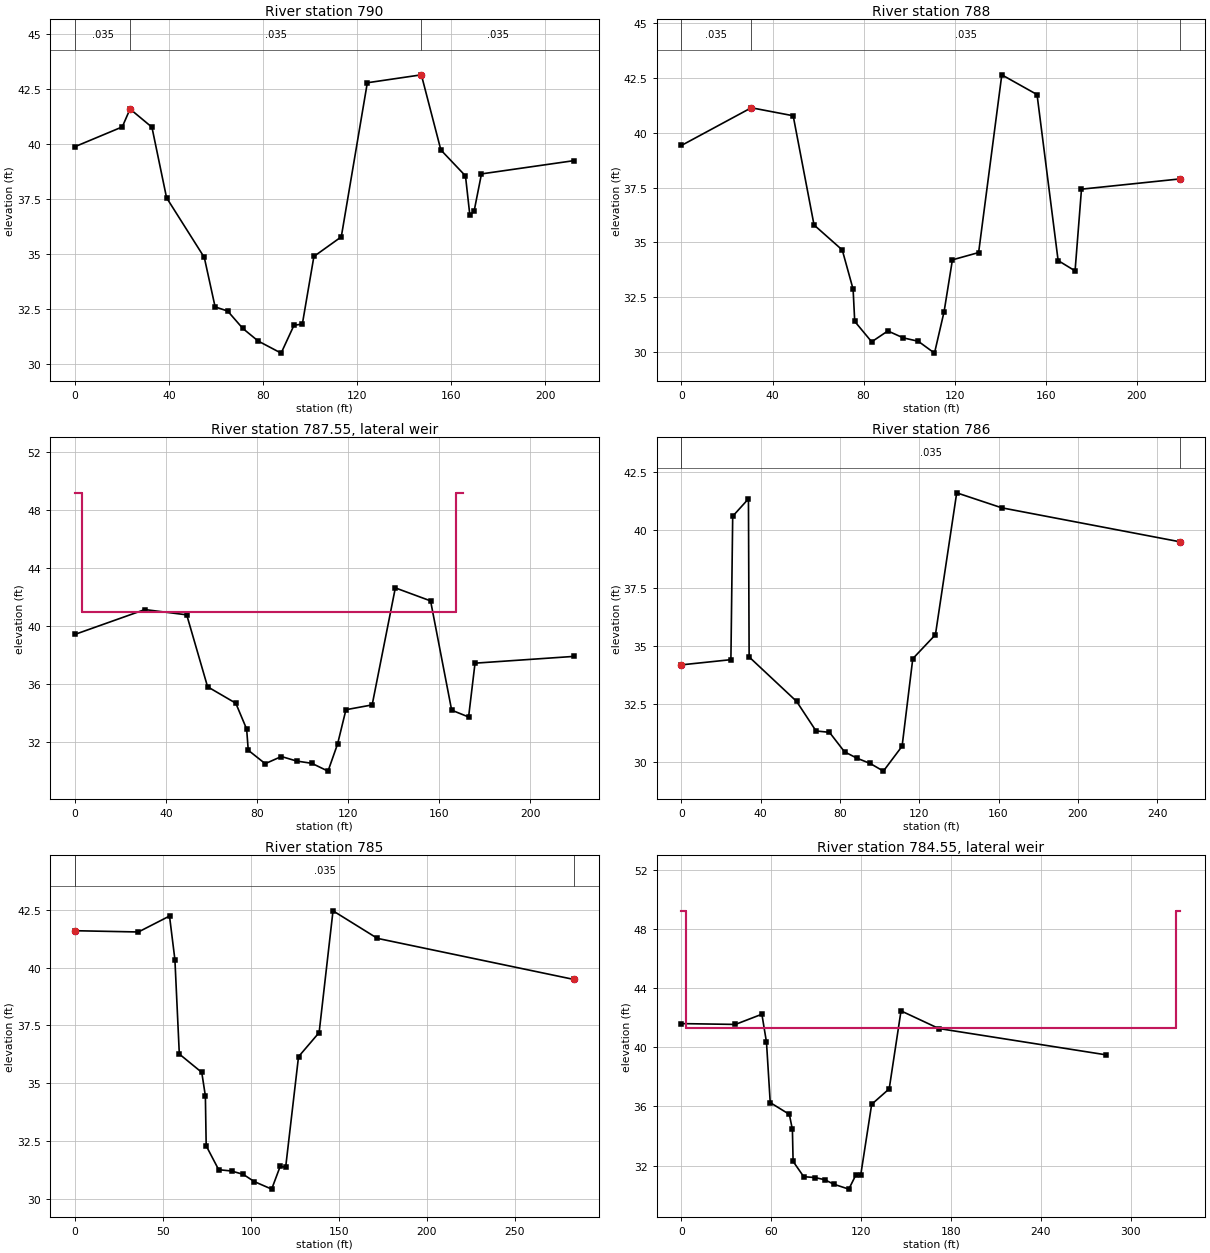
Type RM Length L Ch R = 1 ,790     ,367.552,367.552,367.552
XS GIS Cut Line= 3
      5316630.77     15922188.19      5316662.11     15922397.77
      5316662.11     15922397.77
#Sta/Elev= 23
       0  39.879  20.102  40.778  23.406  41.594   32.72  40.764  38.937  37.552
   54.98  34.833   59.58  32.582  64.918  32.392  71.348  31.601  77.877  31.027
  87.651  30.476  93.104  31.742  96.673  31.801 101.585  34.879 113.228  35.771
 124.298  42.789 147.274   43.15 155.568  39.728 166.033  38.547 167.884  36.768
 169.685  36.932 172.835  38.638 212.178  39.242
#Mann= 3 , 0 , 0
       0    .035       0  23.406    .035       0 147.274    .035       0
Bank Sta=23.406,147.274
XS Rating Curve= 0
Exp/Cntr=.3,.1

Type RM Length L Ch R = 1 ,788     ,327.559,327.559,327.559
XS GIS Cut Line= 2
        5316306.     15922184.88       5316251.8     15922396.29
#Sta/Elev= 21
       0  39.419  30.692  41.135  49.078  40.771  58.245  35.797   70.64  34.659
  75.407  32.871  76.112  31.407  83.563  30.476  90.669  30.971  97.441  30.656
 104.016  30.502 111.158  29.961 115.371  31.847 119.032  34.209 130.545  34.541
 140.728  42.635 156.211  41.736 165.469  34.177 172.913  33.707 175.735  37.428
 219.216  37.897
#Mann= 3 , 0 , 0
       0    .035       0  30.692    .035       0 219.216    .035       0
Bank Sta=30.692,219.216
XS Rating Curve= 0
Exp/Cntr=.3,.1

Type RM Length L Ch R = 6 ,787.55  ,,,
Lateral Weir Pos= 0
Lateral Weir End=                ,                ,        ,c20
Lateral Weir Distance=3.281
Lateral Weir WD=9.843
Lateral Weir Coef=3.01
Lateral Weir Is Ogee= 0
Lateral Weir WSCriteria=-1
Lateral Weir SE= 6
       0   49.21    3.28   49.21    3.28   40.98  167.32   40.98  167.32   49.21
   170.6   49.21

Type RM Length L Ch R = 1 ,786     ,134.58,134.58,134.58
XS GIS Cut Line= 3
       5315954.4     15922094.95       5315949.9     15922344.82
       5315949.9     15922344.82
#Sta/Elev= 18
       0  34.196  24.944  34.419  25.856  40.604  33.802  41.355  34.144  34.537
  58.087  32.621  67.897  31.345  74.682  31.286   82.27  30.446  88.635  30.167
  95.223  29.944 101.883  29.613 111.329  30.689 116.716  34.462  128.14  35.495
 138.881  41.614 161.591  40.968 251.775  39.498
#Mann= 3 , 0 , 0
       0    .035       0       0    .035       0 251.775    .035       0
Bank Sta=0,251.775
XS Rating Curve= 0
Exp/Cntr=.3,.1

Type RM Length L Ch R = 1 ,785     ,148.031,148.031,148.031
XS GIS Cut Line= 2
       5315789.3     15922115.98      5315901.74     15922375.95
#Sta/Elev= 20
       0  41.594  36.027  41.539  53.717  42.228  56.785  40.341  59.291   36.26
  72.051  35.466  74.101  34.446  74.564   32.29   81.66  31.257   88.95  31.201
   95.61  31.056 101.847  30.745 111.778  30.417 116.614  31.401 119.724  31.362
 127.037  36.145 138.747  37.188 146.637  42.454  171.85  41.263 283.596  39.485
#Mann= 3 , 0 , 0
       0    .035       0       0    .035       0 283.596    .035       0
Bank Sta=0,283.596
XS Rating Curve= 0
Exp/Cntr=.3,.1

Type RM Length L Ch R = 6 ,784.55  ,,,
Lateral Weir Pos= 0
Lateral Weir End=                ,                ,        ,c20
Lateral Weir Distance=3.281
Lateral Weir WD=9.843
Lateral Weir Coef=3.01
Lateral Weir Is Ogee= 0
Lateral Weir WSCriteria=-1
Lateral Weir SE= 6
       0   49.21    3.28   49.21    3.28   41.31     330   41.31     330   49.21
  333.28   49.21

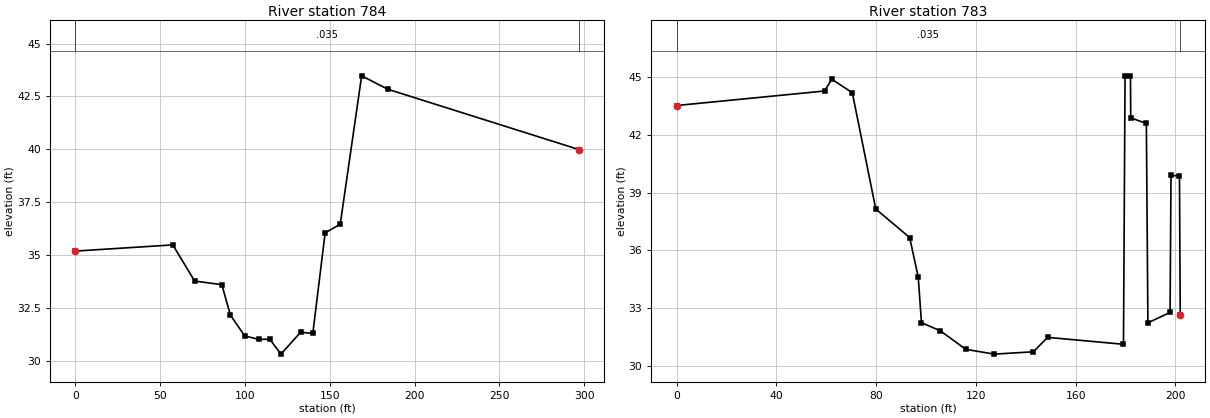
Type RM Length L Ch R = 1 ,784     ,97.146,97.146,97.146
XS GIS Cut Line= 3
      5315656.14     15922177.62      5315790.94     15922440.81
      5315790.94     15922440.81
#Sta/Elev= 16
       0  35.197  57.523  35.489  70.387  33.783  86.407  33.612   91.47  32.172
  99.859  31.194 108.159  31.027 114.656  31.037 121.247  30.331 132.815  31.362
 140.033  31.309 147.293   36.06 156.184  36.463 168.806  43.474 184.222  42.841
  296.85  39.993
#Mann= 3 , 0 , 0
       0    .035       0       0    .035       0  296.85    .035       0
Bank Sta=0,296.85
XS Rating Curve= 0
Exp/Cntr=.3,.1

Type RM Length L Ch R = 1 ,783     ,160.367,160.367,160.367
XS GIS Cut Line= 3
      5315552.85     15922231.53      5315663.94     15922399.05
      5315663.94     15922399.05
#Sta/Elev= 23
       0   43.53  59.324  44.285  62.238  44.898  70.453  44.196  79.859  38.143
  93.451   36.66  96.886  34.596  98.179  32.228 105.676  31.811 115.968  30.843
 127.369  30.594 143.041  30.715 148.734  31.467  179.16  31.106 179.797  45.075
 181.962  45.043 182.073   42.89 188.337  42.595 188.953  32.221 197.838  32.766
 198.215  39.908 201.611  39.846 201.913  32.644
#Mann= 3 , 0 , 0
       0    .035       0       0    .035       0 201.913    .035       0
Bank Sta=0,201.913
XS Rating Curve= 0
Exp/Cntr=.3,.1