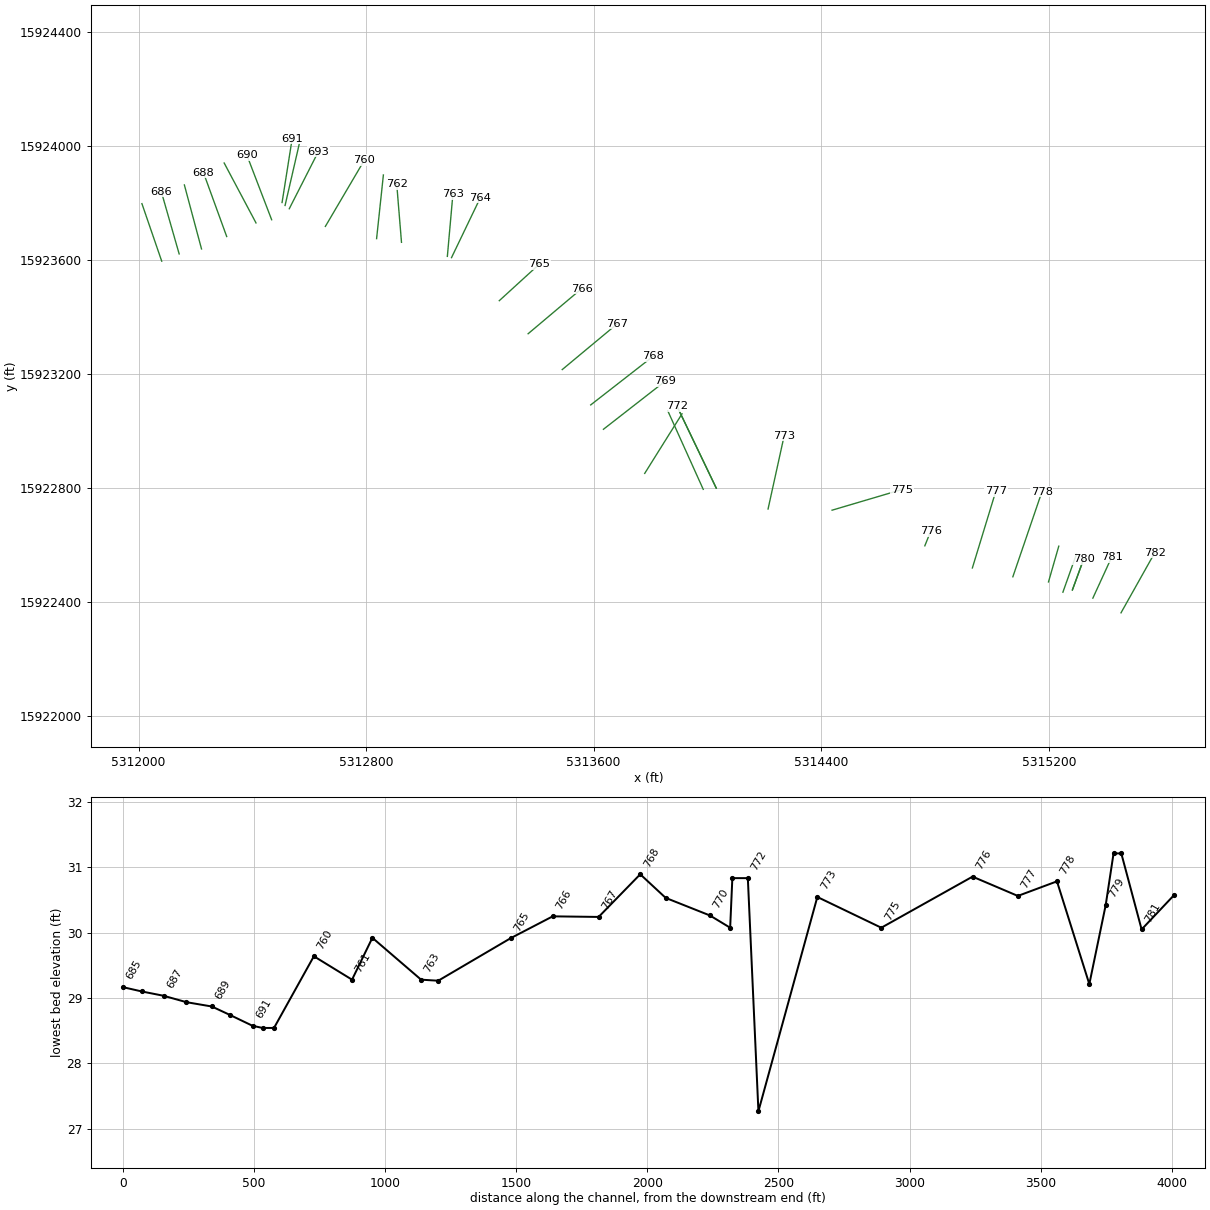
HEC-RAS study ozz_def.prj: ozzeri

--- ozz_def.g04 (geometry) --- (continued)

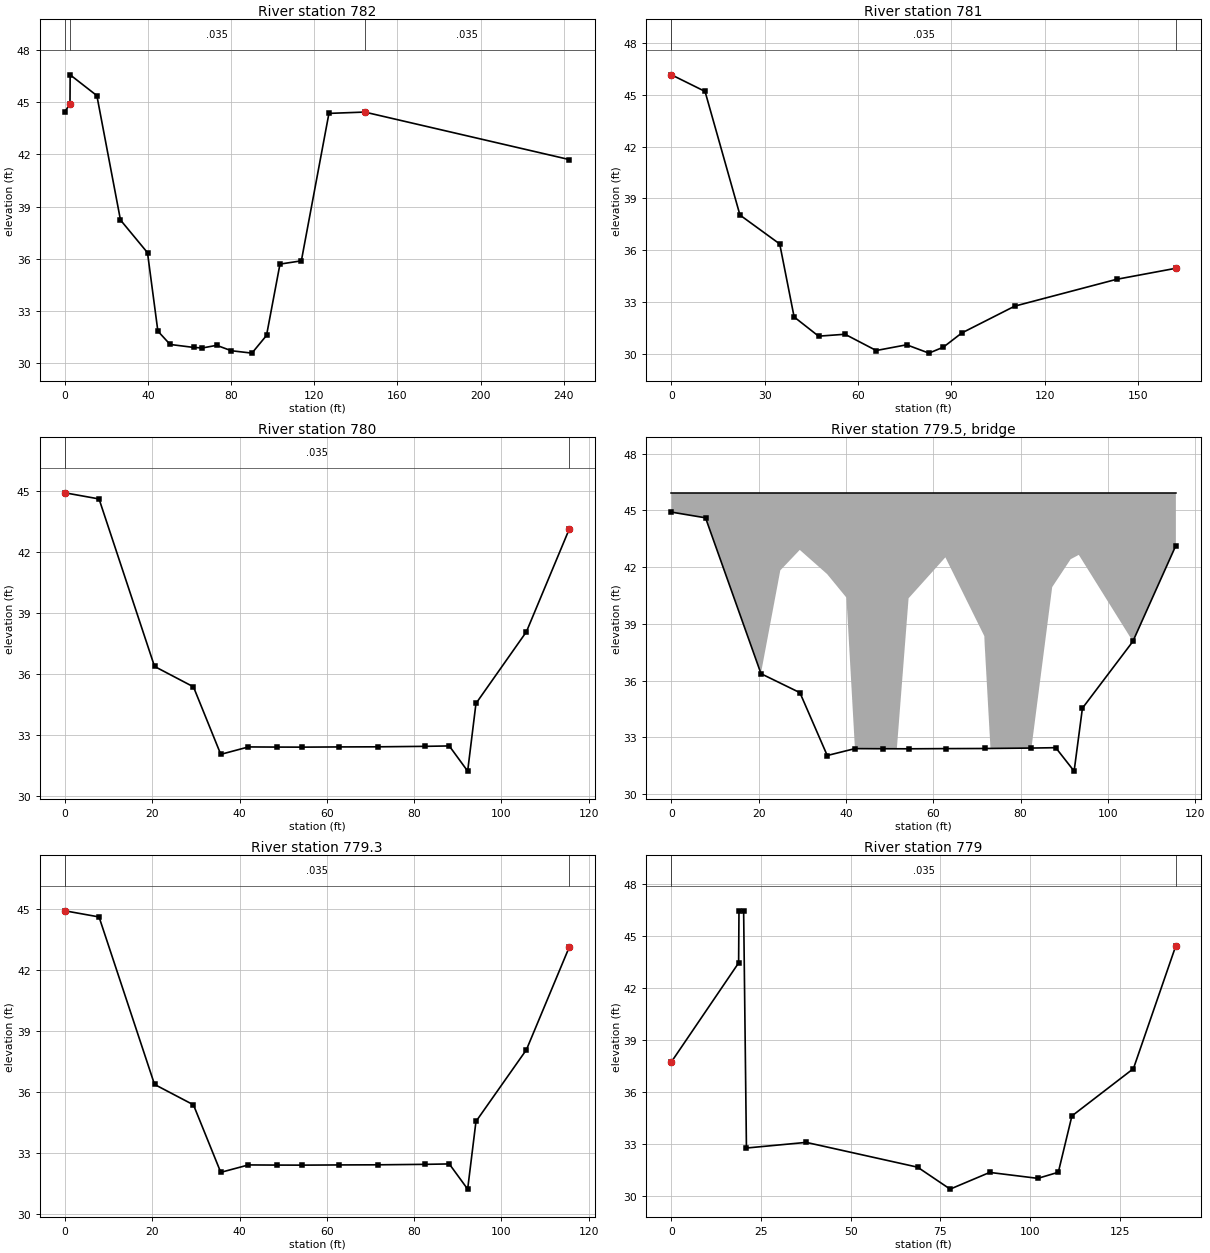
Type RM Length L Ch R = 1 ,782     ,123.031,123.031,123.031
XS GIS Cut Line= 3
      5315453.94      15922360.7      5315572.64     15922571.92
      5315572.64     15922571.92
#Sta/Elev= 19
       0  44.455   2.395  44.921    2.48  46.578  15.335  45.381  26.693  38.228
  39.701  36.348  44.692  31.837  50.577   31.07  62.106  30.896  66.135  30.869
  73.002   31.02  80.036  30.709  89.961  30.571  96.982  31.588 103.458  35.692
  113.75  35.879 127.024   44.36 144.249  44.436 242.756  41.703
#Mann= 3 , 0 , 0
       0    .035       0   2.395    .035       0 144.249    .035       0
Bank Sta=2.395,144.249
XS Rating Curve= 0
Exp/Cntr=.3,.1

Type RM Length L Ch R = 1 ,781     ,77.493,77.493,77.493
XS GIS Cut Line= 2
      5315354.92      15922412.2      5315421.33     15922556.76
#Sta/Elev= 15
       0  46.158  10.781  45.197  22.008  38.041   34.79  36.368  39.419  32.142
  47.283   31.03  55.774  31.142  65.804    30.2  75.591  30.531  82.749  30.049
  87.385  30.394  93.297  31.214 110.328  32.769 143.058  34.321 162.129  34.961
#Mann= 3 , 0 , 0
       0    .035       0       0    .035       0 162.129    .035       0
Bank Sta=0,162.129
XS Rating Curve= 0
Exp/Cntr=.3,.1

Type RM Length L Ch R = 1 ,780     ,29.528,29.528,29.528
XS GIS Cut Line= 2
      5315283.07     15922441.17      5315322.51     15922548.92
#Sta/Elev= 16
       0  44.911   7.799   44.61  20.512  36.365  29.429  35.361  35.689  32.037
  42.037  32.402   48.55  32.395  54.377  32.392  62.828  32.402  71.772  32.408
   82.48  32.431  88.051  32.451  92.264  31.211  94.167  34.541 105.725  38.071
 115.577  43.143
#Mann= 3 , 0 , 0
       0    .035       0       0    .035       0 115.577    .035       0
Bank Sta=0,115.577
XS Rating Curve= 0
Exp/Cntr=.3,.1

Type RM Length L Ch R = 3 ,779.5   ,,,
BEGIN DESCRIPTION:
Ponte di Pontetetto
END DESCRIPTION:
Bridge Culvert--1,0,-1,-1, 0
Deck Dist Width WeirC Skew NumUp NumDn MinLoCord MaxHiCord MaxSubmerge Is_Ogee
1.64,26.247,2.61,0, 19, 19, , , .95, 0, 0,0,,
       0   7.776  20.472  24.934  29.396  35.663  40.092  42.159   51.64  54.331
  62.762  71.686  73.097  82.349  87.238   91.47   93.34 105.741 115.584
  45.932  45.932  45.932  45.932  45.932  45.932  45.932  45.932  45.932  45.932
  45.932  45.932  45.932  45.932  45.932  45.932  45.932  45.932  45.932
  44.915  44.619  36.352  41.831  42.913  41.634  40.387  31.234  30.741  40.354
   42.52  38.353  30.741  30.512  40.945  42.421  42.651  38.058  43.143
       0   7.776  20.472  24.934  29.396  35.663  40.092  42.159   51.64  54.331
  62.762  71.686  73.097  82.349  87.238   91.47   93.34 105.741 115.584
  45.932  45.932  45.932  45.932  45.932  45.932  45.932  45.932  45.932  45.932
  45.932  45.932  45.932  45.932  45.932  45.932  45.932  45.932  45.932
  44.915  44.619  36.352  41.831  42.913  41.634  40.387  31.234  30.741  40.354
   42.52  38.353  30.741  30.512  40.945  42.421  42.651  38.058  43.143
BR Coef=-1 , 0 , 0 ,1.25, 0 ,,,.8,-1,2,0,
WSPro=,,,, 1 ,,,, 0 ,,,, 0 ,,,,-1 ,-1 ,-1 , 0 , 0 , 0 , 0 , 0
BC Design=,, 0 ,, 0 ,,,,,,
BC HTab Sub Flow Pts= 40

Type RM Length L Ch R = 1 ,779.3   ,29.856,29.856,29.856
XS GIS Cut Line= 2
      5315283.07     15922441.17      5315322.51     15922548.92
#Sta/Elev= 16
       0  44.911   7.799   44.61  20.512  36.365  29.429  35.361  35.689  32.037
  42.037  32.402   48.55  32.395  54.377  32.392  62.828  32.402  71.772  32.408
   82.48  32.431  88.051  32.451  92.264  31.211  94.167  34.541 105.725  38.071
 115.577  43.143
#Mann= 3 , 0 , 0
       0    .035       0       0    .035       0 115.577    .035       0
Bank Sta=0,115.577
XS Rating Curve= 0
Exp/Cntr=.3,.1

Type RM Length L Ch R = 1 ,779     ,62.566,62.566,62.566
XS GIS Cut Line= 3
      5315249.61      15922433.1      5315296.72     15922565.12
      5315296.72     15922565.12
#Sta/Elev= 14
       0  37.756   18.72  43.445  18.819  46.427  20.118  46.444  20.899  32.789
  37.572  33.114  68.642  31.686  77.703  30.423   88.74  31.385 102.159  31.043
 107.874  31.394  111.66  34.636 128.816  37.359 140.656  44.442
#Mann= 3 , 0 , 0
       0    .035       0       0    .035       0 140.656    .035       0
Bank Sta=0,140.656
XS Rating Curve= 0
Exp/Cntr=.3,.1

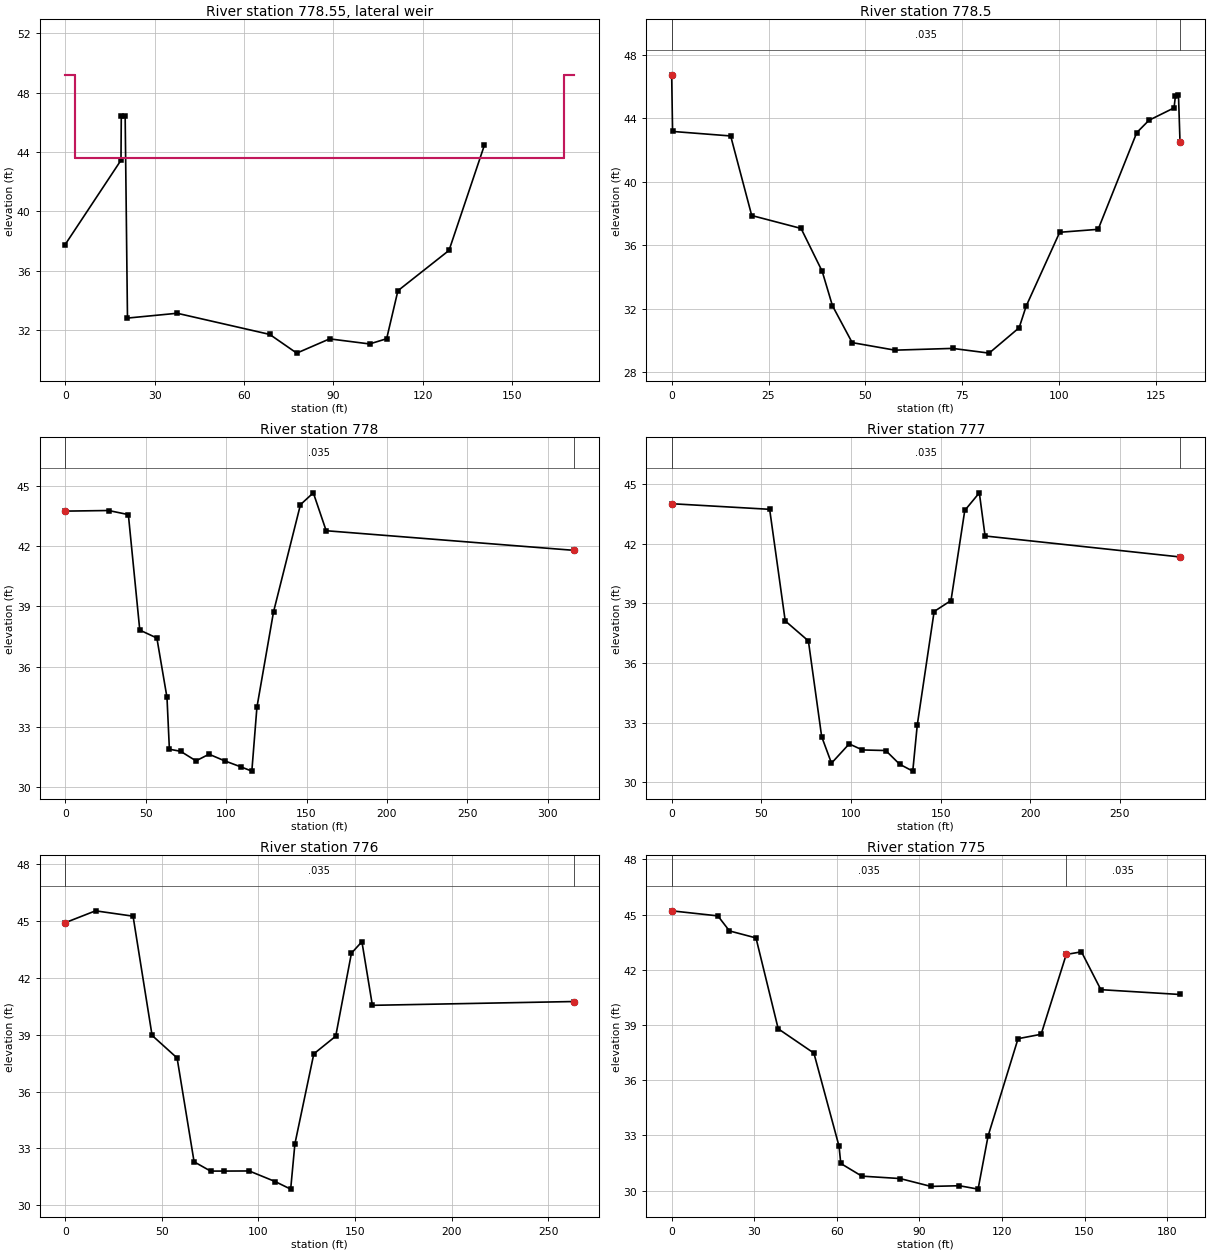
Type RM Length L Ch R = 6 ,778.55  ,,,
Lateral Weir Pos= 0
Lateral Weir End=                ,                ,        ,c14
Lateral Weir Distance=3.281
Lateral Weir WD=9.843
Lateral Weir Coef=3.01
Lateral Weir Is Ogee= 0
Lateral Weir WSCriteria=-1
Lateral Weir SE= 6
       0   49.21    3.28   49.21    3.28   43.61  167.32   43.61  167.32   49.21
   170.6   49.21

Type RM Length L Ch R = 1 ,778.5   ,123.392,123.392,123.392
XS GIS Cut Line= 2
      5315198.98     15922469.23      5315235.14     15922594.82
#Sta/Elev= 21
       0  46.749     .23  43.182  15.226  42.897  20.659  37.884  33.396   37.07
  38.845   34.37  41.493  32.201  46.588  29.875  57.618    29.4  72.503  29.511
  81.936  29.213  89.688  30.814  91.486  32.169 100.148  36.827 110.075  37.014
 120.036  43.107 123.189  43.885 129.665  44.665  130.03  45.443 130.807  45.479
 131.201  42.543
#Mann= 3 , 0 , 0
       0    .035       0       0    .035       0 131.201    .035       0
Bank Sta=0,131.201
XS Rating Curve= 0
Exp/Cntr=.3,.1

Type RM Length L Ch R = 1 ,778     ,149.18,149.18,149.18
XS GIS Cut Line= 2
      5315073.69     15922487.24      5315175.89     15922785.96
#Sta/Elev= 19
       0   43.75  26.972   43.78  39.252  43.576  46.345  37.818  56.972  37.421
  63.255  34.459  64.754  31.877  71.739  31.772  81.283  31.296  89.383  31.627
   99.14  31.296 109.452  30.988 115.997  30.784  119.16   33.97 129.465   38.72
 146.214  44.072 154.213  44.662 162.198  42.772 315.945  41.795
#Mann= 3 , 0 , 0
       0    .035       0       0    .035       0 315.945    .035       0
Bank Sta=0,315.945
XS Rating Curve= 0
Exp/Cntr=.3,.1

Type RM Length L Ch R = 1 ,777     ,172.736,172.736,172.736
XS GIS Cut Line= 2
       5314931.4     15922518.31      5315014.07     15922788.75
#Sta/Elev= 18
       0  44.022  54.639   43.74  63.317  38.123   76.24  37.116  83.642  32.297
  89.117  30.961  98.993  31.932 106.355  31.627  119.37  31.598 127.119  30.909
 134.442  30.561 136.965   32.89 146.358  38.596 155.758  39.147 163.445  43.684
 171.565   44.57  174.76  42.398 283.465  41.342
#Mann= 3 , 0 , 0
       0    .035       0       0    .035       0 283.465    .035       0
Bank Sta=0,283.465
XS Rating Curve= 0
Exp/Cntr=.3,.1

Type RM Length L Ch R = 1 ,776     ,347.966,347.966,347.966
XS GIS Cut Line= 2
      5314764.24     15922596.03      5314784.71     15922646.82
#Sta/Elev= 18
       0  44.905  15.689  45.531  35.108  45.249  44.938  38.963  57.884  37.772
  66.677  32.297   75.19  31.808  82.152  31.808  95.197  31.814 108.579  31.257
  116.65  30.856 118.839  33.245 128.619  37.989 139.951  38.921 148.084  43.297
 153.504  43.904 158.917  40.548 262.992  40.748
#Mann= 3 , 0 , 0
       0    .035       0       0    .035       0 262.992    .035       0
Bank Sta=0,262.992
XS Rating Curve= 0
Exp/Cntr=.3,.1

Type RM Length L Ch R = 1 ,775     ,243.898,243.898,243.898
XS GIS Cut Line= 3
      5314438.16     15922721.19      5314683.89      15922793.8
      5314683.89      15922793.8
#Sta/Elev= 20
       0    45.2  16.778  44.925  20.994  44.108  30.633  43.727  38.704  38.789
   51.67  37.467  60.807  32.405  61.434   31.47  69.075  30.781  82.976   30.65
  94.186  30.223 104.547  30.259 111.325  30.075 114.957  32.963 125.843  38.251
 134.229  38.491 143.353  42.828 148.878  42.972 155.925  40.915 184.682  40.653
#Mann= 3 , 0 , 0
       0    .035       0       0    .035       0 143.353    .035       0
Bank Sta=0,143.353
XS Rating Curve= 0
Exp/Cntr=.3,.1

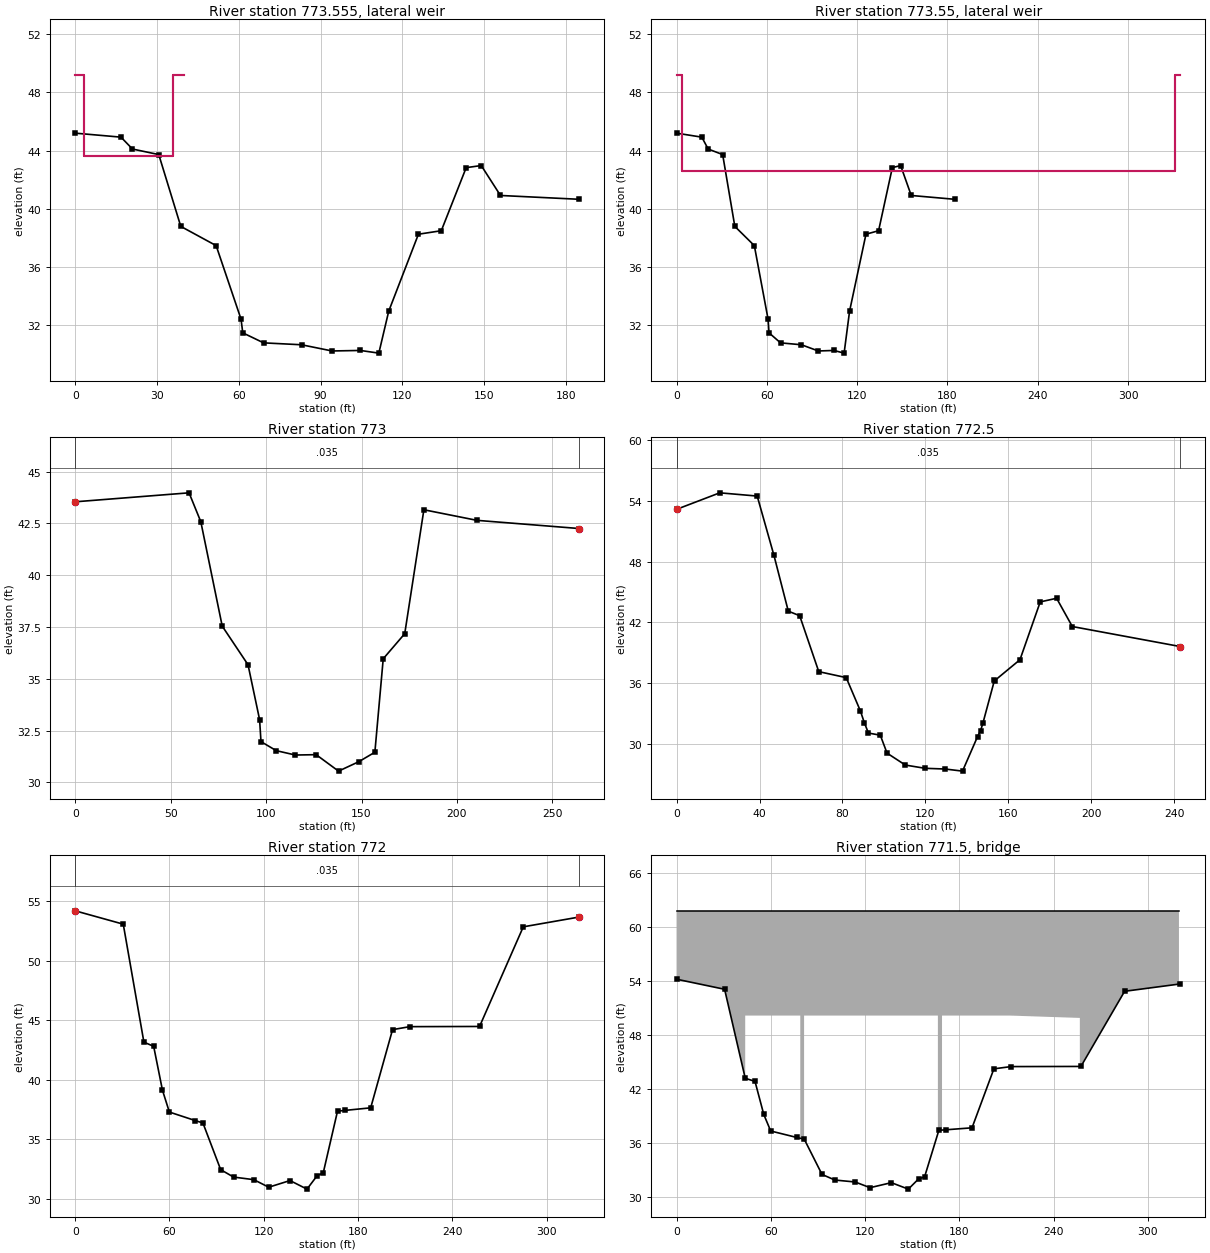
Type RM Length L Ch R = 6 ,773.555 ,,,
Lateral Weir Pos= 0
Lateral Weir End=                ,                ,        ,c12
Lateral Weir Distance=3.281
Lateral Weir WD=9.843
Lateral Weir Coef=3.01
Lateral Weir Is Ogee= 0
Lateral Weir WSCriteria=-1
Lateral Weir SE= 6
       0   49.21    3.28   49.21    3.28   43.61      36   43.61      36   49.21
      40   49.21

Type RM Length L Ch R = 6 ,773.55  ,,,
Lateral Weir Pos= 3
Lateral Weir End=                ,                ,        ,c11
Lateral Weir Distance=3.281
Lateral Weir WD=9.843
Lateral Weir Coef=3.01
Lateral Weir Is Ogee= 0
Lateral Weir WSCriteria=-1
Lateral Weir SE= 6
       0   49.21    3.28   49.21    3.28   42.62  331.37   42.62  331.37   49.21
  334.65   49.21

Type RM Length L Ch R = 1 ,773     ,224.705,224.705,224.705
XS GIS Cut Line= 3
      5314213.12     15922725.43      5314269.85     15922983.07
      5314269.85     15922983.07
#Sta/Elev= 18
       0  43.543  59.633  43.976  65.797  42.579  77.008  37.543  90.525  35.679
  96.588  33.031  97.313  31.969 105.348  31.532 115.344  31.322  126.22  31.339
 137.946  30.545 148.583  31.001 156.975  31.457 161.355  35.968 172.621  37.178
 182.651  43.159 210.443  42.648 263.858  42.254
#Mann= 3 , 0 , 0
       0    .035       0       0    .035       0 263.858    .035       0
Bank Sta=0,263.858
XS Rating Curve= 0
Exp/Cntr=.3,.1

Type RM Length L Ch R = 1 ,772.5   ,40.354,40.354,40.354
#Sta/Elev= 27
       0  53.169   20.83  54.803  38.891  54.482  46.955  48.625  53.888  43.097
  59.383  42.644  68.583  37.113  81.821  36.522  88.671  33.219  90.577  32.051
  92.539  31.037  98.255  30.827 101.516  29.052 110.325  27.871 119.879  27.549
 129.662  27.477 137.917   27.27 145.144  30.676 146.631   31.27 147.776  32.037
 153.333  36.266 153.445  36.227 165.623  38.291 175.397  44.012 183.301   44.37
 190.876  41.575 242.923  39.596
#Mann= 3 , 0 , 0
       0    .035       0       0    .035       0 242.923    .035       0
Bank Sta=0,242.923
XS Rating Curve= 0
Exp/Cntr=.3,.1

Type RM Length L Ch R = 1 ,772     ,59.055,59.055,59.055
XS GIS Cut Line= 2
      5314030.94     15922798.72      5313892.55     15923087.04
#Sta/Elev= 24
       0  54.173  30.574  53.054  43.714  43.159  49.928  42.812  55.515  39.134
  59.918  37.297  76.444  36.581  81.286  36.381  92.579  32.467 100.778  31.844
 113.668  31.627 123.176  30.994 136.713  31.552 147.523  30.833 154.006  31.962
 157.871  32.198 166.952  37.372 171.624  37.434 188.068  37.651 201.982  44.209
 212.966  44.459 257.375  44.475 285.197  52.831 320.597  53.648
#Mann= 3 , 0 , 0
       0    .035       0       0    .035       0 320.597    .035       0
Bank Sta=0,320.597
XS Rating Curve= 0
Exp/Cntr=.3,.1

Type RM Length L Ch R = 3 ,771.5   ,,,
BEGIN DESCRIPTION:
Bretellina
END DESCRIPTION:
Bridge Culvert--1,0,-1,-1, 0
Deck Dist Width WeirC Skew NumUp NumDn MinLoCord MaxHiCord MaxSubmerge Is_Ogee
1.64,55.774,2.61,0, 30, 30, , , .95, 0, 0,0,,
       0  30.545  43.701  43.701  49.869  55.479  59.744   78.74   78.74  81.168
  81.168  92.388 100.525 113.386   122.9  136.45 147.244 153.707 157.513 166.339
 166.339 168.963 168.963 187.533 201.411 212.336 256.693 256.693 284.416 319.783
  61.778  61.778  61.778  61.778  61.778  61.778  61.778  61.778  61.778  61.778
  61.778  61.778  61.778  61.778  61.778  61.778  61.778  61.778  61.778  61.778
  61.778  61.778  61.778  61.778  61.778  61.778  61.778  61.778  61.778  61.778
  54.167  53.051  43.143  50.131  50.131  50.131  50.131  50.131  36.319  36.352
  50.131  50.131  50.131  50.131  50.131  50.131  50.131  50.131  50.131  50.131
  37.467  37.402  50.131  50.131  50.131  50.131  49.869  44.488  50.131  50.131
       0  30.545  43.701  43.701  49.869  55.479  59.744   78.74   78.74  81.168
  81.168  92.388 100.525 113.386   122.9  136.45 147.244 153.707 157.513 166.339
 166.339 168.963 168.963 187.533 201.411 212.336 256.693 256.693 284.416 319.783
  61.778  61.778  61.778  61.778  61.778  61.778  61.778  61.778  61.778  61.778
  61.778  61.778  61.778  61.778  61.778  61.778  61.778  61.778  61.778  61.778
  61.778  61.778  61.778  61.778  61.778  61.778  61.778  61.778  61.778  61.778
  54.167  53.051  43.143  50.131  50.131  50.131  50.131  50.131  36.319  36.352
  50.131  50.131  50.131  50.131  50.131  50.131  50.131  50.131  50.131  50.131
  37.467  37.402  50.131  50.131  50.131  50.131  49.869  44.488  50.131  50.131
BR Coef=-1 , 0 , 0 ,1.25, 0 ,,,.8,-1,2,0,
WSPro=,,,, 1 ,,,, 0 ,,,, 0 ,,,,-1 ,-1 ,-1 , 0 , 0 , 0 , 0 , 0
BC Design=,, 0 ,, 0 ,,,,,,
BC HTab Sub Flow Pts= 40

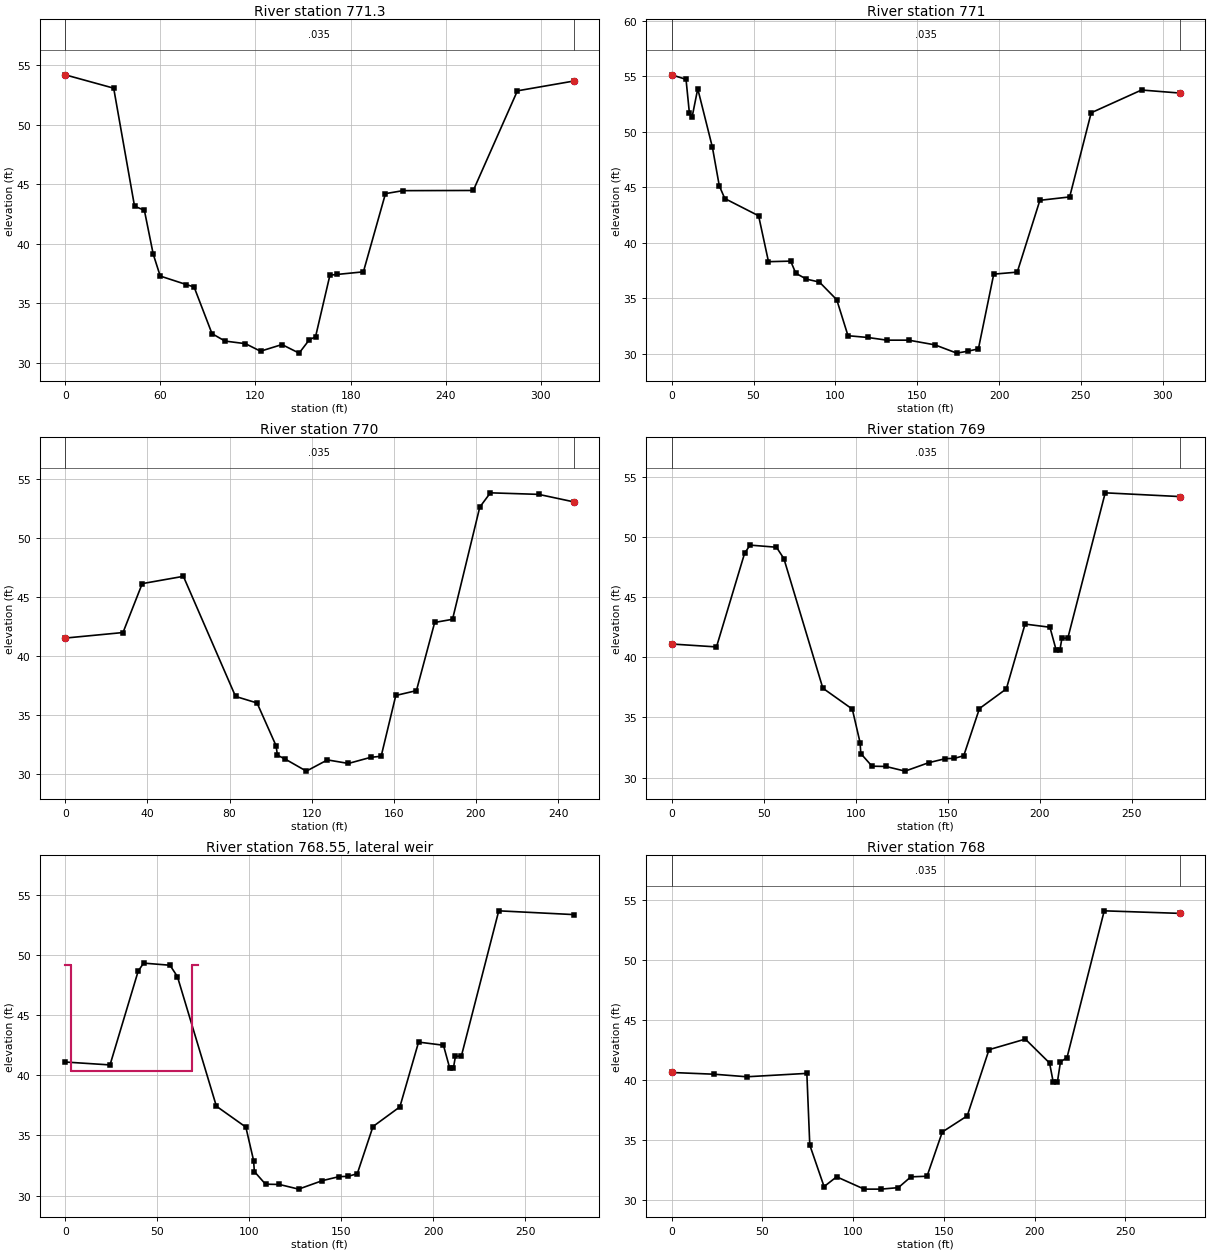
Type RM Length L Ch R = 1 ,771.3   ,8.333,8.333,8.333
XS GIS Cut Line= 2
      5314030.94     15922798.72      5313892.55     15923087.04
#Sta/Elev= 24
       0  54.173  30.574  53.054  43.714  43.159  49.928  42.812  55.515  39.134
  59.918  37.297  76.444  36.581  81.286  36.381  92.579  32.467 100.778  31.844
 113.668  31.627 123.176  30.994 136.713  31.552 147.523  30.833 154.006  31.962
 157.871  32.198 166.952  37.372 171.624  37.434 188.068  37.651 201.982  44.209
 212.966  44.459 257.375  44.475 285.197  52.831 320.597  53.648
#Mann= 3 , 0 , 0
       0    .035       0       0    .035       0 320.597    .035       0
Bank Sta=0,320.597
XS Rating Curve= 0
Exp/Cntr=.3,.1

Type RM Length L Ch R = 1 ,771     ,76.936,76.936,76.936
XS GIS Cut Line= 2
       5313985.2     15922794.42       5313860.4      15923070.6
#Sta/Elev= 30
       0  55.148    8.77  54.738   10.81  51.722  12.493  51.355  15.925  53.891
  24.885  48.615  29.081  45.151  32.441  44.003    53.1  42.448  59.137  38.314
  72.694  38.363  75.814   37.27   82.31  36.742  90.259  36.476  100.84  34.882
   107.7  31.644 119.721  31.486 131.453  31.243 144.767  31.243 160.801   30.82
 174.131  30.075 180.889  30.249 187.359  30.459 196.726  37.192 211.083  37.372
 224.911  43.842 243.104  44.147 256.253  51.729 287.008   53.78 310.499  53.504
#Mann= 3 , 0 , 0
       0    .035       0       0    .035       0 310.499    .035       0
Bank Sta=0,310.499
XS Rating Curve= 0
Exp/Cntr=.3,.1

Type RM Length L Ch R = 1 ,770     ,168.898,168.898,168.898
XS GIS Cut Line= 2
      5313779.49     15922850.39      5313910.66     15923059.74
#Sta/Elev= 22
       0  41.516  28.143  41.985  37.497  46.122  57.536  46.739   82.94  36.581
  93.406  36.027 102.677  32.405 103.314  31.611 107.228   31.27 117.405  30.262
 127.674  31.211   137.9  30.912 148.789   31.43 153.832  31.519 160.965  36.663
 171.007   37.07 179.892  42.838 188.583  43.104  201.85  52.592 207.011  53.802
 230.538  53.671   247.5  53.041
#Mann= 3 , 0 , 0
       0    .035       0       0    .035       0   247.5    .035       0
Bank Sta=0,247.5
XS Rating Curve= 0
Exp/Cntr=.3,.1

Type RM Length L Ch R = 1 ,769     ,97.113,97.113,97.113
XS GIS Cut Line= 2
      5313634.38     15923005.38      5313851.97     15923174.77
#Sta/Elev= 27
       0  41.102   24.36   40.86  39.672  48.661  42.631  49.327  56.962   49.15
  61.001  48.205  82.182  37.428  98.196  35.689 102.421  32.907 102.818  31.995
 108.888  30.942 116.424  30.919 126.893  30.531 139.751  31.234 148.812  31.568
 153.743  31.594 158.783  31.814 167.313  35.735 181.939  37.372 192.106  42.759
  205.63  42.497 208.944  40.643 211.079  40.633 212.149  41.572 215.377  41.601
 235.692  53.675 276.345  53.363
#Mann= 3 , 0 , 0
       0    .035       0       0    .035       0 276.345    .035       0
Bank Sta=0,276.345
XS Rating Curve= 0
Exp/Cntr=.3,.1

Type RM Length L Ch R = 6 ,768.55  ,,,
Lateral Weir Pos= 0
Lateral Weir End=                ,                ,        ,c10
Lateral Weir Distance=3.281
Lateral Weir WD=9.843
Lateral Weir Coef=3.01
Lateral Weir Is Ogee= 0
Lateral Weir WSCriteria=-1
Lateral Weir SE= 6
       0   49.21    3.28   49.21    3.28   40.33    68.9   40.33    68.9   49.21
      72   49.21

Type RM Length L Ch R = 1 ,768     ,158.629,158.629,158.629
XS GIS Cut Line= 3
      5313589.63     15923090.91      5313809.45     15923261.98
      5313809.48     15923262.01
#Sta/Elev= 23
       0   40.61  23.314  40.466  41.417  40.253  74.472  40.535  76.089  34.564
   83.96  31.102  90.886  31.919  106.06  30.892 115.459  30.892 124.888  31.017
 131.775  31.916 140.676  31.965 149.098  35.653 162.835  36.995 174.833   42.51
 194.833  43.392 208.199  41.398 210.167  39.839 212.539  39.849 214.203  41.496
 217.795  41.847  238.31  54.078 280.052  53.865
#Mann= 3 , 0 , 0
       0    .035       0       0    .035       0 280.052    .035       0
Bank Sta=0,280.052
XS Rating Curve= 0
Exp/Cntr=.3,.1

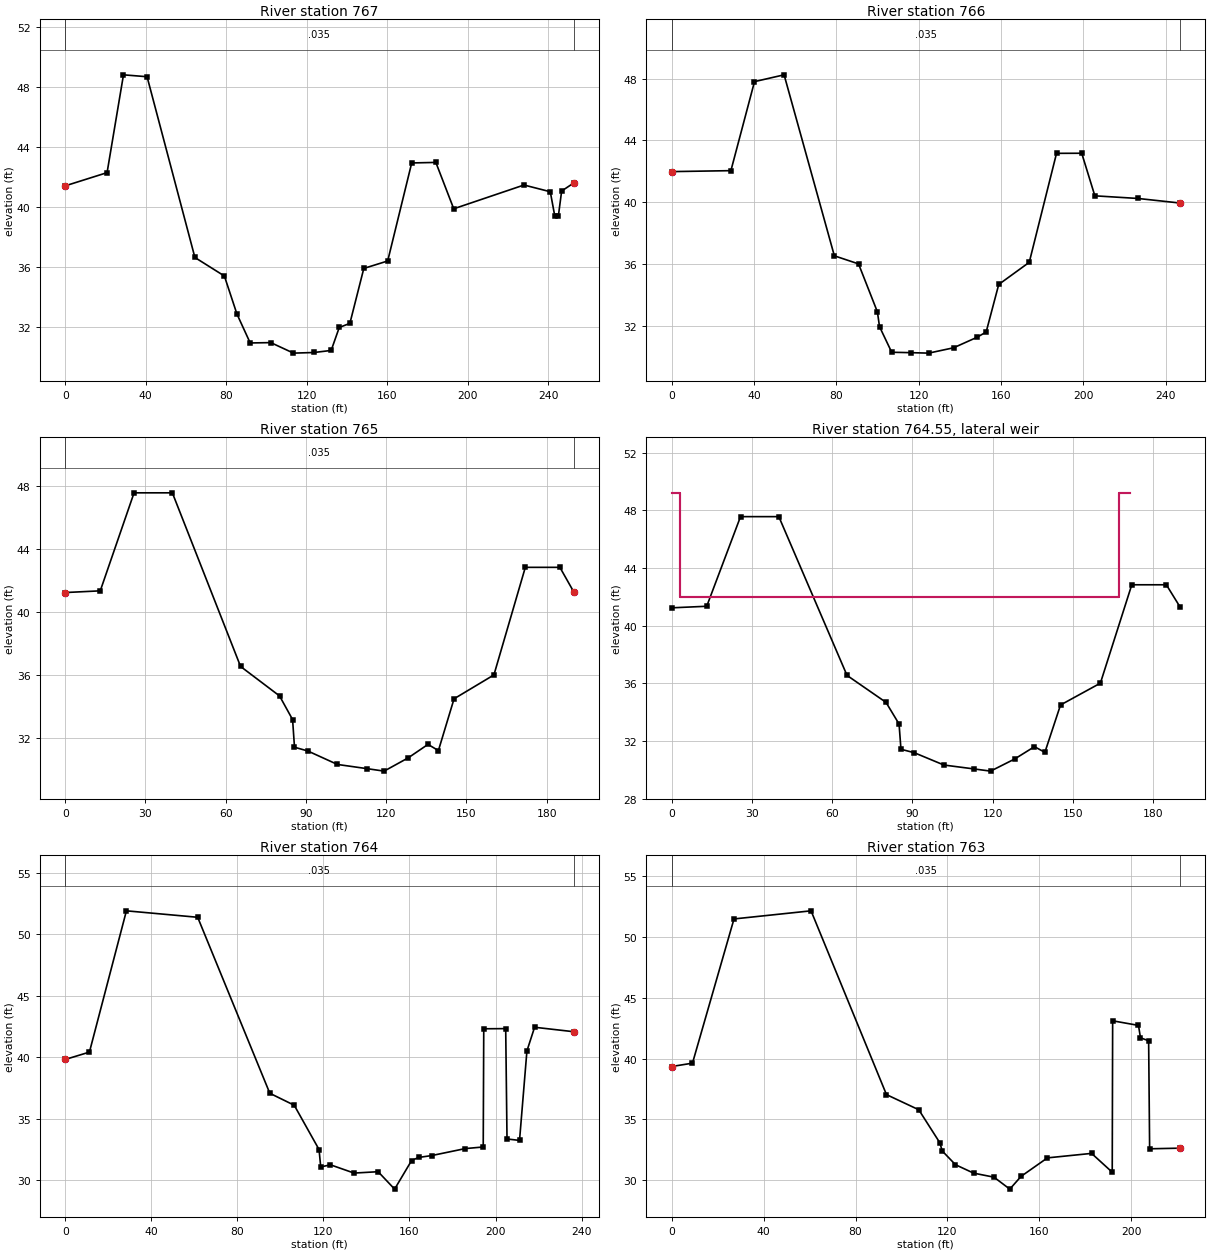
Type RM Length L Ch R = 1 ,767     ,175.098,175.098,175.098
XS GIS Cut Line= 3
       5313489.6     15923215.12      5313683.17     15923375.98
      5313683.17     15923375.98
#Sta/Elev= 25
       0  41.411  20.797  42.293   28.94  48.825  40.663  48.698  64.413  36.627
  79.058   35.39  85.292  32.851  91.883  30.919 102.119  30.942 113.379   30.24
 123.602  30.282 132.103   30.42 136.106  31.952 141.391  32.228 148.301  35.896
 160.167  36.394  172.09   42.94 184.085  42.976 192.969  39.879 227.864  41.467
 240.922  41.017 243.173  39.383 244.967  39.429 246.568  41.066  252.47  41.594
#Mann= 3 , 0 , 0
       0    .035       0       0    .035       0  252.47    .035       0
Bank Sta=0,252.47
XS Rating Curve= 0
Exp/Cntr=.3,.1

Type RM Length L Ch R = 1 ,766     ,160.4,160.4,160.4
XS GIS Cut Line= 2
      5313369.62     15923340.94      5313558.23      15923499.7
#Sta/Elev= 21
       0  41.982  28.783  42.044  40.246  47.799  54.633  48.238  79.052  36.539
  90.804  36.017  99.974  32.913 100.994  31.962 106.913  30.305 116.204  30.279
 124.888  30.249 136.978  30.594 148.261  31.266 152.812  31.611 158.927  34.688
 173.757  36.119 187.011  43.163 199.255  43.169 205.636  40.417 226.608  40.246
 247.011  39.951
#Mann= 3 , 0 , 0
       0    .035       0       0    .035       0 247.011    .035       0
Bank Sta=0,247.011
XS Rating Curve= 0
Exp/Cntr=.3,.1

Type RM Length L Ch R = 1 ,765     ,276.214,276.214,276.214
XS GIS Cut Line= 2
      5313268.21     15923457.02       5313408.5     15923584.97
#Sta/Elev= 20
       0  41.237  13.107  41.345  25.741  47.559  40.062  47.559  65.561  36.552
  80.141  34.682  85.016  33.182  85.728   31.43  90.676  31.194 101.782  30.338
 112.969  30.069 119.232  29.915 128.228  30.755 135.643  31.611 139.534  31.217
 145.384  34.501 160.289  36.014 172.028  42.835 184.954  42.835 190.056  41.302
#Mann= 3 , 0 , 0
       0    .035       0       0    .035       0 190.056    .035       0
Bank Sta=0,190.056
XS Rating Curve= 0
Exp/Cntr=.3,.1

Type RM Length L Ch R = 6 ,764.55  ,,,
Lateral Weir Pos= 3
Lateral Weir End=                ,                ,        ,c09
Lateral Weir Distance=3.281
Lateral Weir WD=9.843
Lateral Weir Coef=3.01
Lateral Weir Is Ogee= 0
Lateral Weir WSCriteria=-1
Lateral Weir SE= 6
       0   49.21    3.28   49.21    3.28   41.97  167.25   41.97  167.25   49.21
   171.5   49.21

Type RM Length L Ch R = 1 ,764     ,65.354,65.354,65.354
XS GIS Cut Line= 3
      5313100.26     15923608.17      5313181.43     15923776.87
      5313201.48      15923818.5
#Sta/Elev= 24
       0  39.813  11.257  40.413  28.448  51.906  61.575  51.381  95.095  37.064
 106.447  36.089 117.989  32.484 118.757   31.07 123.291  31.243 134.259  30.571
 145.443  30.682 153.107  29.265 160.997  31.591 164.239  31.841 170.325  31.995
 185.896  32.562 194.291  32.694 194.537   42.31 204.738  42.323 205.348  33.346
 211.165  33.228 214.603  40.509 218.163  42.434 236.266  42.073
#Mann= 3 , 0 , 0
       0    .035       0       0    .035       0 236.266    .035       0
Bank Sta=0,236.266
XS Rating Curve= 0
Exp/Cntr=.3,.1

Type RM Length L Ch R = 1 ,763     ,185.728,185.728,185.728
XS GIS Cut Line= 2
      5313085.63     15923612.66      5313105.09     15923830.45
#Sta/Elev= 22
       0  39.347   9.055  39.623  27.123  51.463  60.653  52.129  93.474  37.041
 107.536  35.797 116.732  33.077 117.726  32.418 123.504  31.286 131.404  30.594
 140.276  30.262 147.139  29.281  152.07  30.331  163.52  31.847  182.74  32.215
 191.722  30.669 191.906    43.1 203.143  42.723 204.019  41.703 207.566  41.463
 207.999  32.592 221.214  32.644
#Mann= 3 , 0 , 0
       0    .035       0       0    .035       0 221.214    .035       0
Bank Sta=0,221.214
XS Rating Curve= 0
Exp/Cntr=.3,.1

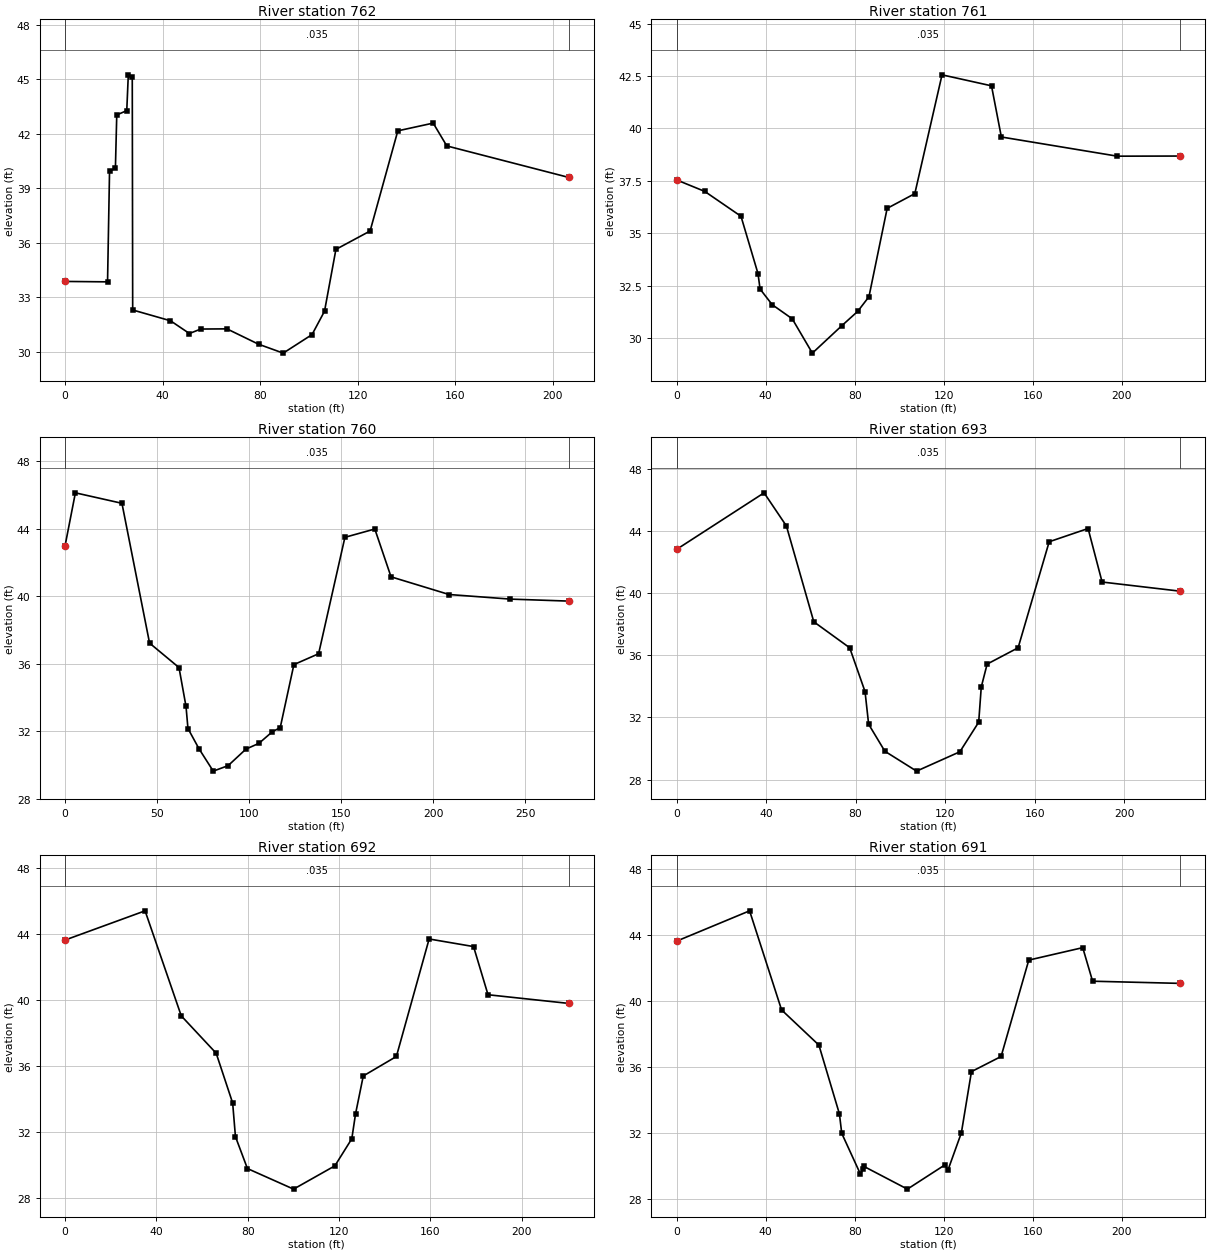
Type RM Length L Ch R = 1 ,762     ,77.592,77.592,77.592
XS GIS Cut Line= 3
      5312924.41     15923661.98      5312907.61      15923866.5
      5312907.61      15923866.5
#Sta/Elev= 23
       0  33.868  17.461  33.845  18.278  39.928  20.689  40.118  21.237  43.035
  25.341  43.271  25.974  45.243  27.598  45.118  27.772  32.297  43.274  31.703
  51.033  31.001  55.689  31.247  66.427  31.257  79.373  30.413  89.508  29.921
 101.329  30.942 106.447  32.228 111.122  35.633 125.141  36.644 136.512  42.159
  151.02  42.585 156.598  41.329 206.572  39.596
#Mann= 3 , 0 , 0
       0    .035       0       0    .035       0 206.572    .035       0
Bank Sta=0,206.572
XS Rating Curve= 0
Exp/Cntr=.3,.1

Type RM Length L Ch R = 1 ,761     ,145.538,145.538,145.538
XS GIS Cut Line= 3
      5312836.88     15923674.93      5312860.73     15923898.46
      5312860.73     15923898.46
#Sta/Elev= 18
       0  37.546  12.638  36.998   28.94   35.81  36.588  33.071  37.503  32.339
  42.943  31.594  51.949  30.919  60.997  29.281  74.193  30.587  81.332   31.27
  86.414  31.972   94.59  36.188 107.011   36.89 119.236  42.559  141.46  42.034
 145.886  39.593 197.949  38.678  226.23  38.684
#Mann= 3 , 0 , 0
       0    .035       0       0    .035       0  226.23    .035       0
Bank Sta=0,226.23
XS Rating Curve= 0
Exp/Cntr=.3,.1

Type RM Length L Ch R = 1 ,760     ,152.034,152.034,152.034
XS GIS Cut Line= 3
      5312656.76     15923717.85      5312794.06     15923950.92
      5312794.06     15923950.92
#Sta/Elev= 22
       0  42.953   5.653  46.115  30.925  45.495  45.919  37.218  61.896  35.771
  65.709  33.468  66.765  32.162  72.746  30.965  80.495  29.639  88.573  29.964
  98.235  30.942 105.279  31.283 112.592  31.972 116.847  32.211 124.268  35.945
  137.69  36.588 151.969  43.481 168.202  43.973 177.008  41.142 208.514  40.095
 241.785  39.823 273.425  39.705
#Mann= 3 , 0 , 0
       0    .035       0       0    .035       0 273.425    .035       0
Bank Sta=0,273.425
XS Rating Curve= 0
Exp/Cntr=.3,.1

Type RM Length L Ch R = 1 ,693     ,43.504,43.504,43.504
XS GIS Cut Line= 2
      5312529.86     15923779.89      5312632.02     15923980.41
#Sta/Elev= 18
       0  42.815  39.108  46.457  49.081  44.324  61.319  38.156  77.362  36.483
  84.219  33.661  85.827  31.562  93.077  29.823 107.251  28.543 126.608   29.79
 135.007  31.693 136.155  33.957  138.78  35.433 152.625  36.483 166.503  43.307
 183.891   44.16 190.157  40.715 225.066  40.125
#Mann= 3 , 0 , 0
       0    .035       0       0    .035       0 225.066    .035       0
Bank Sta=0,225.066
XS Rating Curve= 0
Exp/Cntr=.3,.1

Type RM Length L Ch R = 1 ,692     ,38.287,38.287,38.287
XS GIS Cut Line= 2
      5312515.09      15923791.4       5312564.7      15924006.3
#Sta/Elev= 17
       0  43.635  35.072  45.407  50.919  39.042  66.207  36.778  73.425   33.76
  74.639  31.726  79.888   29.79 100.098  28.543 118.176  29.954 125.591  31.594
 127.231  33.104  130.61    35.4 145.112  36.581 159.449  43.701 178.904  43.241
 185.236  40.322 220.538  39.797
#Mann= 3 , 0 , 0
       0    .035       0       0    .035       0 220.538    .035       0
Bank Sta=0,220.538
XS Rating Curve= 0
Exp/Cntr=.3,.1

Type RM Length L Ch R = 1 ,691     ,85.269,85.269,85.269
XS GIS Cut Line= 2
      5312504.56     15923801.77      5312539.93     15924025.26
#Sta/Elev= 19
       0  43.602  32.808   45.44  47.178  39.436  63.944  37.303  73.163  33.136
  74.213  31.955  82.579  29.495  83.858   29.79  84.154  29.954 103.707  28.576
 120.636  30.052 121.916  29.724 127.953  31.988  132.48  35.696 145.801  36.614
 158.235  42.454  182.48  43.209 186.909  41.175  226.28  41.043
#Mann= 3 , 0 , 0
       0    .035       0       0    .035       0  226.28    .035       0
Bank Sta=0,226.28
XS Rating Curve= 0
Exp/Cntr=.3,.1

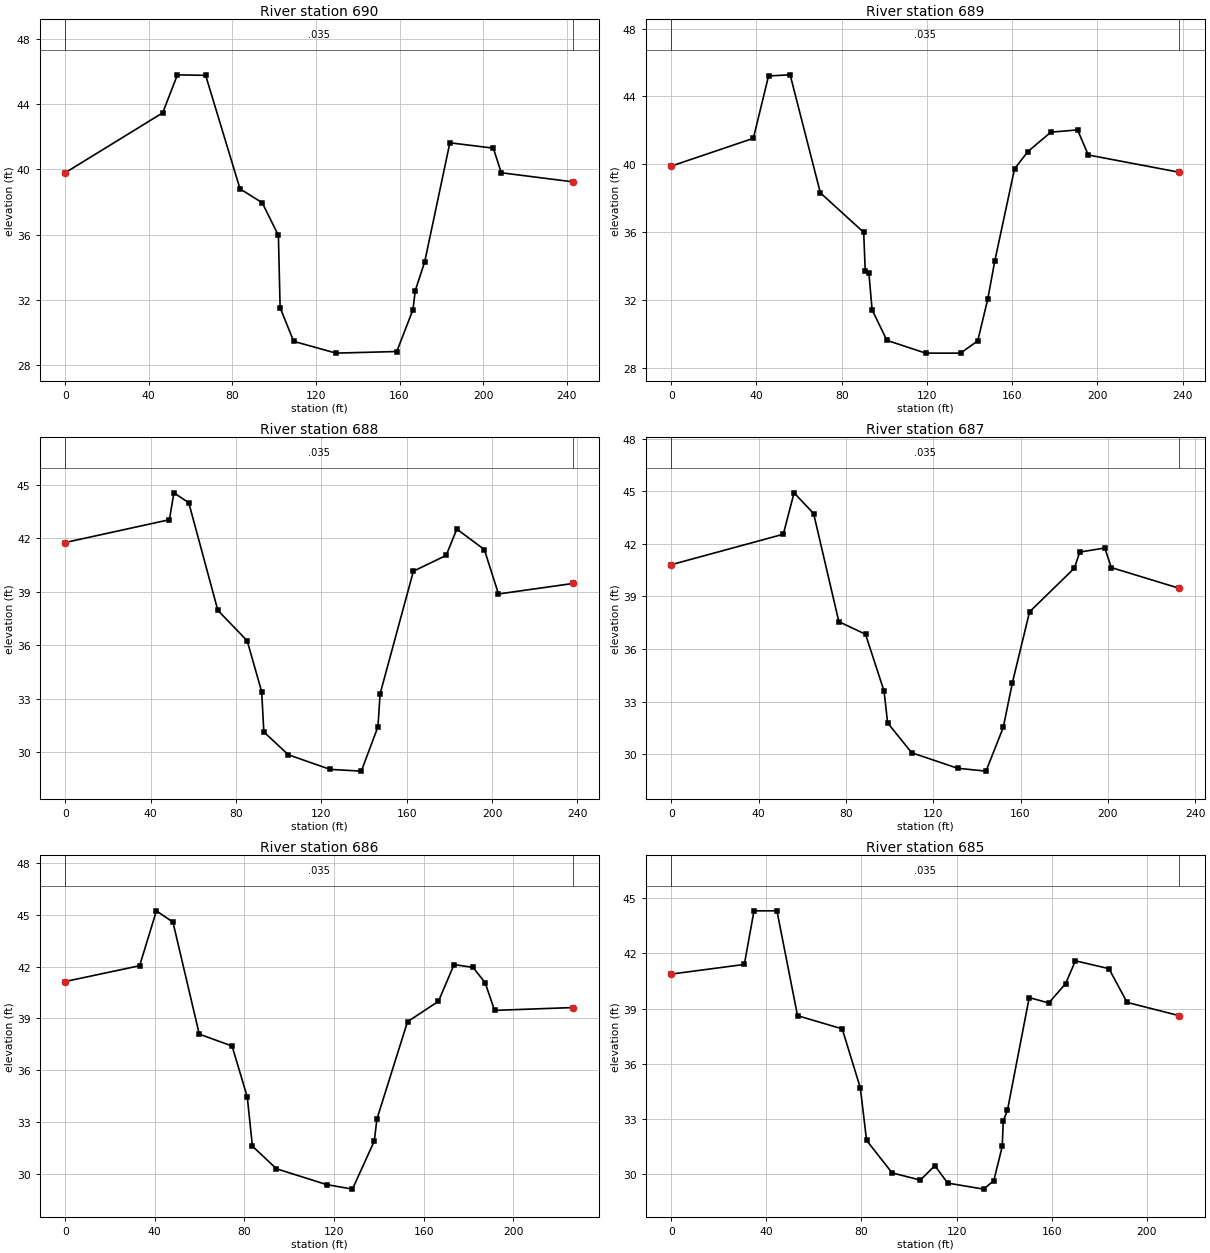
Type RM Length L Ch R = 1 ,690     ,70.112,70.112,70.112
XS GIS Cut Line= 2
      5312467.91     15923741.27      5312380.77     15923968.21
#Sta/Elev= 18
       0  39.797  46.654  43.471  53.707  45.801  67.224  45.768  83.661  38.812
  94.291  37.959 102.034  35.958 102.854  31.529  109.35  29.462 129.593   28.74
 158.694  28.839 166.404  31.398 167.552  32.579 172.014  34.318 184.088  41.634
 204.888  41.306 208.694  39.797 243.077  39.239
#Mann= 3 , 0 , 0
       0    .035       0       0    .035       0 243.077    .035       0
Bank Sta=0,243.077
XS Rating Curve= 0
Exp/Cntr=.3,.1

Type RM Length L Ch R = 1 ,689     ,96.785,96.785,96.785
XS GIS Cut Line= 2
      5312412.89     15923730.09      5312300.98     15923940.55
#Sta/Elev= 21
       0  39.895   38.55  41.535  45.669   45.21  55.807  45.276   69.98   38.32
  90.322  35.991  91.043  33.694  92.749  33.596  94.259   31.43 101.181  29.626
 119.357  28.871 135.761  28.871 143.832  29.593 148.589  32.087 151.804  34.285
 161.089  39.731 167.323  40.748  178.15  41.896 190.682  42.028 195.702  40.551
 238.353  39.534
#Mann= 3 , 0 , 0
       0    .035       0       0    .035       0 238.353    .035       0
Bank Sta=0,238.353
XS Rating Curve= 0
Exp/Cntr=.3,.1

Type RM Length L Ch R = 1 ,688     ,87.205,87.205,87.205
XS GIS Cut Line= 2
      5312309.84     15923682.38      5312228.44     15923906.04
#Sta/Elev= 19
       0  41.765  48.819  43.045  50.951  44.554  57.907  43.996  71.522  37.959
  85.269  36.253   92.06  33.399  93.077  31.135  104.56  29.856 124.114  29.035
 138.747  28.937 146.555   31.43 147.539  33.268 163.156  40.157  178.51  41.043
 183.497   42.52 196.391  41.371 203.018  38.878 237.992  39.469
#Mann= 3 , 0 , 0
       0    .035       0       0    .035       0 237.992    .035       0
Bank Sta=0,237.992
XS Rating Curve= 0
Exp/Cntr=.3,.1

Type RM Length L Ch R = 1 ,687     ,83.235,83.235,83.235
XS GIS Cut Line= 2
      5312221.33     15923638.68      5312161.09     15923863.42
#Sta/Elev= 19
       0  40.814  51.345  42.552  56.266  44.915  65.223  43.734  76.772  37.566
  89.009  36.844  97.507  33.596  99.114  31.791 110.138  30.085 131.168  29.199
 144.193  29.035   152.1  31.529 156.299  34.088  164.14  38.123 184.678  40.617
 187.139  41.535 198.589  41.765 201.608   40.65 232.677  39.469
#Mann= 3 , 0 , 0
       0    .035       0       0    .035       0 232.677    .035       0
Bank Sta=0,232.677
XS Rating Curve= 0
Exp/Cntr=.3,.1

Type RM Length L Ch R = 1 ,686     ,72.113,72.113,72.113
XS GIS Cut Line= 2
      5312142.72     15923621.26      5312080.22     15923839.17
#Sta/Elev= 20
       0  41.142  33.235   42.06  40.715  45.243  48.097  44.587  59.843  38.091
  74.475  37.402  81.266  34.449  83.563  31.594  94.291  30.282 116.667  29.364
 128.215  29.101 137.959   31.89  139.14  33.169 152.789  38.812 166.601  39.993
 173.556  42.126 182.021  41.962 187.434  41.076 191.634  39.469 226.706  39.633
#Mann= 3 , 0 , 0
       0    .035       0       0    .035       0 226.706    .035       0
Bank Sta=0,226.706
XS Rating Curve= 0
Exp/Cntr=.3,.1

Type RM Length L Ch R = 1 ,685     ,65.026,65.026,65.026
XS GIS Cut Line= 2
      5312081.43     15923595.73      5312011.88      15923797.7
#Sta/Elev= 24
       0  40.879  30.741  41.404   34.81  44.324  44.455  44.324  53.117  38.615
  71.916  37.894  79.528  34.678  82.152  31.824  92.881  30.052  104.79  29.659
  110.86  30.446 116.273  29.495 131.365  29.167 135.663  29.626 139.206  31.496
 139.633  32.874 141.404  33.465 150.558    39.6  158.76  39.304 165.846  40.354
  169.98  41.601 184.088  41.175 191.699  39.337 213.615  38.615
#Mann= 3 , 0 , 0
       0    .035       0       0    .035       0 213.615    .035       0
Bank Sta=0,213.615
XS Rating Curve= 0
Exp/Cntr=.3,.1