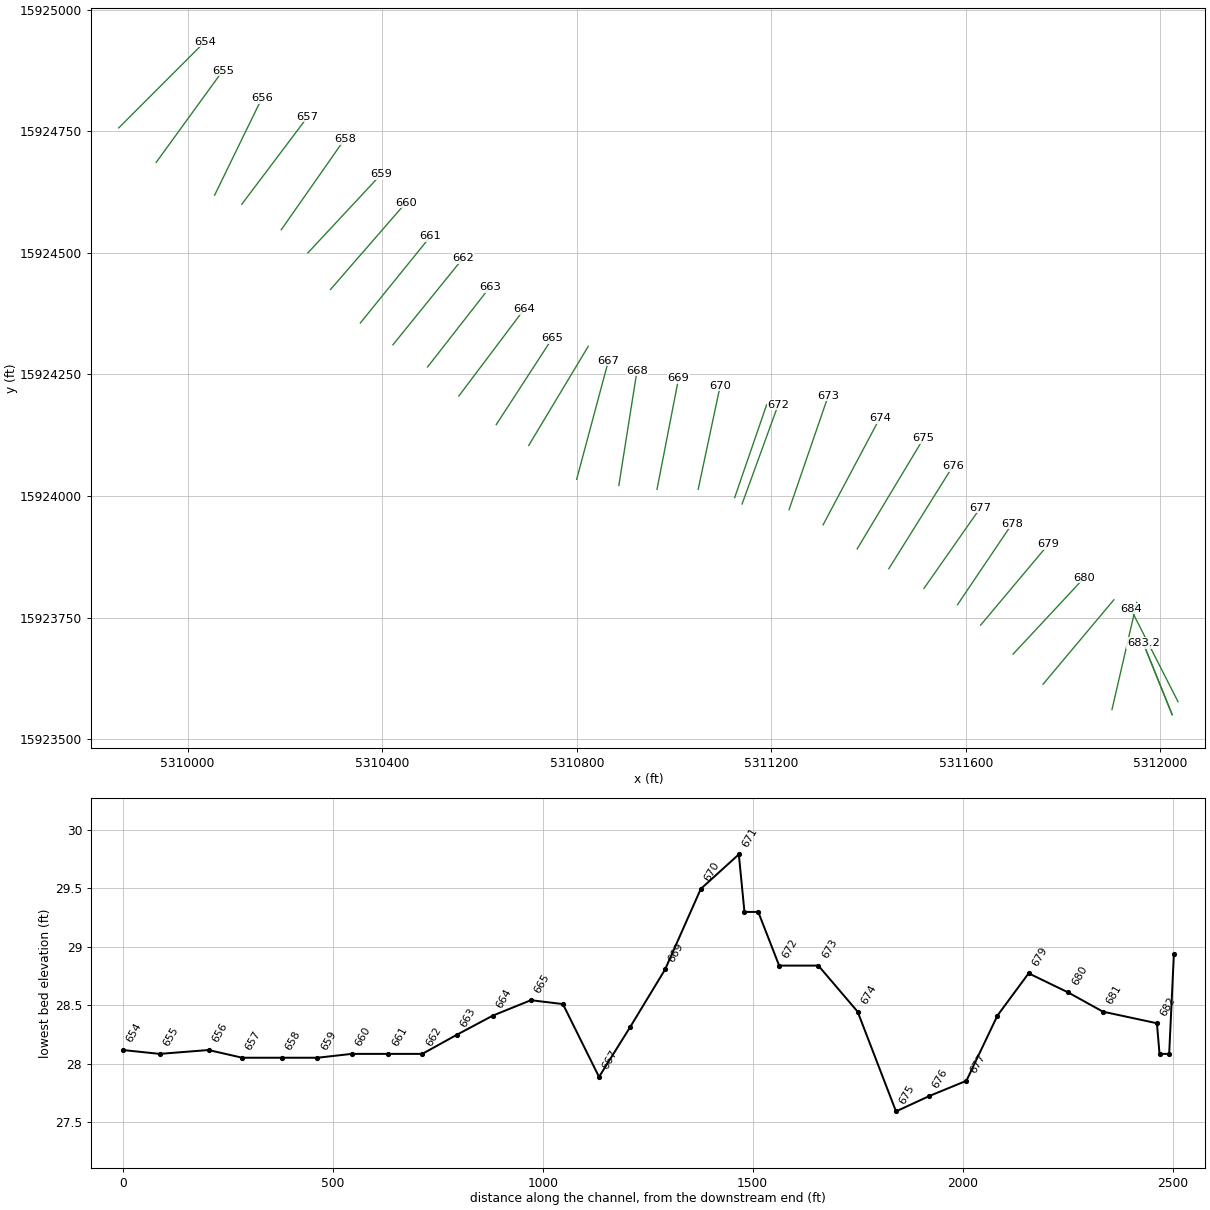
HEC-RAS study ozz_def.prj: ozzeri

--- ozz_def.g04 (geometry) --- (continued)

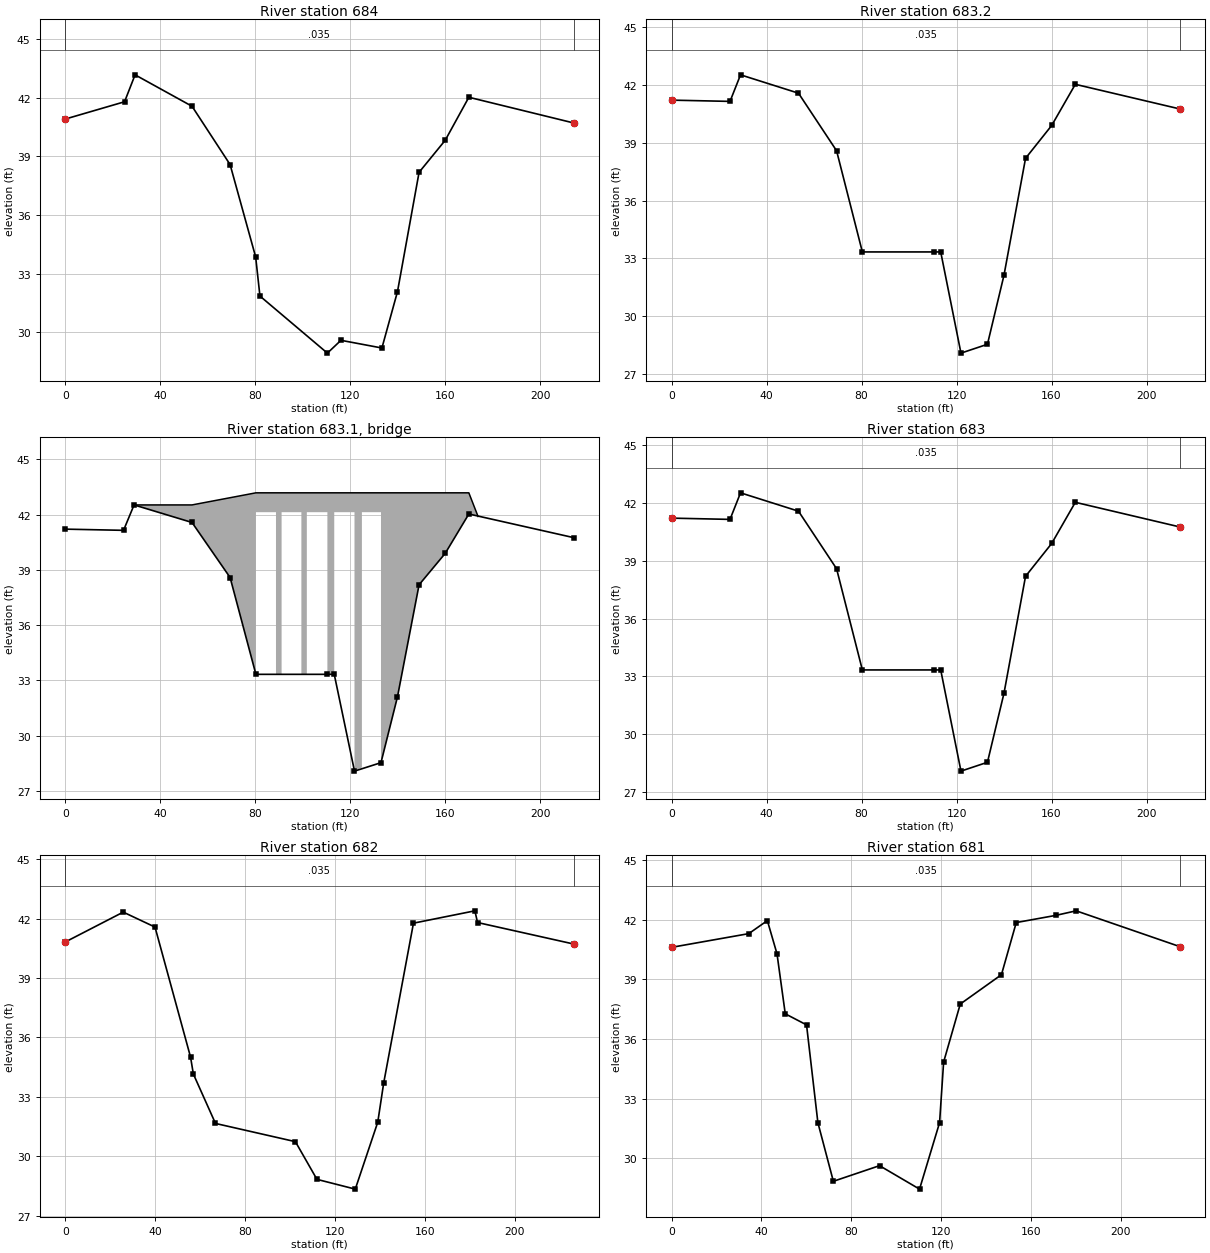
Type RM Length L Ch R = 1 ,684     ,11.22,11.22,11.22
XS GIS Cut Line= 2
      5312036.09     15923577.66      5311938.88     15923768.44
#Sta/Elev= 15
       0  40.912      25  41.798  29.429  43.176  53.412  41.568  69.455  38.583
  80.217  33.858  82.021  31.857 110.433  28.937 116.142  29.593 133.399  29.199
 139.961  32.087 149.049  38.189 160.072  39.829 170.013  42.028 214.108  40.715
#Mann= 3 , 0 , 0
       0    .035       0       0    .035       0 214.108    .035       0
Bank Sta=0,214.108
XS Rating Curve= 0
Exp/Cntr=.3,.1

Type RM Length L Ch R = 1 ,683.2   ,22.966,22.966,22.966
XS GIS Cut Line= 2
      5312024.11     15923550.85      5311964.63     15923698.06
#Sta/Elev= 15
       0  41.207  24.573  41.142  29.003   42.52  53.412  41.568  69.455  38.583
  80.315  33.333 110.433  33.333  113.32  33.333  121.85  28.084 133.005  28.543
 139.961  32.119 149.049  38.189 160.072  39.895 170.013  42.028 214.108  40.748
#Mann= 3 , 0 , 0
       0    .035       0       0    .035       0 214.108    .035       0
Bank Sta=0,214.108
XS Rating Curve= 0
Exp/Cntr=.3,.1

Type RM Length L Ch R = 3 ,683.1   ,,,
BEGIN DESCRIPTION:
Cateratte
END DESCRIPTION:
Bridge Culvert--1,0,-1,-1, 0
Deck Dist Width WeirC Skew NumUp NumDn MinLoCord MaxHiCord MaxSubmerge Is_Ogee
1.64,19.685,2.61,0, 27, 27, , , .95, 0, 0,0,,
  29.003  53.412  80.315  80.315   88.78   88.78  91.142  91.142  99.475  99.475
 101.772 101.772 110.433 110.433  113.32  113.32  121.85  121.85 124.967 124.967
 133.005 133.005 139.961 149.049 160.072 170.013 173.885
   42.52   42.52  43.176  43.176  43.176  43.176  43.176  43.176  43.176  43.176
  43.176  43.176  43.176  43.176  43.176  43.176  43.176  43.176  43.176  43.176
  43.176  43.176  43.176  43.176  43.176  43.176  41.896
   42.52  41.568  33.333  42.126  42.126  33.333  33.333  42.126  42.126  33.333
  33.333  42.126  42.126  33.333  33.333  42.126  42.126  28.084  28.281  42.126
  42.126  28.543  32.119  38.189  39.895  42.028  41.896
  29.003  53.412  80.315  80.315   88.78   88.78  91.142  91.142  99.475  99.475
 101.772 101.772 110.433 110.433  113.32  113.32  121.85  121.85 124.967 124.967
 133.005 133.005 139.961 149.049 160.072 170.013 173.885
   42.52   42.52  43.176  43.176  43.176  43.176  43.176  43.176  43.176  43.176
  43.176  43.176  43.176  43.176  43.176  43.176  43.176  43.176  43.176  43.176
  43.176  43.176  43.176  43.176  43.176  43.176  41.896
   42.52  41.568  33.333  42.126  42.126  33.333  33.333  42.126  42.126  33.333
  33.333  42.126  42.126  33.333  33.333  42.126  42.126  28.084  28.281  42.126
  42.126  28.543  32.119  38.189  39.895  42.028  41.896
BR Coef=-1 , 0 , 0 ,1.25, 0 ,,,.8,-1,2,0,
WSPro=,,,, 1 ,,,, 0 ,,,, 0 ,,,,-1 ,-1 ,-1 , 0 , 0 , 0 , 0 , 0
BC Design=,, 0 ,, 0 ,,,,,,
BC HTab Sub Flow Pts= 40

Type RM Length L Ch R = 1 ,683     ,6.234,6.234,6.234
XS GIS Cut Line= 2
      5312024.11     15923550.85      5311964.63     15923698.06
#Sta/Elev= 15
       0  41.207  24.573  41.142  29.003   42.52  53.412  41.568  69.455  38.583
  80.315  33.333 110.433  33.333  113.32  33.333  121.85  28.084 133.005  28.543
 139.961  32.119 149.049  38.189 160.072  39.895 170.013  42.028 214.108  40.748
#Mann= 3 , 0 , 0
       0    .035       0       0    .035       0 214.108    .035       0
Bank Sta=0,214.108
XS Rating Curve= 0
Exp/Cntr=.3,.1

Type RM Length L Ch R = 1 ,682     ,128.576,128.576,128.576
XS GIS Cut Line= 2
      5311900.46     15923561.29      5311951.35     15923781.66
#Sta/Elev= 15
       0  40.814   25.82  42.323  39.961  41.568  55.774  35.007  57.021  34.154
  66.864   31.66 102.428  30.741 112.008  28.839 129.068  28.346 139.075  31.726
 141.699  33.694 154.954  41.765 182.283  42.388 183.465  41.798 226.181  40.715
#Mann= 3 , 0 , 0
       0    .035       0       0    .035       0 226.181    .035       0
Bank Sta=0,226.181
XS Rating Curve= 0
Exp/Cntr=.3,.1

Type RM Length L Ch R = 1 ,681     ,82.448,82.448,82.448
XS GIS Cut Line= 2
      5311758.76     15923613.45       5311904.3     15923786.88
#Sta/Elev= 18
       0  40.617   34.35  41.306  42.618  41.962  46.916  40.289  50.591   37.27
  60.072  36.713  65.125  31.791  72.014  28.839  92.585  29.626   110.4  28.445
 119.324  31.791 121.129  34.843 128.543  37.762 146.883  39.239 153.478  41.864
 171.063  42.224 180.151  42.454 226.411   40.65
#Mann= 3 , 0 , 0
       0    .035       0       0    .035       0 226.411    .035       0
Bank Sta=0,226.411
XS Rating Curve= 0
Exp/Cntr=.3,.1

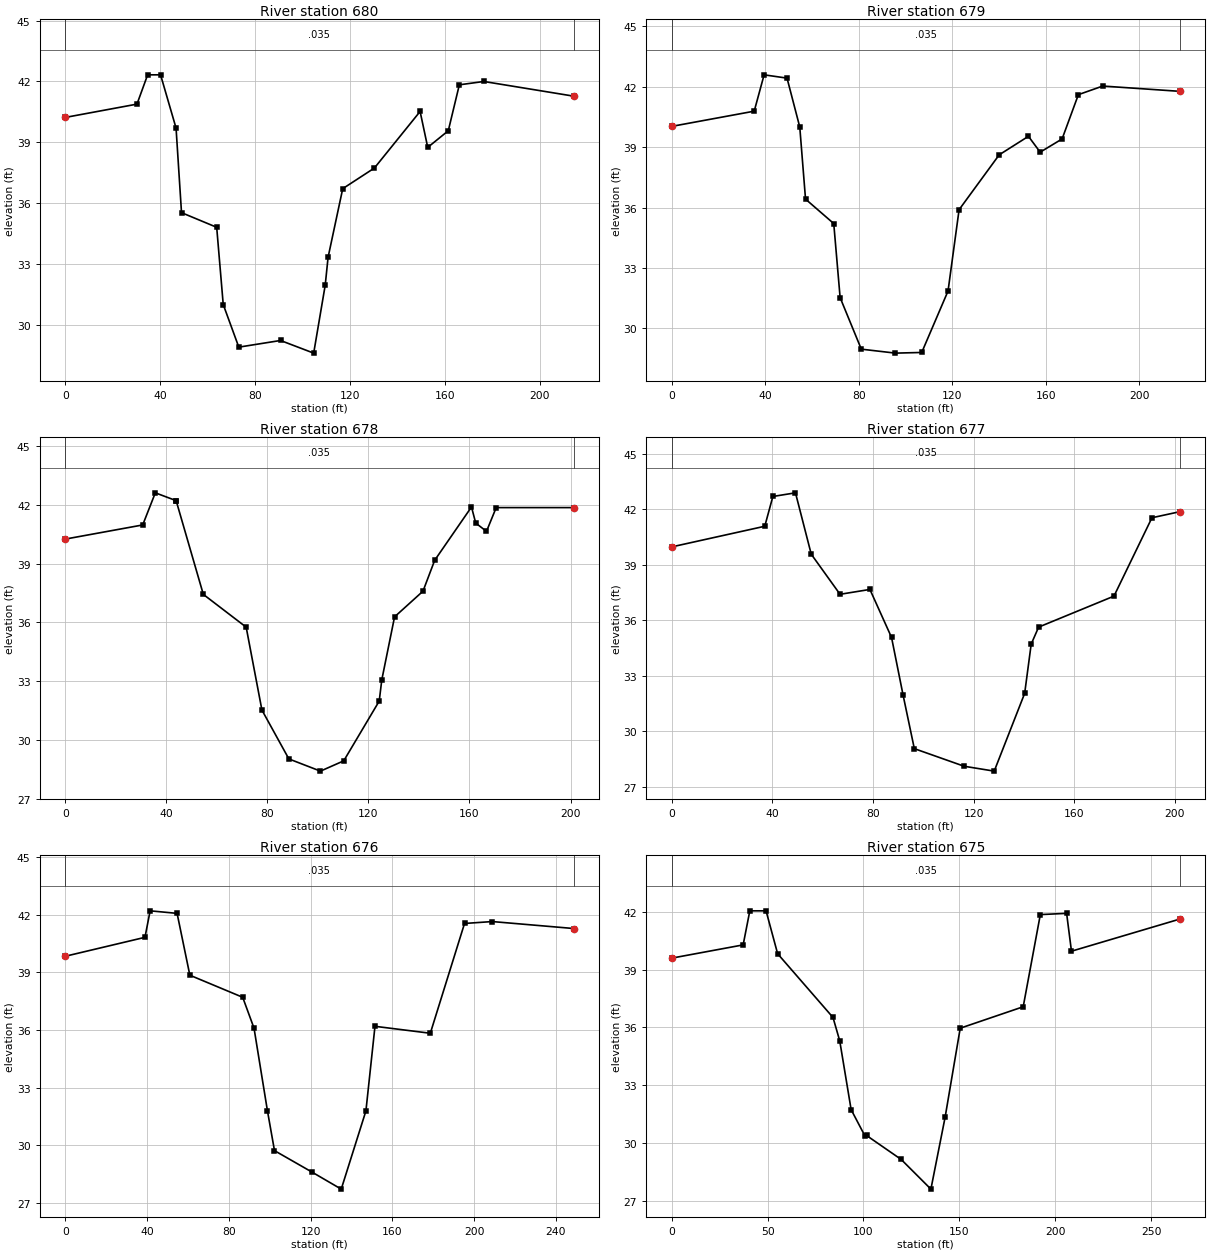
Type RM Length L Ch R = 1 ,680     ,94.455,94.455,94.455
XS GIS Cut Line= 2
      5311697.24     15923675.39      5311843.34     15923832.09
#Sta/Elev= 21
       0  40.223  30.249  40.879  34.744  42.323   40.19  42.323  46.719  39.698
  49.016  35.531  63.845   34.81  66.601  31.004  73.163  28.904  90.748  29.232
 104.724  28.609  109.58  31.955 110.794  33.333 116.962  36.713 130.315   37.73
 149.573  40.518 152.789  38.747  161.45  39.567 166.109  41.831 176.444  41.995
 214.239  41.273
#Mann= 3 , 0 , 0
       0    .035       0       0    .035       0 214.239    .035       0
Bank Sta=0,214.239
XS Rating Curve= 0
Exp/Cntr=.3,.1

Type RM Length L Ch R = 1 ,679     ,74.213,74.213,74.213
XS GIS Cut Line= 2
      5311630.41     15923734.88      5311770.18     15923901.41
#Sta/Elev= 20
       0  40.026  35.302  40.781  39.534  42.585  49.344  42.421   54.79  39.993
  57.251  36.417  69.324  35.203  72.047  31.529  81.102   28.97  95.702  28.773
 106.955  28.806 118.209  31.857 122.933  35.892 140.092  38.615 152.592  39.534
 157.612  38.747 166.995  39.403  173.95  41.601 184.383  42.028 217.421  41.765
#Mann= 3 , 0 , 0
       0    .035       0       0    .035       0 217.421    .035       0
Bank Sta=0,217.421
XS Rating Curve= 0
Exp/Cntr=.3,.1

Type RM Length L Ch R = 1 ,678     ,73.983,73.983,73.983
XS GIS Cut Line= 2
      5311582.91      15923776.9      5311695.41      15923943.7
#Sta/Elev= 21
       0  40.256  30.676  40.978  35.663  42.618  43.799  42.224  43.963  42.192
  54.659  37.434  71.621  35.761  77.854  31.529  88.517  29.035 101.017  28.412
 110.236  28.937 124.278  31.988 125.295  33.071 130.348  36.286 141.601  37.598
 146.227  39.173 160.794  41.896 162.467  41.076 166.732   40.65 170.571  41.864
 201.181  41.864
#Mann= 3 , 0 , 0
       0    .035       0       0    .035       0 201.181    .035       0
Bank Sta=0,201.181
XS Rating Curve= 0
Exp/Cntr=.3,.1

Type RM Length L Ch R = 1 ,677     ,88.747,88.747,88.747
XS GIS Cut Line= 2
      5311513.98     15923810.43      5311629.86     15923975.95
#Sta/Elev= 18
       0  39.961  37.008  41.076  40.223  42.684  49.213  42.881  55.479  39.567
  66.929  37.402  78.806  37.664  87.402  35.072  91.995  31.955  96.457  29.068
 116.273  28.117 128.215  27.854 140.322  32.054 142.913  34.711 145.866   35.63
  175.82  37.303 190.912  41.535 202.067  41.864
#Mann= 3 , 0 , 0
       0    .035       0       0    .035       0 202.067    .035       0
Bank Sta=0,202.067
XS Rating Curve= 0
Exp/Cntr=.3,.1

Type RM Length L Ch R = 1 ,676     ,78.871,78.871,78.871
XS GIS Cut Line= 2
       5311441.6     15923850.79      5311573.36     15924061.61
#Sta/Elev= 17
       0  39.829  39.009  40.814  41.535  42.192  54.724   42.06  60.958  38.845
  86.811  37.697  92.356  36.089  98.917  31.791 102.362  29.724 120.702  28.609
 135.007  27.723  147.08  31.791 151.509  36.188 178.576  35.827 195.308  41.535
 208.891  41.634 248.622  41.273
#Mann= 3 , 0 , 0
       0    .035       0       0    .035       0 248.622    .035       0
Bank Sta=0,248.622
XS Rating Curve= 0
Exp/Cntr=.3,.1

Type RM Length L Ch R = 1 ,675     ,91.404,91.404,91.404
XS GIS Cut Line= 2
      5311376.54     15923891.57      5311513.06     15924118.77
#Sta/Elev= 19
       0    39.6   37.27  40.289  40.748   42.06  49.213   42.06  55.249  39.829
  84.121  36.516  87.631  35.302   93.57  31.726  100.82  30.348 101.608  30.381
 119.685  29.134 135.171  27.592 142.585  31.332 150.459  35.958 183.301  37.073
 192.224  41.864 205.938  41.929 208.465  39.961 265.059  41.634
#Mann= 3 , 0 , 0
       0    .035       0       0    .035       0 265.059    .035       0
Bank Sta=0,265.059
XS Rating Curve= 0
Exp/Cntr=.3,.1

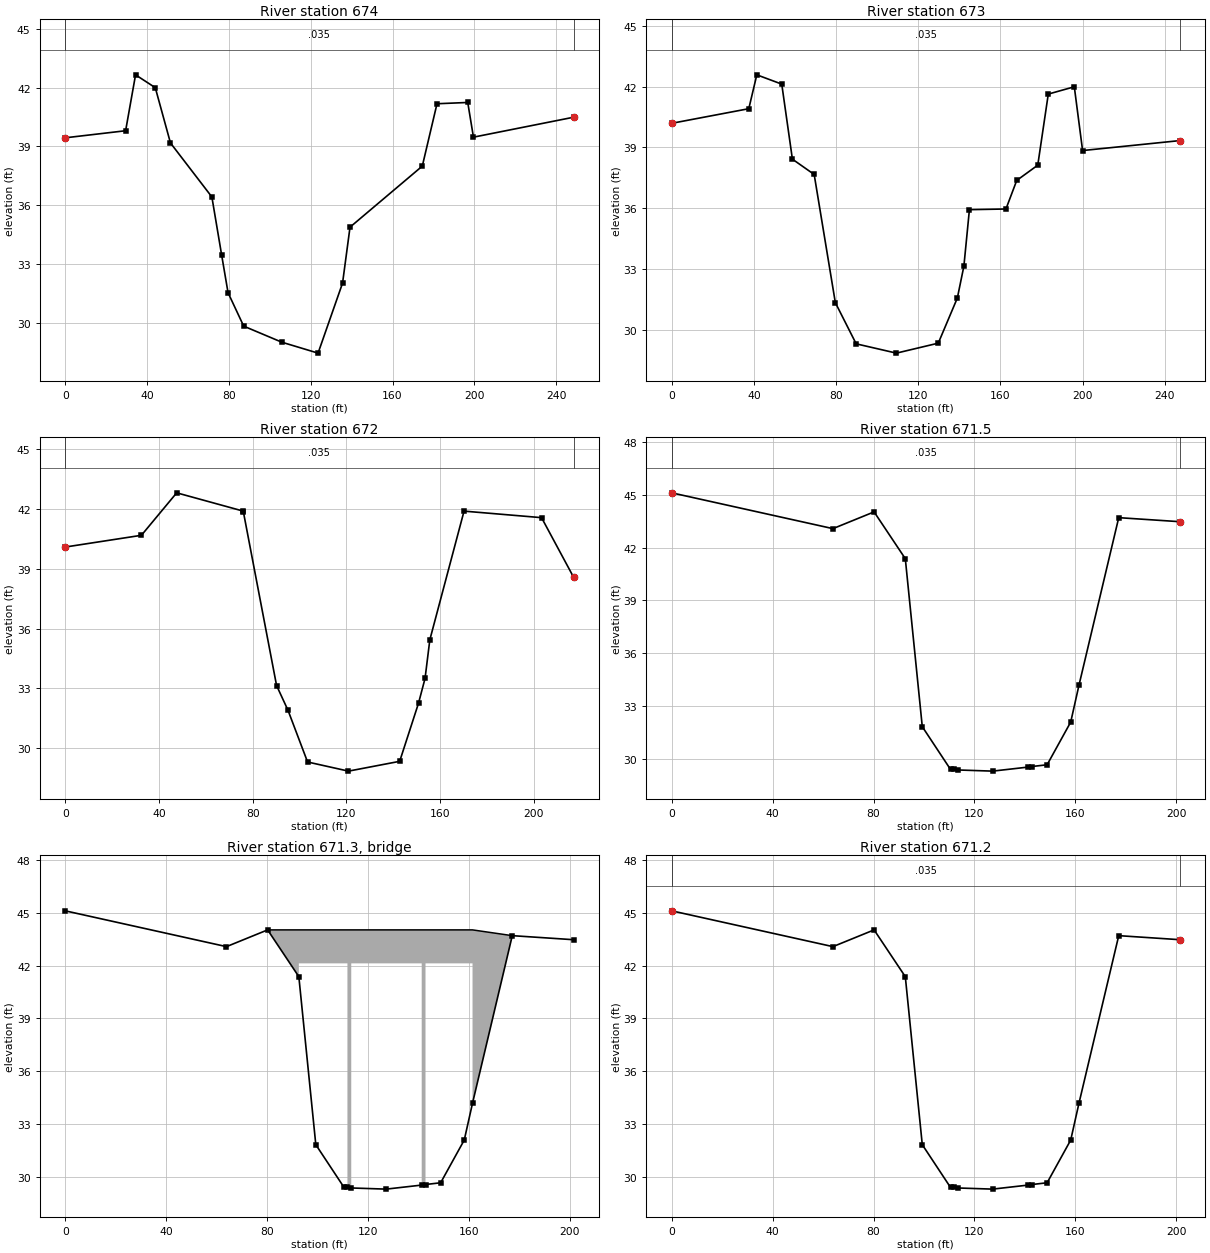
Type RM Length L Ch R = 1 ,674     ,93.602,93.602,93.602
XS GIS Cut Line= 2
       5311306.5     15923941.04      5311423.13     15924160.43
#Sta/Elev= 18
       0  39.436  29.528  39.797  34.383  42.651  44.029  41.995  51.444  39.173
  71.686  36.417  76.444  33.465  79.593  31.529  87.238  29.823 105.873  29.003
 123.589  28.445 135.564  32.021 139.206  34.875 174.541  37.992 181.726  41.175
 196.752   41.24 199.541  39.469 248.458  40.486
#Mann= 3 , 0 , 0
       0    .035       0       0    .035       0 248.458    .035       0
Bank Sta=0,248.458
XS Rating Curve= 0
Exp/Cntr=.3,.1

Type RM Length L Ch R = 1 ,673     ,93.307,93.307,93.307
XS GIS Cut Line= 2
      5311236.52     15923972.18      5311317.06      15924206.1
#Sta/Elev= 20
       0   40.19  37.533  40.912  41.437  42.585  53.576  42.126   58.76  38.419
  69.357  37.664  79.659  31.332  89.797  29.298 109.383  28.839 129.757  29.331
 139.042  31.562 142.224  33.136 144.915  35.925 162.697  35.958 167.946  37.369
 178.182  38.123 183.301  41.634 195.965  41.995     200  38.845 247.408  39.337
#Mann= 3 , 0 , 0
       0    .035       0       0    .035       0 247.408    .035       0
Bank Sta=0,247.408
XS Rating Curve= 0
Exp/Cntr=.3,.1

Type RM Length L Ch R = 1 ,672     ,49.803,49.803,49.803
XS GIS Cut Line= 2
      5311139.93     15923983.89      5311214.11      15924187.7
#Sta/Elev= 16
       0  40.092  32.513  40.682  47.572  42.815  75.984  41.896  76.017  41.864
   90.19  33.136  95.079   31.89 103.412  29.298 120.866  28.839 142.717  29.331
 150.755  32.251 153.543  33.497 155.577  35.433 170.177  41.896 203.248  41.568
 216.896  38.583
#Mann= 3 , 0 , 0
       0    .035       0       0    .035       0 216.896    .035       0
Bank Sta=0,216.896
XS Rating Curve= 0
Exp/Cntr=.3,.1

Type RM Length L Ch R = 1 ,671.5   ,32.808,32.808,32.808
#Sta/Elev= 16
       0  45.112  63.911  43.077  80.217  44.029  92.585  41.371  99.311  31.824
 110.499  29.396 111.844  29.396 113.353  29.364 127.198  29.298 141.273  29.528
 142.782   29.56 148.786  29.659 158.136  32.087 161.417  34.186 177.165  43.701
 201.444  43.471
#Mann= 3 , 0 , 0
       0    .035       0       0    .035       0 201.444    .035       0
Bank Sta=0,201.444
XS Rating Curve= 0
Exp/Cntr=.3,.1

Type RM Length L Ch R = 3 ,671.3   ,,,
BEGIN DESCRIPTION:
Ponte di ferro
END DESCRIPTION:
Bridge Culvert--1,0,-1,-1, 0
Deck Dist Width WeirC Skew NumUp NumDn MinLoCord MaxHiCord MaxSubmerge Is_Ogee
1.64,29.528,2.61,0, 14, 14, , , .95, 0, 0,0,,
  80.217  92.585  92.585 111.844 111.844 113.353 113.353 141.273 141.273 142.782
 142.782 161.417 161.417 177.165
  44.029  44.029  44.029  44.029  44.029  44.029  44.029  44.029  44.029  44.029
  44.029  44.029  44.029  43.701
  44.029  34.908  42.126  42.126  29.396  29.364  42.126  42.126  29.528   29.56
  42.126  42.126  34.186  43.701
  80.217  92.585  92.585 111.844 111.844 113.353 113.353 141.273 141.273 142.782
 142.782 161.417 161.417 177.165
  44.029  44.029  44.029  44.029  44.029  44.029  44.029  44.029  44.029  44.029
  44.029  44.029  44.029  43.701
  44.029  34.908  42.126  42.126  29.396  29.364  42.126  42.126  29.528   29.56
  42.126  42.126  34.186  43.701
BR Coef=-1 , 0 , 0 ,1.25, 0 ,,,.8,-1,2,0,
WSPro=,,,, 1 ,,,, 0 ,,,, 0 ,,,,-1 ,-1 ,-1 , 0 , 0 , 0 , 0 , 0
BC Design=,, 0 ,, 0 ,,,,,,
BC HTab Sub Flow Pts= 40

Type RM Length L Ch R = 1 ,671.2   ,13.451,13.451,13.451
#Sta/Elev= 16
       0  45.112  63.911  43.077  80.217  44.029  92.585  41.371  99.311  31.824
 110.499  29.396 111.844  29.396 113.353  29.364 127.198  29.298 141.273  29.528
 142.782   29.56 148.786  29.659 158.136  32.087 161.417  34.186 177.165  43.701
 201.444  43.471
#Mann= 3 , 0 , 0
       0    .035       0       0    .035       0 201.444    .035       0
Bank Sta=0,201.444
XS Rating Curve= 0
Exp/Cntr=.3,.1

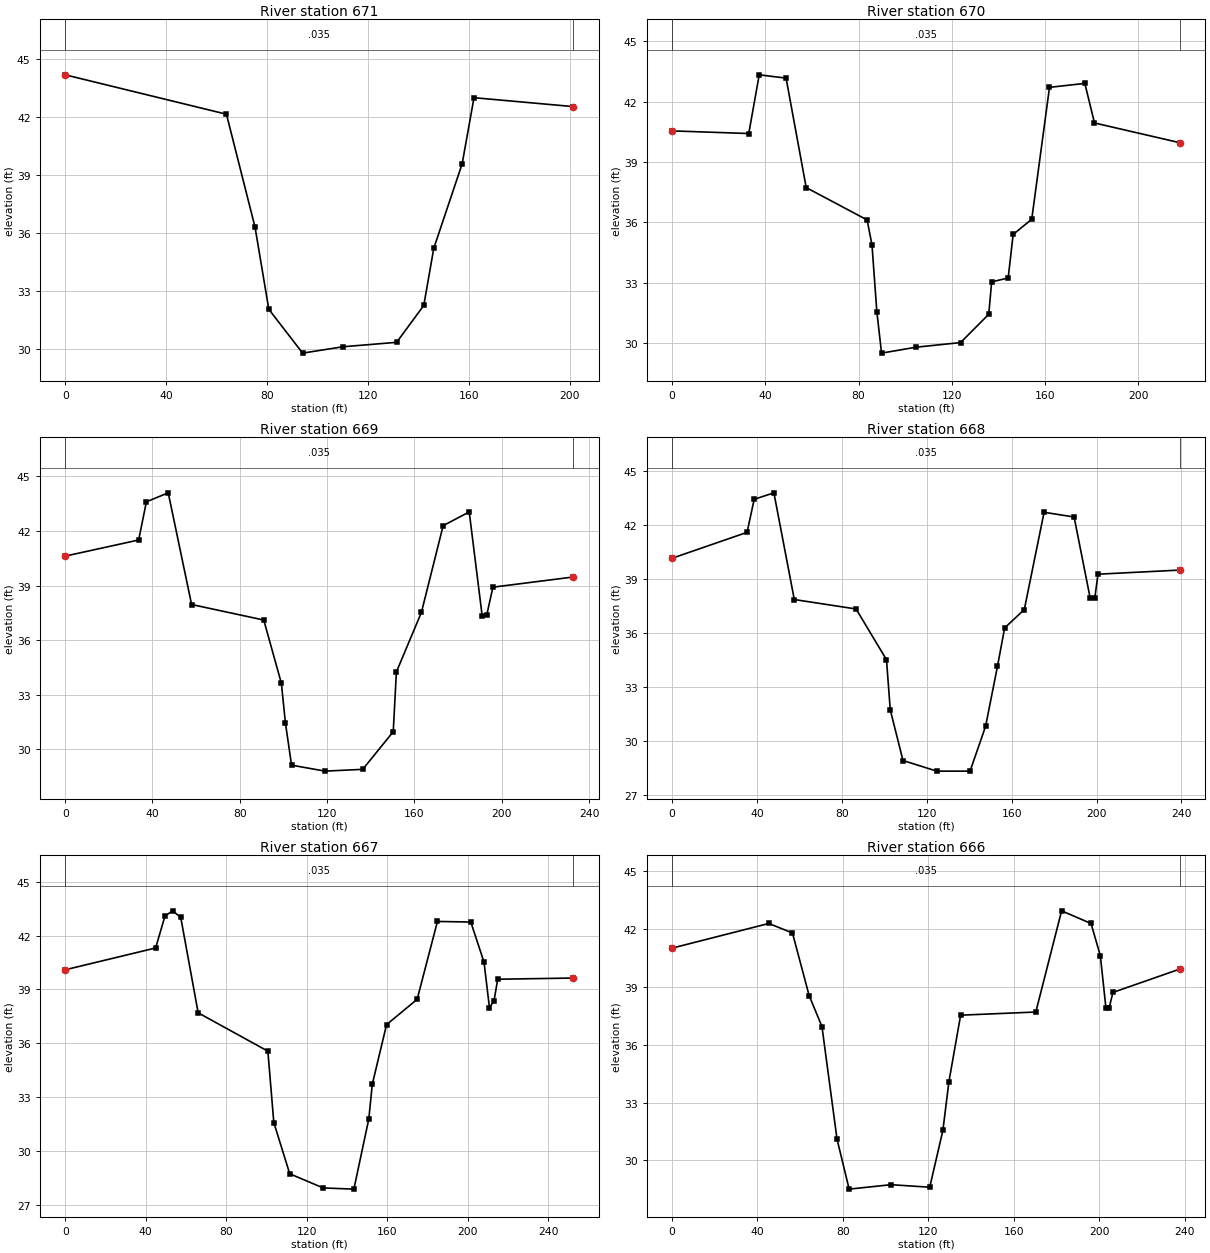
Type RM Length L Ch R = 1 ,671     ,90.551,90.551,90.551
XS GIS Cut Line= 2
      5311124.67     15923996.92      5311190.26     15924187.37
#Sta/Elev= 12
       0   44.16  63.944  42.126  75.295  36.286  80.741  32.054   94.16   29.79
 110.072  30.118  131.43  30.348 142.192  32.251 146.161  35.203 157.415  39.567
 162.106  42.979 201.444   42.52
#Mann= 3 , 0 , 0
       0    .035       0       0    .035       0 201.444    .035       0
Bank Sta=0,201.444
XS Rating Curve= 0
Exp/Cntr=.3,.1

Type RM Length L Ch R = 1 ,670     ,85.007,85.007,85.007
XS GIS Cut Line= 2
      5311049.67     15924014.11      5311094.98      15924227.2
#Sta/Elev= 20
       0  40.551  32.907   40.42  37.402   43.34  48.917  43.176  57.546   37.73
  83.661  36.122  85.761  34.875  87.828  31.562  89.862  29.495 104.659   29.79
 123.753   30.02 135.827   31.43 137.073  33.038  144.16  33.235 146.293    35.4
 154.265  36.155 161.877  42.717 177.034  42.913 181.168  40.945 217.848  39.961
#Mann= 3 , 0 , 0
       0    .035       0       0    .035       0 217.848    .035       0
Bank Sta=0,217.848
XS Rating Curve= 0
Exp/Cntr=.3,.1

Type RM Length L Ch R = 1 ,669     ,83.038,83.038,83.038
XS GIS Cut Line= 2
      5310964.99     15924013.85      5311009.42     15924242.32
#Sta/Elev= 20
       0  40.617  33.661  41.503  37.205  43.602  47.211  44.094  57.907  37.959
  90.978  37.106  99.049  33.629 100.886  31.463 103.707  29.134 119.029  28.806
 136.319  28.904 150.295  30.971 151.739  34.252 163.222  37.533 173.163   42.29
 185.105  43.045 191.076  37.303  193.11  37.369 195.965  38.911 232.743  39.469
#Mann= 3 , 0 , 0
       0    .035       0       0    .035       0 232.743    .035       0
Bank Sta=0,232.743
XS Rating Curve= 0
Exp/Cntr=.3,.1

Type RM Length L Ch R = 1 ,668     ,74.278,74.278,74.278
XS GIS Cut Line= 2
      5310886.48     15924021.78      5310923.95     15924258.17
#Sta/Elev= 21
       0  40.157  35.367  41.601  38.714  43.438  47.999  43.799  57.612  37.861
  86.713  37.336  101.05  34.514 102.822  31.726 108.825  28.904 124.738  28.314
  140.42  28.314 147.736  30.807 153.346  34.154 156.726  36.286 165.978  37.303
 175.295  42.717 189.436  42.454 196.982  37.959 199.213  37.959 200.689  39.272
 239.337  39.501
#Mann= 3 , 0 , 0
       0    .035       0       0    .035       0 239.337    .035       0
Bank Sta=0,239.337
XS Rating Curve= 0
Exp/Cntr=.3,.1

Type RM Length L Ch R = 1 ,667     ,86.024,86.024,86.024
XS GIS Cut Line= 2
       5310799.8     15924034.51      5310865.12     15924278.22
#Sta/Elev= 22
       0  40.092  44.915  41.306  49.541  43.077  53.314  43.373  57.382  43.012
  66.043  37.697 100.656  35.564 103.609  31.594 111.516   28.74  128.15  27.953
 143.373  27.887 150.787  31.791 152.526  33.727 159.613  37.041 174.803  38.451
 184.875  42.782 201.444  42.749 208.005  40.518 210.696  37.992 212.959  38.353
 214.797  39.567 252.297  39.633
#Mann= 3 , 0 , 0
       0    .035       0       0    .035       0 252.297    .035       0
Bank Sta=0,252.297
XS Rating Curve= 0
Exp/Cntr=.3,.1

Type RM Length L Ch R = 1 ,666     ,76.181,76.181,76.181
XS GIS Cut Line= 2
      5310701.21      15924104.1      5310823.72     15924308.01
#Sta/Elev= 20
       0   41.01  45.308   42.29  56.398  41.798  64.206   38.55   70.21  36.942
  77.264  31.102   82.94   28.51 102.526   28.74 120.669  28.609 126.837  31.562
 129.659  34.088 135.138  37.533 170.341  37.697 182.415  42.946 196.194   42.29
 200.558  40.617  203.15  37.927 204.692  37.927 206.463  38.714 237.861  39.928
#Mann= 3 , 0 , 0
       0    .035       0       0    .035       0 237.861    .035       0
Bank Sta=0,237.861
XS Rating Curve= 0
Exp/Cntr=.3,.1

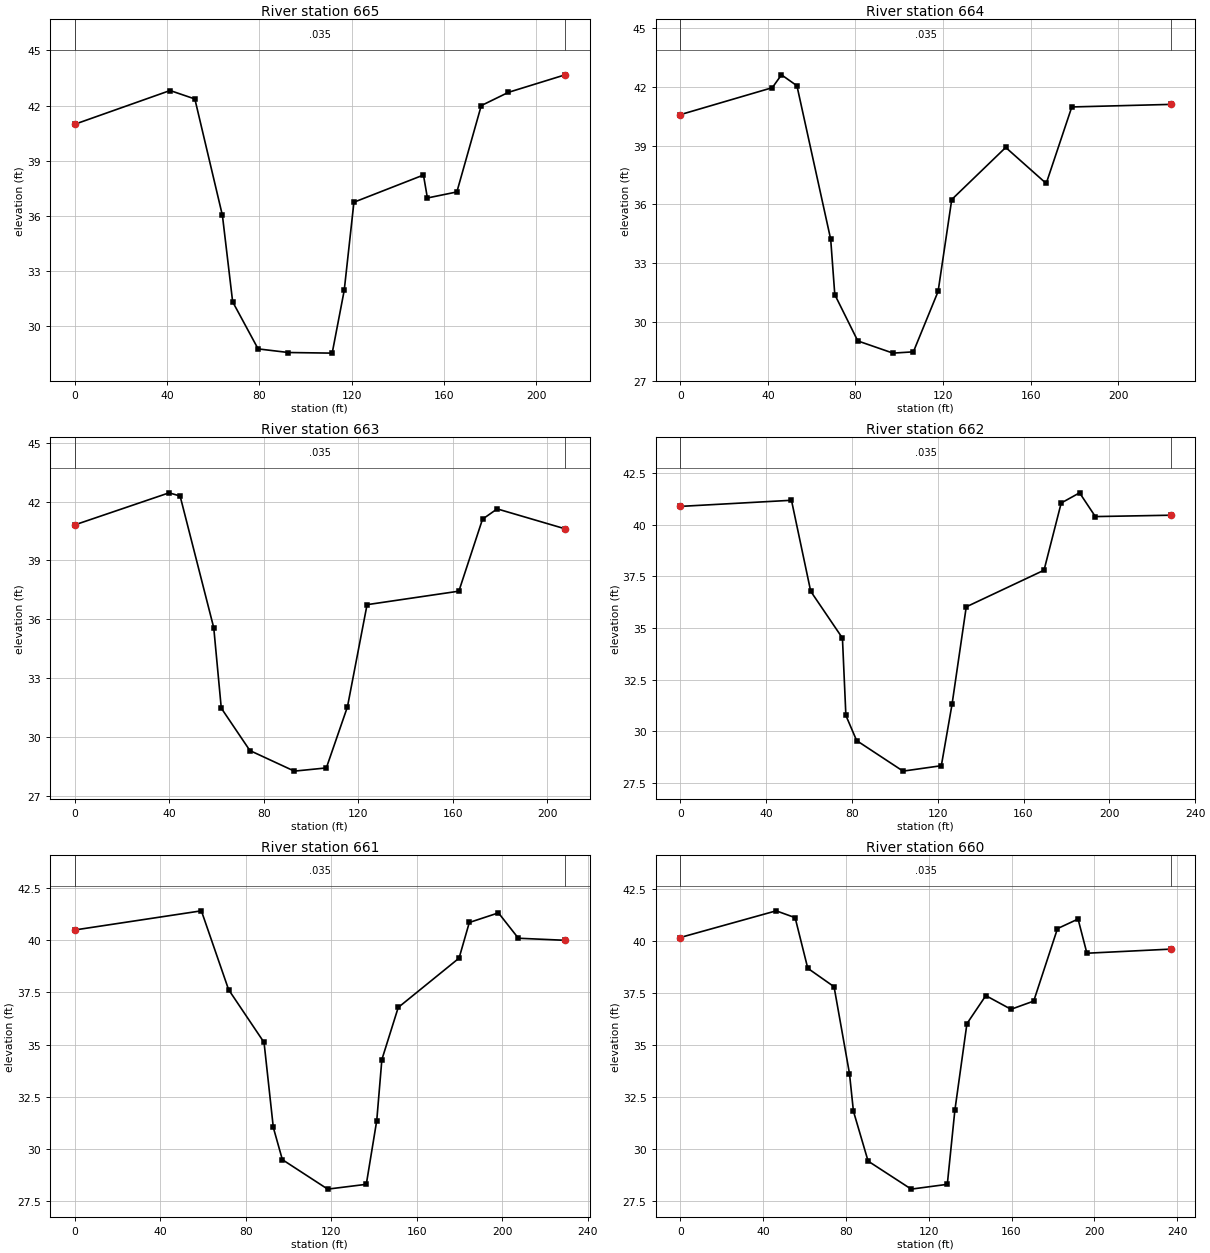
Type RM Length L Ch R = 1 ,665     ,90.322,90.322,90.322
XS GIS Cut Line= 2
      5310634.48     15924146.92       5310750.2      15924325.1
#Sta/Elev= 16
       0  40.978  41.371  42.815    52.1  42.356  64.042  36.024  68.471  31.332
  79.495  28.773  92.651  28.576 111.581  28.543 116.798  31.955 120.997  36.745
 151.115  38.222 152.822  36.975 165.584  37.303 176.148  41.995 187.926  42.717
 212.467  43.668
#Mann= 3 , 0 , 0
       0    .035       0       0    .035       0 212.467    .035       0
Bank Sta=0,212.467
XS Rating Curve= 0
Exp/Cntr=.3,.1

Type RM Length L Ch R = 1 ,664     ,85.794,85.794,85.794
XS GIS Cut Line= 2
      5310557.45     15924205.64      5310692.26     15924384.55
#Sta/Elev= 15
       0  40.584  42.028  41.962  46.227  42.618  53.281   42.06  68.701  34.219
  70.571  31.398   81.07  29.035  97.146  28.412 106.463  28.478 117.749  31.562
 123.983  36.253 148.622  38.911 167.126  37.073 178.806  40.978 224.016  41.109
#Mann= 3 , 0 , 0
       0    .035       0       0    .035       0 224.016    .035       0
Bank Sta=0,224.016
XS Rating Curve= 0
Exp/Cntr=.3,.1

Type RM Length L Ch R = 1 ,663     ,82.48,82.48,82.48
XS GIS Cut Line= 2
      5310493.24     15924265.42      5310621.03     15924428.97
#Sta/Elev= 14
       0  40.814  39.993  42.454  44.652   42.29  58.891  35.564  62.073  31.463
   74.18  29.298  92.979  28.248 106.529  28.412 115.453  31.529 123.753  36.745
 162.598  37.434 172.605  41.109 178.806  41.634 207.546  40.617
#Mann= 3 , 0 , 0
       0    .035       0       0    .035       0 207.546    .035       0
Bank Sta=0,207.546
XS Rating Curve= 0
Exp/Cntr=.3,.1

Type RM Length L Ch R = 1 ,662     ,80.643,80.643,80.643
XS GIS Cut Line= 2
      5310422.15     15924311.12      5310566.04     15924488.81
#Sta/Elev= 15
       0  40.879  51.837  41.175  60.794  36.778  75.591  34.514  77.198  30.774
  82.218   29.56 103.839  28.084 121.686  28.346 126.706  31.332 133.301  36.024
 169.554  37.795 177.559  41.043 186.122  41.535 193.471  40.387 228.642  40.453
#Mann= 3 , 0 , 0
       0    .035       0       0    .035       0 228.642    .035       0
Bank Sta=0,228.642
XS Rating Curve= 0
Exp/Cntr=.3,.1

Type RM Length L Ch R = 1 ,661     ,87.5,87.5,87.5
XS GIS Cut Line= 2
      5310355.02     15924355.81      5310499.34     15924534.02
#Sta/Elev= 16
       0  40.486  59.285  41.404  72.014  37.631  88.583  35.105  92.913  31.037
  97.146  29.495  118.34  28.084 136.385  28.314 141.273  31.365 143.668  34.285
 151.312  36.778 179.757   39.14 184.547  40.846 198.163  41.306  207.48  40.092
 229.331  39.993
#Mann= 3 , 0 , 0
       0    .035       0       0    .035       0 229.331    .035       0
Bank Sta=0,229.331
XS Rating Curve= 0
Exp/Cntr=.3,.1

Type RM Length L Ch R = 1 ,660     ,81.529,81.529,81.529
XS GIS Cut Line= 2
      5310293.57     15924424.57      5310448.98     15924603.38
#Sta/Elev= 19
       0  40.157  46.325  41.437  55.479  41.109  61.581  38.681  74.278  37.795
  81.726  33.629  83.629  31.824  90.715  29.429 111.549  28.084  128.97  28.314
 132.612  31.857 138.451  36.024 147.572  37.369 159.744  36.713 170.702  37.106
 182.185  40.584 192.126  41.043 196.391  39.403 236.909    39.6
#Mann= 3 , 0 , 0
       0    .035       0       0    .035       0 236.909    .035       0
Bank Sta=0,236.909
XS Rating Curve= 0
Exp/Cntr=.3,.1

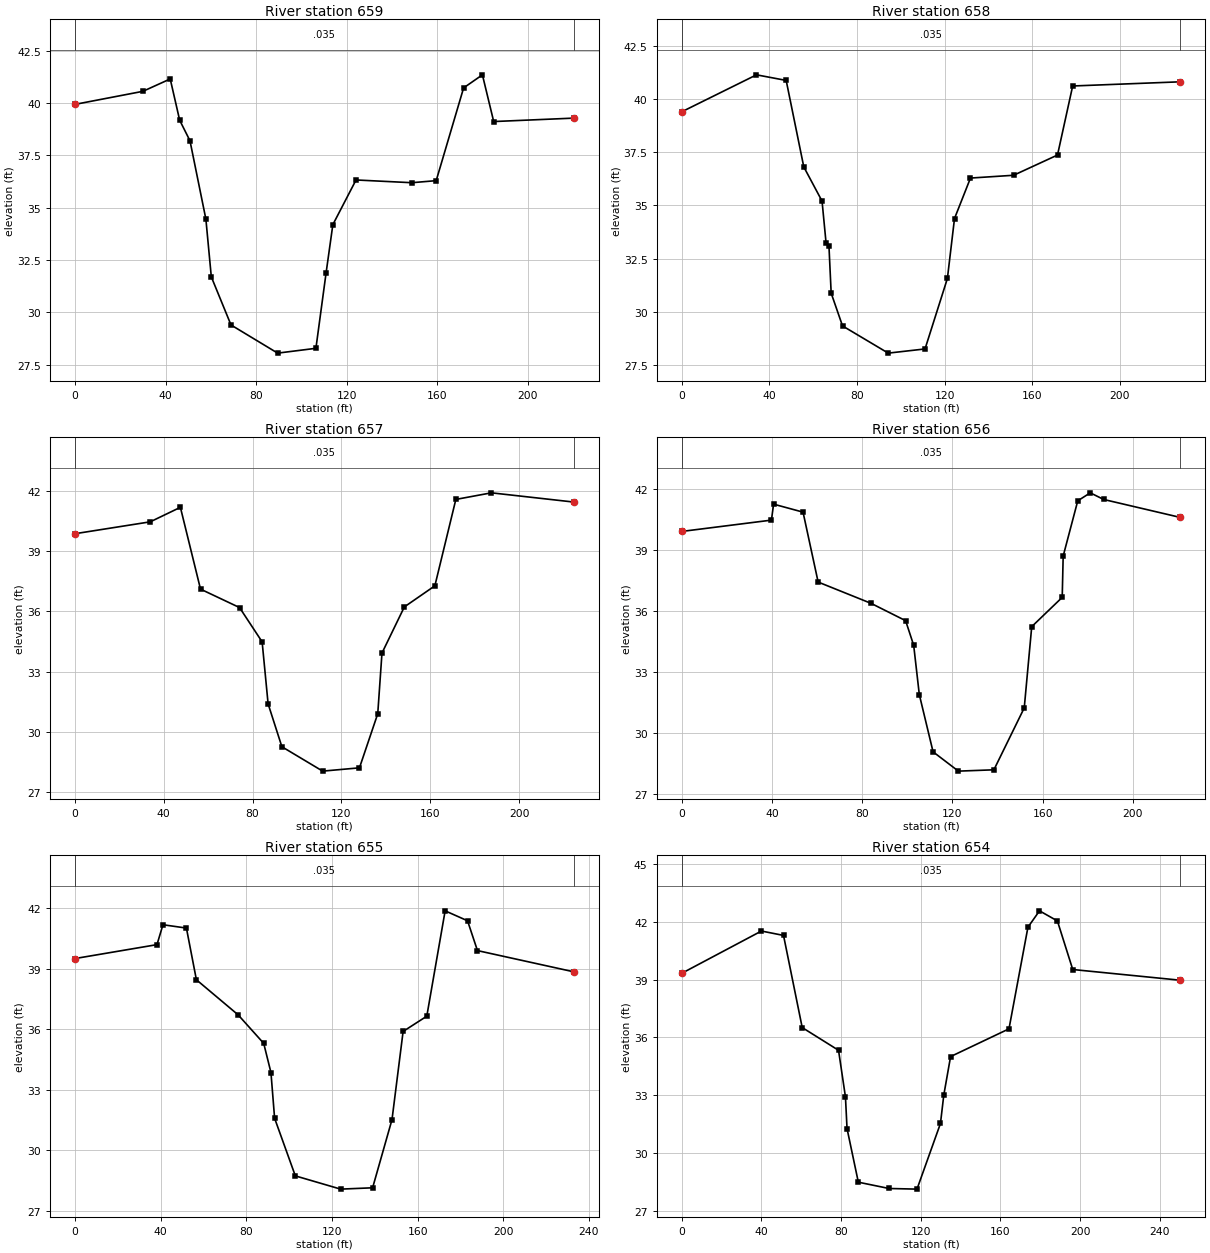
Type RM Length L Ch R = 1 ,659     ,85.531,85.531,85.531
XS GIS Cut Line= 2
      5310247.28     15924500.07      5310397.47     15924661.15
#Sta/Elev= 19
       0  39.928  29.987  40.551   42.06  41.142  46.227  39.173  50.787  38.189
  57.808  34.449  60.203  31.693  68.898  29.396  89.501  28.051 106.398  28.281
  110.86  31.857 113.878  34.186 124.114  36.319  148.72  36.188 159.514  36.286
 171.621  40.715 179.921  41.339 184.908  39.108 220.243  39.272
#Mann= 3 , 0 , 0
       0    .035       0       0    .035       0 220.243    .035       0
Bank Sta=0,220.243
XS Rating Curve= 0
Exp/Cntr=.3,.1

Type RM Length L Ch R = 1 ,658     ,93.668,93.668,93.668
XS GIS Cut Line= 2
      5310192.49     15924547.57      5310323.06     15924734.06
#Sta/Elev= 18
       0  39.403  34.121  41.142  47.671  40.879  55.709  36.811  64.042  35.203
  65.879  33.235  67.192  33.104  68.209  30.873  73.392  29.331  94.259  28.051
 111.056  28.248  121.26  31.562 124.508  34.383 131.791  36.286 151.476  36.417
 171.522  37.369 178.445  40.617 227.657  40.814
#Mann= 3 , 0 , 0
       0    .035       0       0    .035       0 227.657    .035       0
Bank Sta=0,227.657
XS Rating Curve= 0
Exp/Cntr=.3,.1

Type RM Length L Ch R = 1 ,657     ,80.184,80.184,80.184
XS GIS Cut Line= 2
      5310111.45     15924600.07      5310246.62     15924779.46
#Sta/Elev= 17
       0  39.862  33.891  40.453  47.474  41.175  56.529  37.106  74.114  36.188
  84.285  34.482  86.975  31.398  93.176  29.265 111.549  28.051 128.117  28.215
 136.352  30.906 138.255  33.924 148.327   36.22 162.074   37.27 171.522  41.568
 187.533  41.896 224.606  41.437
#Mann= 3 , 0 , 0
       0    .035       0       0    .035       0 224.606    .035       0
Bank Sta=0,224.606
XS Rating Curve= 0
Exp/Cntr=.3,.1

Type RM Length L Ch R = 1 ,656     ,116.404,116.404,116.404
XS GIS Cut Line= 2
      5310055.45     15924618.64      5310152.36     15924817.36
#Sta/Elev= 20
       0  39.928  39.764  40.486  40.715  41.273  53.773  40.879  60.466  37.434
  83.924  36.385  99.245  35.531 102.822  34.318 105.315   31.89 111.417  29.068
 122.638  28.117 138.386  28.182 151.837  31.234 155.151  35.236 168.668   36.68
 169.094  38.714 175.558  41.437 181.102  41.831 187.073  41.503 221.096  40.617
#Mann= 3 , 0 , 0
       0    .035       0       0    .035       0 221.096    .035       0
Bank Sta=0,221.096
XS Rating Curve= 0
Exp/Cntr=.3,.1

Type RM Length L Ch R = 1 ,655     ,87.762,87.762,87.762
XS GIS Cut Line= 2
      5309935.37     15924686.06      5310072.24     15924874.44
#Sta/Elev= 19
       0  39.501  38.287   40.19  41.076  41.175  52.034   41.01  56.693  38.451
  76.181  36.713  88.123  35.302  91.503  33.858  93.209  31.594 102.887   28.74
 124.049  28.084 138.976   28.15 148.031  31.529 153.215  35.892 164.272  36.647
 172.835  41.864 183.301  41.371 187.926  39.895 232.874  38.845
#Mann= 3 , 0 , 0
       0    .035       0       0    .035       0 232.874    .035       0
Bank Sta=0,232.874
XS Rating Curve= 0
Exp/Cntr=.3,.1

Type RM Length L Ch R = 1 ,654     ,116.667,116.667,116.667
XS GIS Cut Line= 2
       5309858.3     15924756.86       5310035.4     15924933.96
#Sta/Elev= 19
       0  39.337  40.026  41.535  51.115  41.306  60.499  36.516   78.74  35.335
  82.218  32.907  83.005  31.266  88.681  28.478 104.101   28.15 118.143  28.117
 129.921  31.529 131.594  33.005 135.007  35.007 164.337   36.45 173.852  41.732
 179.659  42.585 188.648   42.06 196.358  39.534 250.459  38.976
#Mann= 3 , 0 , 0
       0    .035       0       0    .035       0 250.459    .035       0
Bank Sta=0,250.459
XS Rating Curve= 0
Exp/Cntr=.3,.1