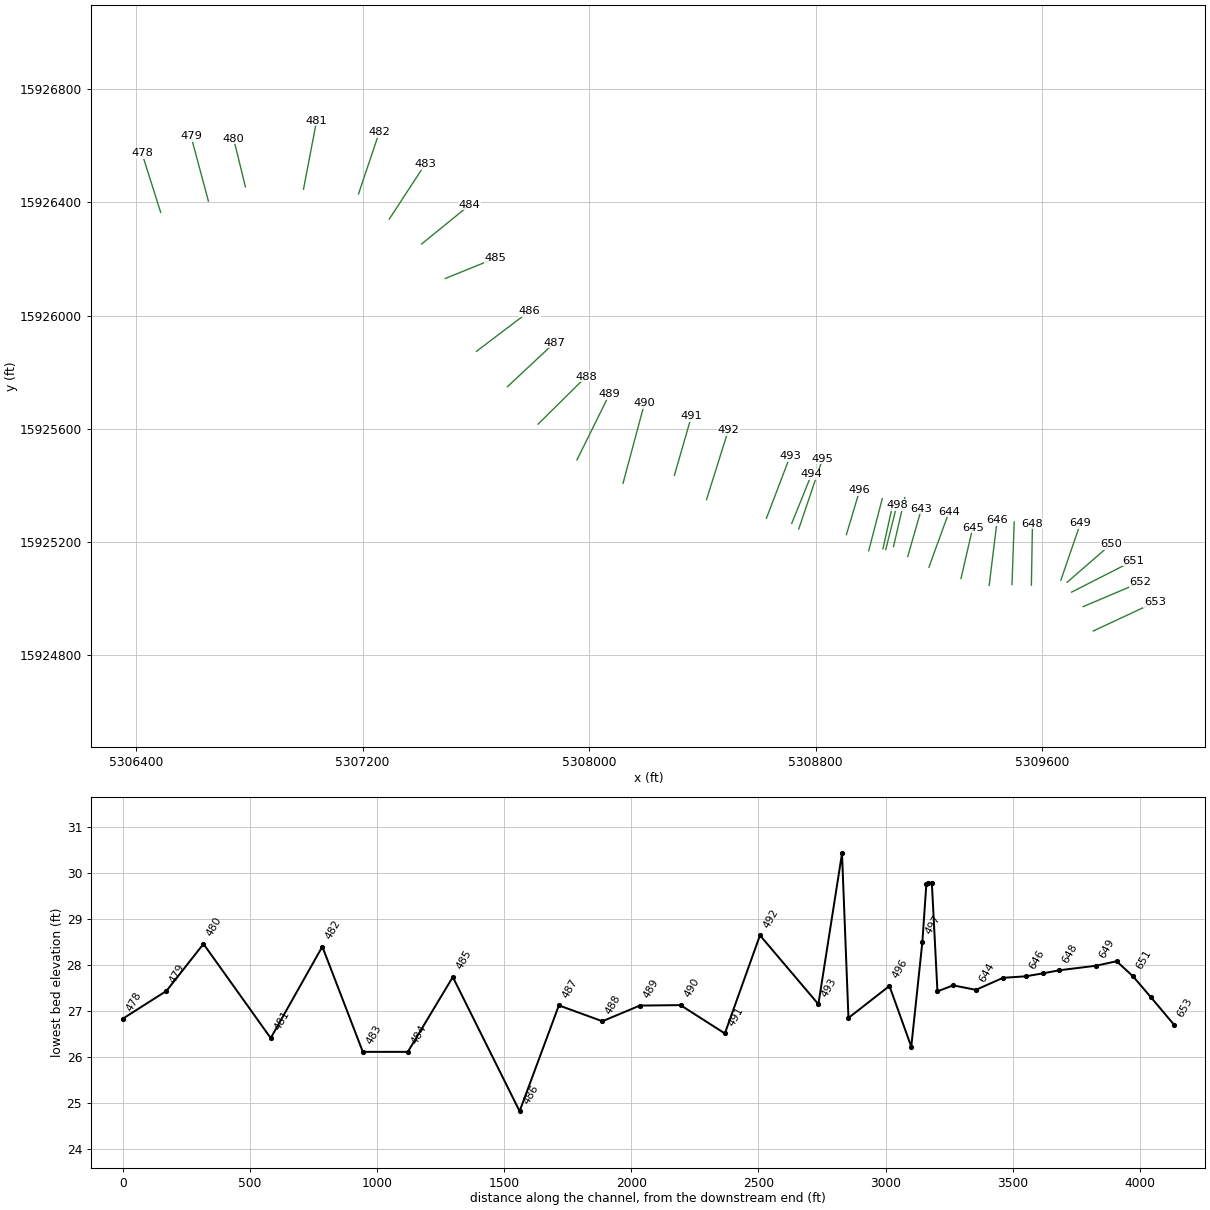
HEC-RAS study ozz_def.prj: ozzeri

--- ozz_def.g04 (geometry) --- (continued)

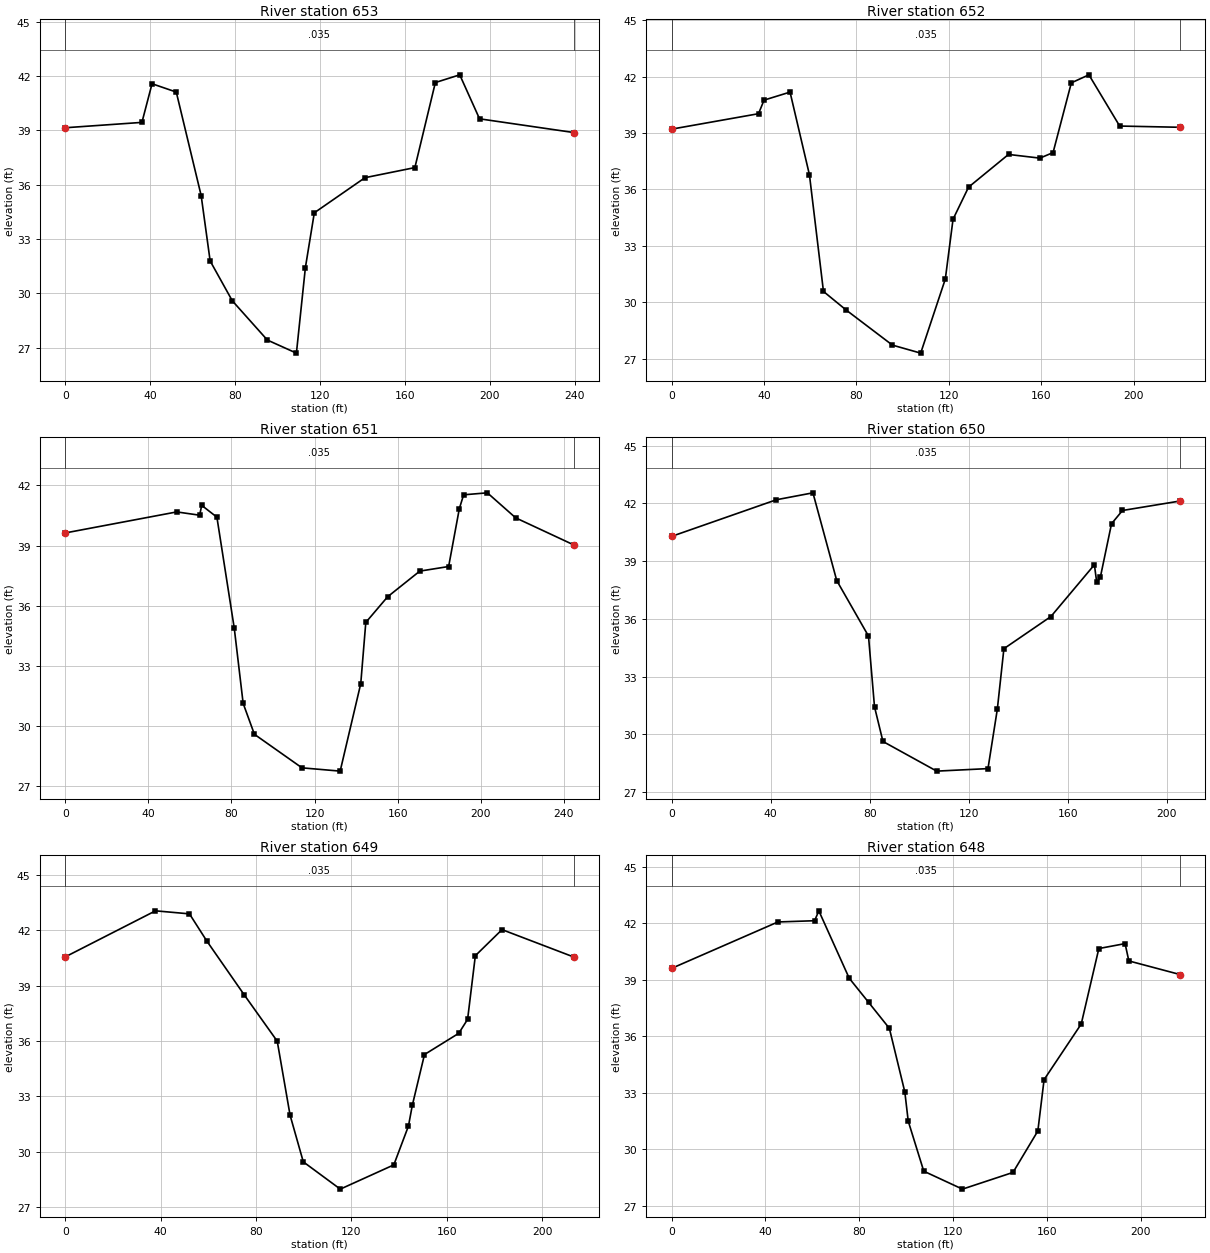
Type RM Length L Ch R = 1 ,653     ,89.829,89.829,89.829
XS GIS Cut Line= 2
      5309780.31     15924886.55      5309997.24      15924987.7
#Sta/Elev= 17
       0   39.14  36.122  39.436  40.879  41.568  52.297  41.109  64.009    35.4
  68.241  31.791  78.675  29.593  95.177  27.428 108.858  26.706 113.091   31.43
  117.29  34.449 141.142  36.385 164.633  36.942 174.278  41.634 185.761   42.06
 195.079  39.633 239.337  38.878
#Mann= 3 , 0 , 0
       0    .035       0       0    .035       0 239.337    .035       0
Bank Sta=0,239.337
XS Rating Curve= 0
Exp/Cntr=.3,.1

Type RM Length L Ch R = 1 ,652     ,71.063,71.063,71.063
XS GIS Cut Line= 2
      5309744.32     15924972.38      5309946.92     15925058.37
#Sta/Elev= 19
       0  39.206  37.598  40.026  39.993  40.748  51.247  41.175  59.646  36.778
  65.715  30.577  75.492  29.593  95.571  27.723 107.808  27.297 118.471  31.234
 121.818  34.416 128.543  36.122 145.833  37.861 159.416  37.664 165.125  37.959
 173.031  41.667 180.643  42.093 193.963   39.37 220.079  39.304
#Mann= 3 , 0 , 0
       0    .035       0       0    .035       0 220.079    .035       0
Bank Sta=0,220.079
XS Rating Curve= 0
Exp/Cntr=.3,.1

Type RM Length L Ch R = 1 ,651     ,64.501,64.501,64.501
XS GIS Cut Line= 2
      5309703.67     15925023.69      5309921.62     15925134.74
#Sta/Elev= 20
       0  39.633  53.675  40.682  64.698  40.518  65.682   41.01  72.999   40.42
  81.365  34.875   85.63  31.135  91.043  29.593 113.944   27.92 132.316  27.756
 142.224  32.119 144.652  35.171 155.151   36.45 170.636   37.73 184.514  37.959
 189.665  40.846 191.732  41.535  203.15  41.634 216.765  40.387 244.619  39.042
#Mann= 3 , 0 , 0
       0    .035       0       0    .035       0 244.619    .035       0
Bank Sta=0,244.619
XS Rating Curve= 0
Exp/Cntr=.3,.1

Type RM Length L Ch R = 1 ,650     ,80.774,80.774,80.774
XS GIS Cut Line= 2
      5309687.86     15925058.53      5309842.81     15925193.21
#Sta/Elev= 18
       0  40.289   42.29  42.192  57.054  42.552  66.667  37.992  79.495  35.105
  81.923   31.43  85.335  29.626 107.054  28.084 127.756  28.215 131.529  31.299
 134.186  34.449 153.182  36.122 170.735  38.812 171.686  37.894  173.13  38.156
 177.657  40.945 182.087  41.634 205.315  42.126
#Mann= 3 , 0 , 0
       0    .035       0       0    .035       0 205.315    .035       0
Bank Sta=0,205.315
XS Rating Curve= 0
Exp/Cntr=.3,.1

Type RM Length L Ch R = 1 ,649     ,144.685,144.685,144.685
XS GIS Cut Line= 2
      5309665.55     15925065.58      5309734.97     15925267.13
#Sta/Elev= 18
       0  40.551  37.861  43.045    52.1  42.881  59.416  41.404  74.967  38.517
  88.911  35.991  94.291  31.988  99.836  29.462 115.354  27.986 137.795  29.298
  143.93  31.398 145.538  32.513 150.656  35.269 165.026  36.417 168.734  37.172
 171.982  40.617 183.169  42.028 213.156  40.551
#Mann= 3 , 0 , 0
       0    .035       0       0    .035       0 213.156    .035       0
Bank Sta=0,213.156
XS Rating Curve= 0
Exp/Cntr=.3,.1

Type RM Length L Ch R = 1 ,648     ,62.205,62.205,62.205
XS GIS Cut Line= 2
      5309561.58     15925048.46      5309565.35     15925265.22
#Sta/Elev= 19
       0    39.6  45.308   42.06  60.958  42.126  62.762  42.651  75.722  39.075
   83.99  37.795  92.848  36.417  99.442  33.038 100.886  31.496 107.513  28.839
 124.016  27.887 145.571  28.773 156.168  30.971 158.825  33.694 174.672  36.647
 182.185   40.65 193.373  40.912  194.98  39.993 216.798  39.272
#Mann= 3 , 0 , 0
       0    .035       0       0    .035       0 216.798    .035       0
Bank Sta=0,216.798
XS Rating Curve= 0
Exp/Cntr=.3,.1

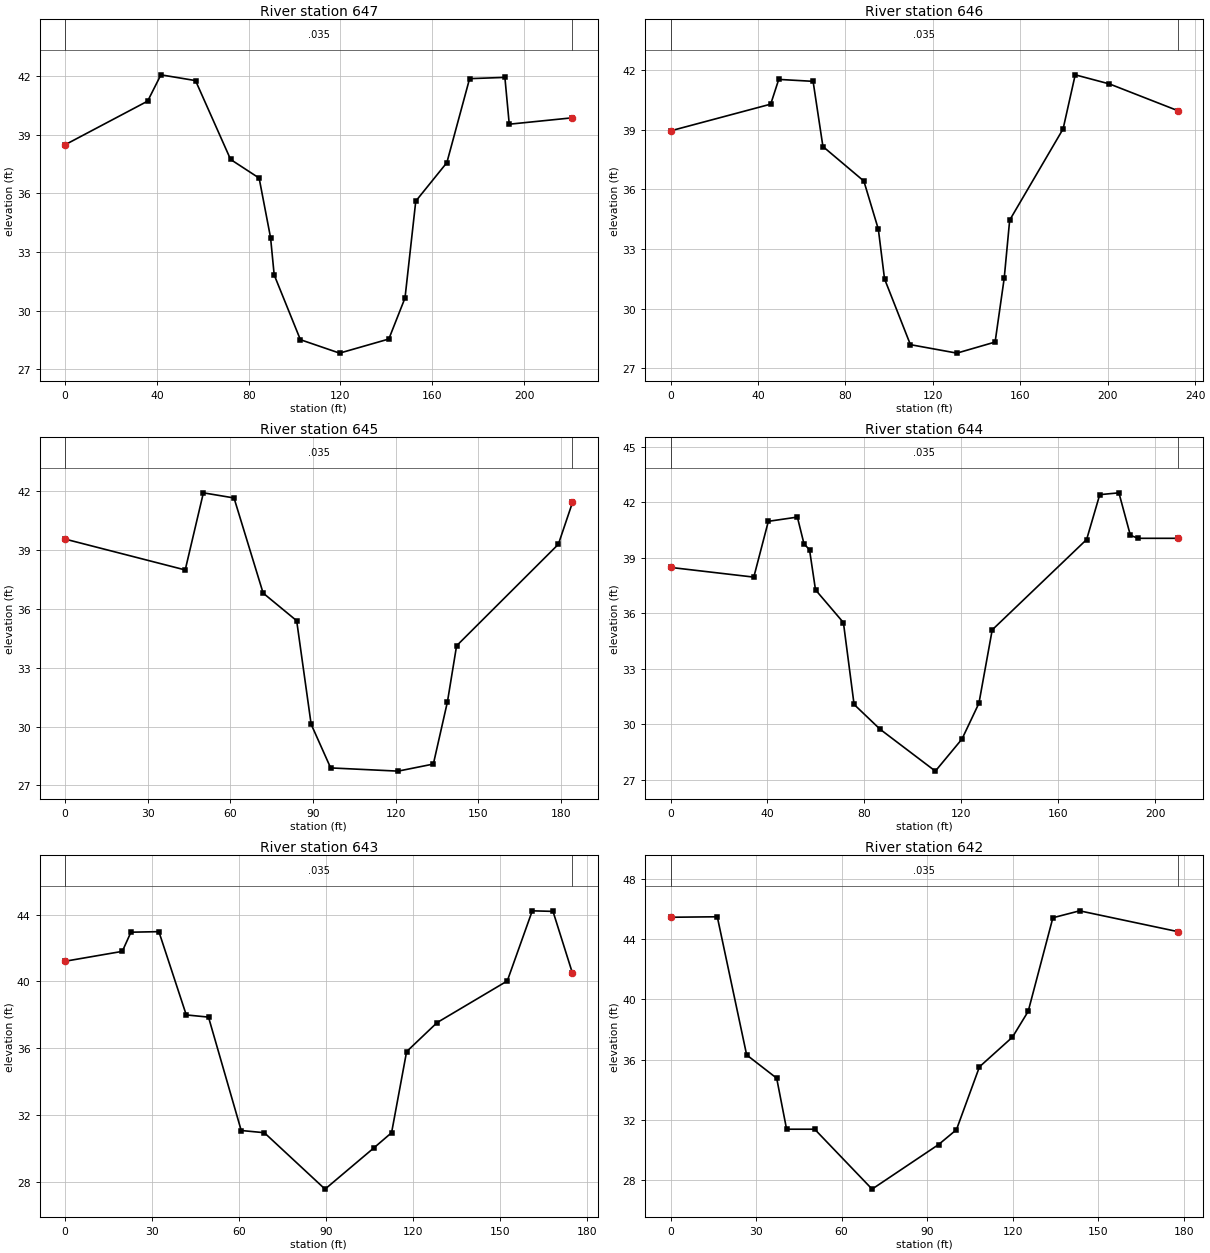
Type RM Length L Ch R = 1 ,647     ,69.357,69.357,69.357
XS GIS Cut Line= 2
      5309493.11     15925050.43      5309500.82     15925271.42
#Sta/Elev= 18
       0  38.484  35.958  40.715  41.732   42.06  56.824  41.765  72.113   37.73
  84.547  36.778  89.534  33.727  91.109  31.824 102.526   28.51 119.619  27.822
 141.076  28.543  148.13  30.643 152.822  35.597 166.371  37.566  176.28  41.864
 191.667  41.929  193.57  39.534 221.129  39.862
#Mann= 3 , 0 , 0
       0    .035       0       0    .035       0 221.129    .035       0
Bank Sta=0,221.129
XS Rating Curve= 0
Exp/Cntr=.3,.1

Type RM Length L Ch R = 1 ,646     ,89.567,89.567,89.567
XS GIS Cut Line= 2
      5309412.47     15925047.51      5309440.75     15925277.85
#Sta/Elev= 17
       0  38.944  45.833  40.289  49.508  41.535  65.223  41.437  69.718  38.156
  88.451  36.417  95.079   33.99    97.9  31.496 109.744  28.182 131.004  27.756
 148.491  28.314 152.657  31.529 155.151  34.449 179.593  39.042 185.138  41.765
  200.82  41.306 232.087  39.961
#Mann= 3 , 0 , 0
       0    .035       0       0    .035       0 232.087    .035       0
Bank Sta=0,232.087
XS Rating Curve= 0
Exp/Cntr=.3,.1

Type RM Length L Ch R = 1 ,645     ,106.66,106.66,106.66
XS GIS Cut Line= 2
      5309313.02     15925071.78      5309354.43     15925251.18
#Sta/Elev= 14
       0  39.567   43.57  37.992  50.164  41.929  61.286  41.667   71.85  36.811
  84.022    35.4  89.272  30.118  96.358  27.887 120.833  27.723 133.629  28.084
 138.747  31.266  142.06  34.121 179.003  39.304 184.121  41.437
#Mann= 3 , 0 , 0
       0    .035       0       0    .035       0 184.121    .035       0
Bank Sta=0,184.121
XS Rating Curve= 0
Exp/Cntr=.3,.1

Type RM Length L Ch R = 1 ,644     ,89.567,89.567,89.567
XS GIS Cut Line= 2
      5309199.77     15925111.68      5309271.36     15925308.33
#Sta/Elev= 20
       0  38.484   34.35  37.959  40.354  40.978  52.329  41.207  55.052  39.764
  57.349  39.436   59.81   37.27  71.325  35.499  75.722   31.07  86.483  29.724
 109.252  27.461 120.243  29.199 127.231  31.135  132.71  35.105 171.654  39.993
 177.067  42.421 184.974   42.52 189.698  40.223 192.881  40.059 209.285  40.059
#Mann= 3 , 0 , 0
       0    .035       0       0    .035       0 209.285    .035       0
Bank Sta=0,209.285
XS Rating Curve= 0
Exp/Cntr=.3,.1

Type RM Length L Ch R = 1 ,643     ,61.713,61.713,61.713
XS GIS Cut Line= 2
      5309124.93     15925149.25       5309173.2     15925317.55
#Sta/Elev= 17
       0  41.207  19.718  41.798  22.703  42.946  32.349  42.979  41.798  37.992
  49.475  37.861  60.761   31.07  68.734  30.938  89.698  27.559 106.496   30.02
 112.664  30.938 117.848  35.794 128.379  37.533 152.592  40.026  161.22  44.226
 168.373  44.193 175.098  40.486
#Mann= 3 , 0 , 0
       0    .035       0       0    .035       0 175.098    .035       0
Bank Sta=0,175.098
XS Rating Curve= 0
Exp/Cntr=.3,.1

Type RM Length L Ch R = 1 ,642     ,22.014,22.014,22.014
XS GIS Cut Line= 2
      5309074.67     15925184.15       5309114.7     15925357.55
#Sta/Elev= 15
       0   45.44  16.404  45.472  26.706  36.319  37.238  34.777  40.715  31.398
  50.558  31.398  70.702  27.428  94.029  30.381 100.295  31.365 108.366  35.531
 119.948    37.5 125.459  39.206 134.121  45.407 143.504  45.866 177.953  44.488
#Mann= 3 , 0 , 0
       0    .035       0       0    .035       0 177.953    .035       0
Bank Sta=0,177.953
XS Rating Curve= 0
Exp/Cntr=.3,.1

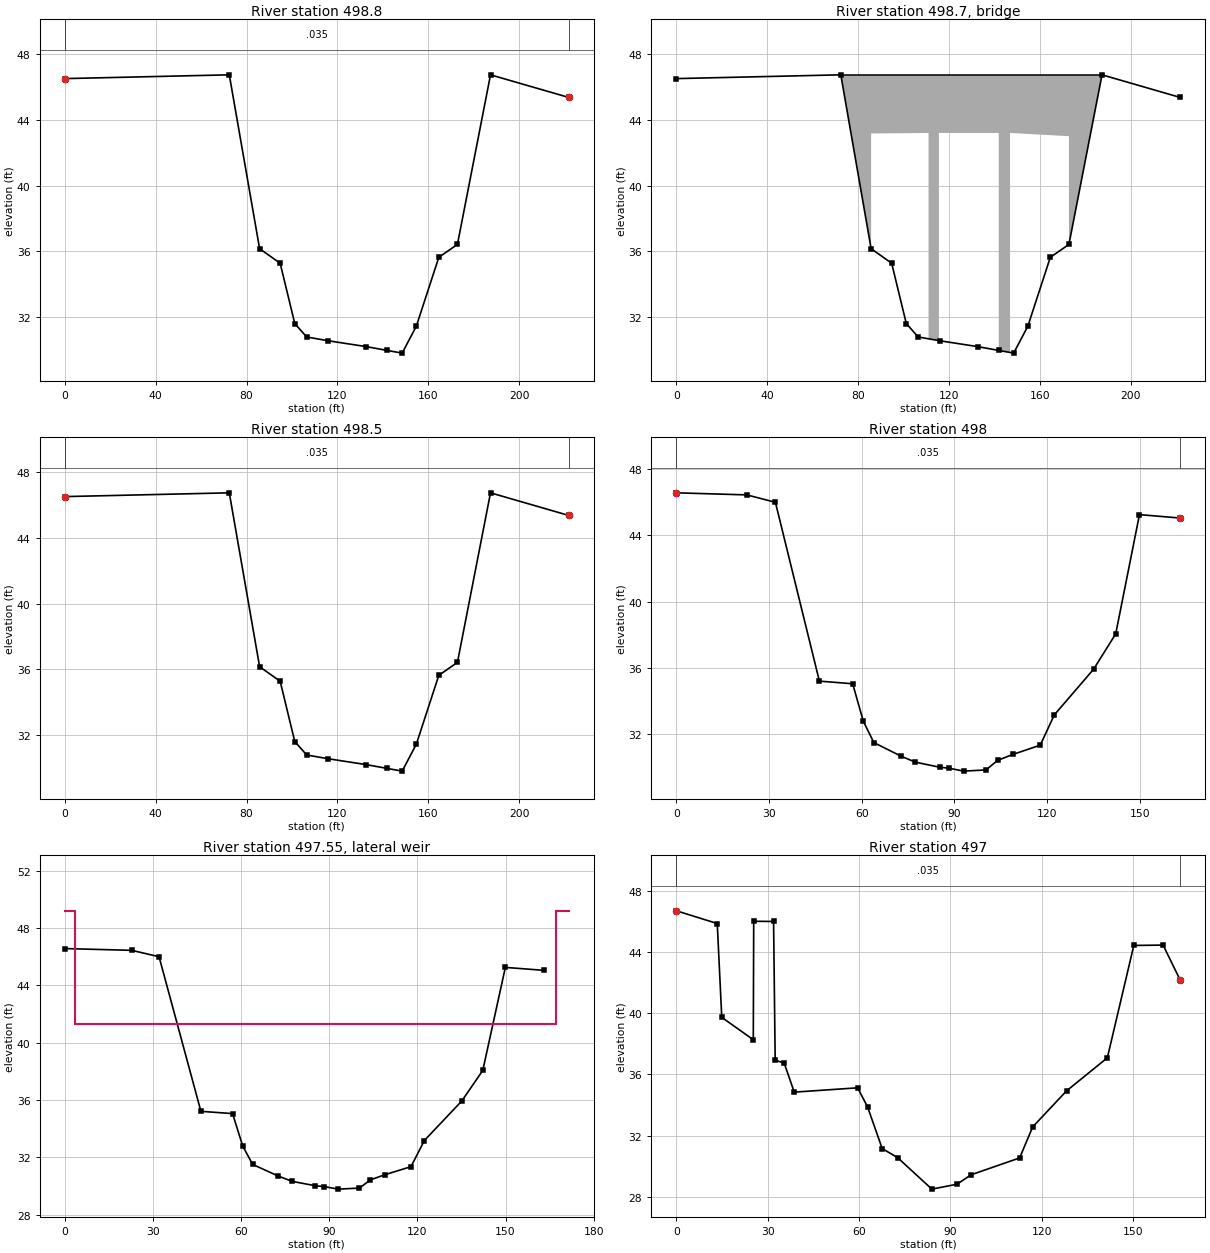
Type RM Length L Ch R = 1 ,498.8   ,16.404,16.404,16.404
#Sta/Elev= 15
       0  46.522  72.375  46.752  85.728  36.155  94.783  35.269 101.214  31.594
 106.463  30.774 115.912  30.545 132.808  30.184 141.929  29.954 148.524   29.79
 154.757   31.43 164.665   35.63 172.867  36.417 187.434  46.752 221.883  45.374
#Mann= 3 , 0 , 0
       0    .035       0       0    .035       0 221.883    .035       0
Bank Sta=0,221.883
XS Rating Curve= 0
Exp/Cntr=.3,.1

Type RM Length L Ch R = 3 ,498.7   ,,,
BEGIN DESCRIPTION:
Ponte Salissimo
END DESCRIPTION:
Bridge Culvert--1,0,-1,-1, 0
Deck Dist Width WeirC Skew NumUp NumDn MinLoCord MaxHiCord MaxSubmerge Is_Ogee
1.64,13.123,2.61,0, 14, 14, , , .95, 0, 0,0,,
  72.375  85.728  85.728 111.024 111.024 115.584 115.584 141.929 141.929 146.916
 146.916 172.867 172.867 187.434
  46.752  46.752  46.752  46.752  46.752  46.752  46.752  46.752  46.752  46.752
  46.752  46.752  46.752  46.752
  46.752  36.155  43.176  43.209  30.676  30.545  43.209  43.209  29.954  29.823
  43.209  43.012  36.417  46.752
  72.375  85.728  85.728 111.024 111.024 115.584 115.584 141.929 141.929 146.916
 146.916 172.867 172.867 187.434
  46.752  46.752  46.752  46.752  46.752  46.752  46.752  46.752  46.752  46.752
  46.752  46.752  46.752  46.752
  46.752  36.155  43.176  43.209  30.676  30.545  43.209  43.209  29.954  29.823
  43.209  43.012  36.417  46.752
BR Coef=-1 , 0 , 0 ,1.25, 0 ,,,.8,-1,2,0,
WSPro=,,,, 1 ,,,, 0 ,,,, 0 ,,,,-1 ,-1 ,-1 , 0 , 0 , 0 , 0 , 0
BC Design=,, 0 ,, 0 ,,,,,,
BC HTab Sub Flow Pts= 40

Type RM Length L Ch R = 1 ,498.5   ,5.085,5.085,5.085
#Sta/Elev= 15
       0  46.522  72.375  46.752  85.728  36.155  94.783  35.269 101.214  31.594
 106.463  30.774 115.912  30.545 132.808  30.184 141.929  29.954 148.524   29.79
 154.757   31.43 164.665   35.63 172.867  36.417 187.434  46.752 221.883  45.374
#Mann= 3 , 0 , 0
       0    .035       0       0    .035       0 221.883    .035       0
Bank Sta=0,221.883
XS Rating Curve= 0
Exp/Cntr=.3,.1

Type RM Length L Ch R = 1 ,498     ,15.781,15.781,15.781
XS GIS Cut Line= 3
      5309047.47     15925174.15      5309086.65     15925331.04
      5309086.65     15925331.04
#Sta/Elev= 21
       0  46.575  22.762   46.45  32.031  46.004  46.276  35.207  57.054  35.049
  60.509  32.785  63.901  31.499   72.69  30.679  77.369  30.315  85.226   30.01
  88.343  29.948  93.018  29.774 100.233  29.846 103.993  30.423 108.921  30.781
 117.799  31.342 122.352  33.169 135.075  35.925 142.238  38.061 149.928  45.259
  163.13  45.052
#Mann= 3 , 0 , 0
       0    .035       0       0    .035       0  163.13    .035       0
Bank Sta=0,163.13
XS Rating Curve= 0
Exp/Cntr=.3,.1

Type RM Length L Ch R = 6 ,497.55  ,,,
Lateral Weir Pos= 3
Lateral Weir End=                ,                ,        ,c05
Lateral Weir Distance=3.281
Lateral Weir WD=9.843
Lateral Weir Coef=3.01
Lateral Weir Is Ogee= 0
Lateral Weir WSCriteria=-1
Lateral Weir SE= 6
       0   49.21    3.28   49.21    3.28   41.31  167.25   41.31  167.25   49.21
   171.5   49.21

Type RM Length L Ch R = 1 ,497     ,43.668,43.668,43.668
XS GIS Cut Line= 2
       5309037.4     15925176.64      5309073.06      15925337.3
#Sta/Elev= 23
       0  46.673  13.392  45.843  14.872  39.718   25.23  38.258  25.367  45.991
  31.896  45.978  32.418  36.919  35.377  36.736  38.678  34.836  59.501  35.118
  62.779  33.868  67.569  31.155   72.68  30.554  83.881  28.504  92.129  28.822
  96.739  29.436 112.726  30.541 117.018  32.566 128.136  34.918 141.539  37.077
 150.233  44.413 159.862  44.436 165.482  42.146
#Mann= 3 , 0 , 0
       0    .035       0       0    .035       0 165.482    .035       0
Bank Sta=0,165.482
XS Rating Curve= 0
Exp/Cntr=.3,.1

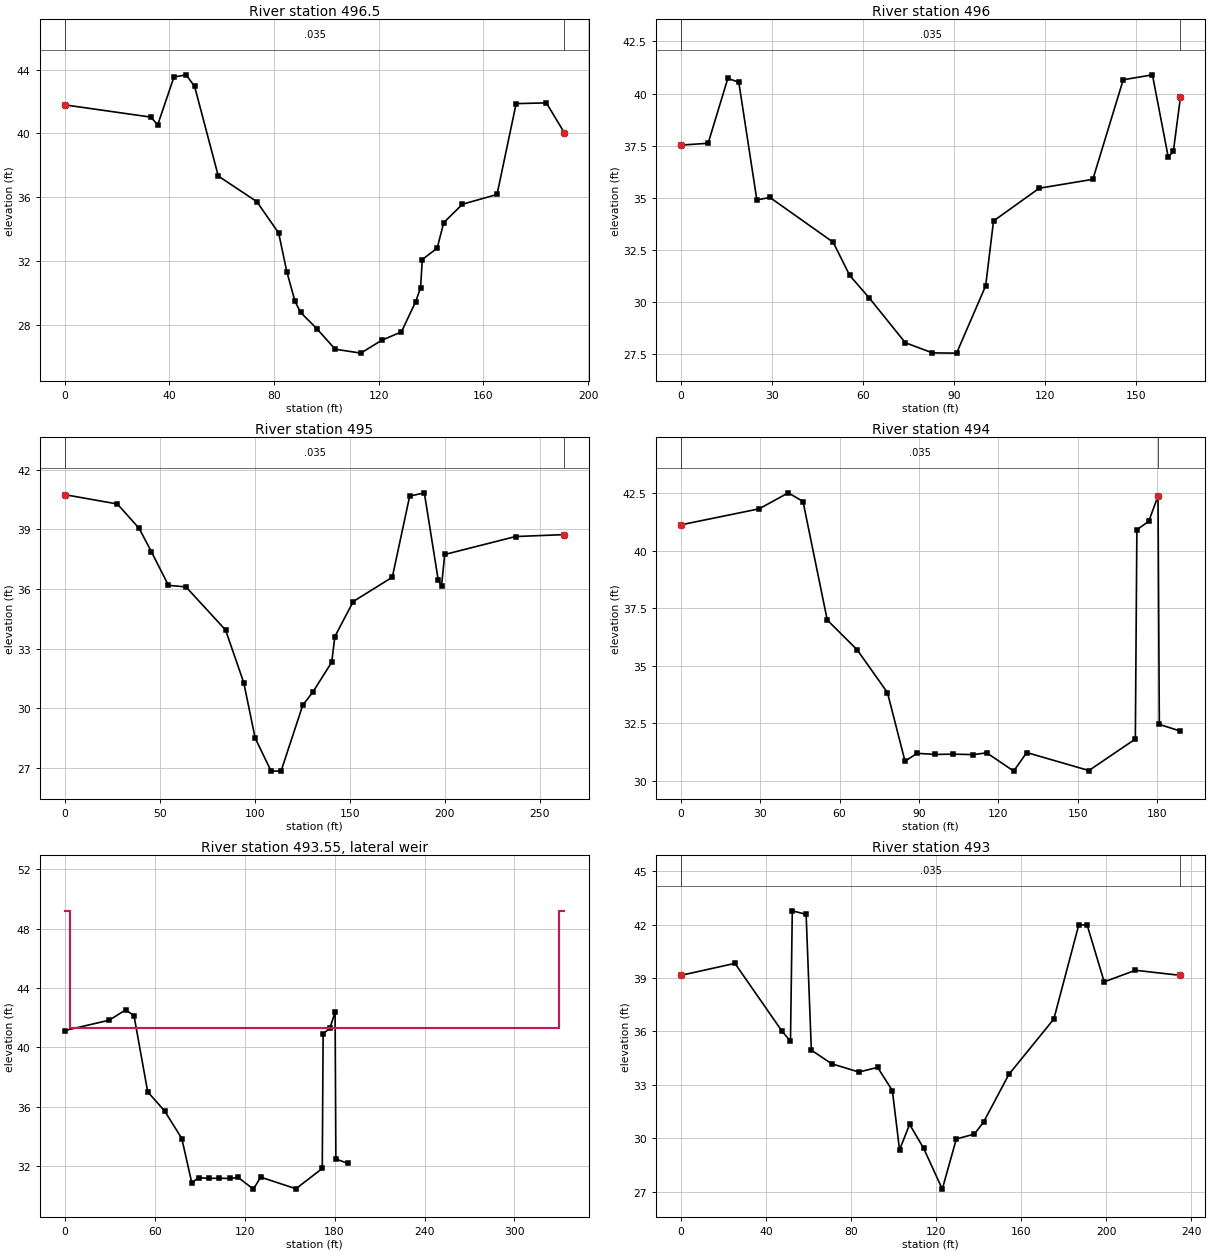
Type RM Length L Ch R = 1 ,496.5   ,85.86,85.86,85.86
XS GIS Cut Line= 2
      5308987.01     15925169.23      5309034.97     15925353.48
#Sta/Elev= 27
       0  41.785   32.92  41.017  35.502  40.528  41.719  43.527  46.365  43.668
  49.623   42.94  58.671  37.323  73.389  35.719  81.739  33.753  84.852  31.332
  87.972  29.475  90.108   28.78   96.44  27.736  103.34   26.47 113.166  26.224
 121.047  27.024 128.668  27.556 134.108  29.455 135.974  30.318 136.631   32.09
 142.326  32.808  144.82  34.403 151.985  35.558 165.194  36.168   172.5  41.864
 184.049  41.909 190.912  40.039
#Mann= 3 , 0 , 0
       0    .035       0       0    .035       0 190.912    .035       0
Bank Sta=0,190.912
XS Rating Curve= 0
Exp/Cntr=.3,.1

Type RM Length L Ch R = 1 ,496     ,161.155,161.155,161.155
XS GIS Cut Line= 2
      5308908.37      15925226.8      5308955.54     15925384.28
#Sta/Elev= 21
       0  37.526   8.983  37.612  15.479  40.722  19.098  40.545  25.062  34.895
  29.377  35.013  50.226  32.867  55.705   31.27  62.116  30.197  74.032  28.045
  82.982  27.559  90.951  27.546 100.541  30.774  103.13  33.885 118.202  35.456
 135.899  35.883 145.919  40.659 155.554  40.896 160.768  36.952 162.451  37.221
 164.793   39.82
#Mann= 3 , 0 , 0
       0    .035       0       0    .035       0 164.793    .035       0
Bank Sta=0,164.793
XS Rating Curve= 0
Exp/Cntr=.3,.1

Type RM Length L Ch R = 1 ,495     ,25.394,25.394,25.394
XS GIS Cut Line= 3
      5308740.12     15925246.72      5308824.28     15925494.91
      5308824.28     15925494.91
#Sta/Elev= 24
       0  40.748  27.684  40.279  39.154  39.049  45.627  37.871  54.567  36.188
  63.766  36.112  84.613  33.944  94.186  31.296  100.18  28.514 108.576   26.85
 113.822  26.854  125.22  30.161 130.682  30.846 140.469  32.326 142.133  33.615
 151.811  35.377 172.356  36.598 181.493  40.673 189.206   40.84 196.555  36.434
 198.268  36.168 199.918   37.74 237.208  38.642 262.871   38.74
#Mann= 3 , 0 , 0
       0    .035       0       0    .035       0 262.871    .035       0
Bank Sta=0,262.871
XS Rating Curve= 0
Exp/Cntr=.3,.1

Type RM Length L Ch R = 1 ,494     ,92.881,92.881,92.881
XS GIS Cut Line= 2
      5308715.26     15925266.17      5308785.76     15925440.45
#Sta/Elev= 22
       0  41.132   29.56  41.827  40.607  42.523  46.168  42.146  55.328  36.995
  66.631  35.702  78.087  33.842  84.724   30.86  89.278  31.204  96.237  31.155
 103.041  31.168 110.499  31.148  115.63  31.224  125.82   30.43 130.715  31.237
 154.229  30.456 171.791  31.824 172.372  40.922 176.847  41.283 180.358  42.382
  180.86  32.461 188.839  32.169
#Mann= 3 , 0 , 0
       0    .035       0       0    .035       0 180.358    .035       0
Bank Sta=0,180.358
XS Rating Curve= 0
Exp/Cntr=.3,.1

Type RM Length L Ch R = 6 ,493.55  ,,,
Lateral Weir Pos= 0
Lateral Weir End=                ,                ,        ,c06
Lateral Weir Distance=3.281
Lateral Weir WD=9.843
Lateral Weir Coef=3.01
Lateral Weir Is Ogee= 0
Lateral Weir WSCriteria=-1
Lateral Weir SE= 6
       0   49.21    3.28   49.21    3.28   41.31     330   41.31     330   49.21
  333.28   49.21

Type RM Length L Ch R = 1 ,493     ,229.79,229.79,229.79
XS GIS Cut Line= 2
      5308625.92     15925284.38      5308709.42     15925503.02
#Sta/Elev= 25
       0  39.147   25.41   39.82  47.382  36.043  51.532  35.443  52.385  42.769
  58.885  42.572  61.345  34.951  70.879  34.186   83.73   33.72  92.497  33.983
  99.439   32.68 102.812  29.354 107.552  30.784 114.154  29.439 122.913  27.149
 129.518  29.964 138.028   30.24 142.349  30.919 154.291  33.599 175.361  36.696
   187.1  41.985 191.033  41.969 199.049  38.783 213.727  39.432 234.895  39.147
#Mann= 3 , 0 , 0
       0    .035       0       0    .035       0 234.895    .035       0
Bank Sta=0,234.895
XS Rating Curve= 0
Exp/Cntr=.3,.1

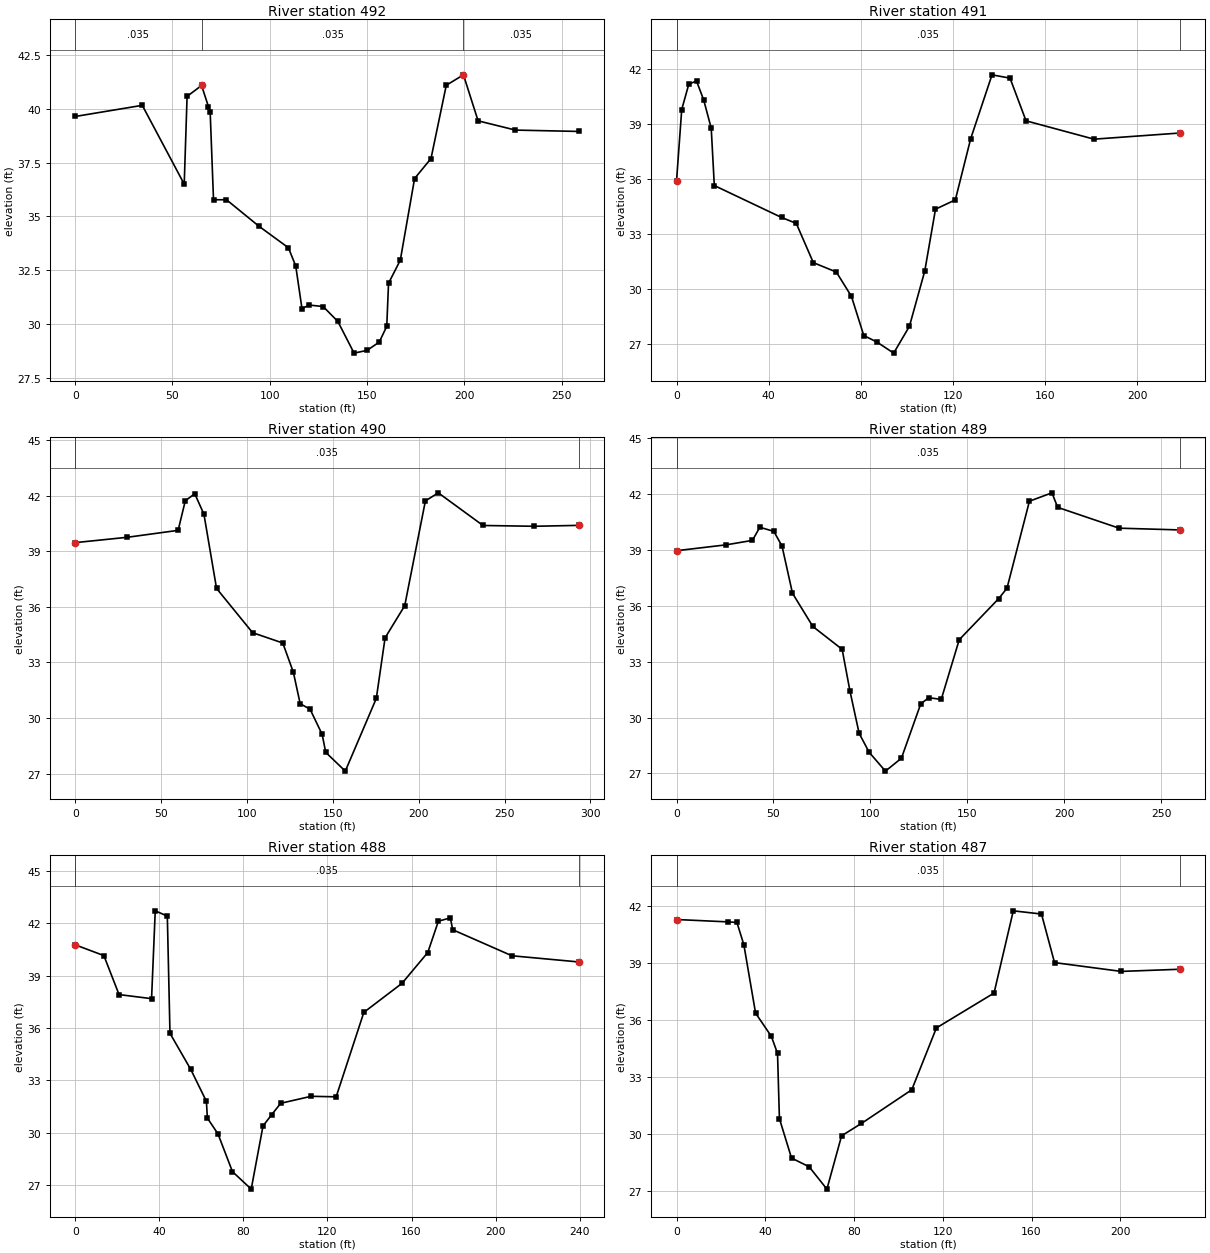
Type RM Length L Ch R = 1 ,492     ,138.091,138.091,138.091
XS GIS Cut Line= 2
       5308414.4     15925350.26      5308491.63       15925596.
#Sta/Elev= 29
       0  39.649  34.465  40.167   56.03  36.503  57.503  40.584  64.957  41.089
  68.481  40.108  69.367  39.865  71.089  35.778  77.756  35.778  94.347  34.554
 109.583  33.547 113.363  32.697 116.568  30.715 120.236  30.883 127.451  30.814
 135.003  30.121 143.346  28.648  150.01  28.776 156.276   29.16 160.144  29.892
 161.063  31.896  167.11  32.969 174.455  36.765 182.894  37.694 190.738  41.099
 199.567  41.585   207.1  39.446 226.325  39.016 258.917  38.953
#Mann= 3 , 0 , 0
       0    .035       0  64.957    .035       0 199.567    .035       0
Bank Sta=64.957,199.567
XS Rating Curve= 0
Exp/Cntr=.3,.1

Type RM Length L Ch R = 1 ,491     ,174.442,174.442,174.442
XS GIS Cut Line= 2
      5308300.98     15925435.96      5308361.42     15925645.41
#Sta/Elev= 25
       0  35.919   2.241   39.79   5.322  41.175   8.671  41.342  11.785  40.308
  15.052  38.773  16.398  35.646  45.584  33.907  51.998  33.583    59.4  31.444
  69.386  30.932  75.955  29.606  81.319   27.47  87.073  27.113  94.304  26.512
 101.145  27.976 107.802  30.988 112.464  34.357 121.086  34.865 127.743  38.196
 137.014   41.68 144.839  41.499 151.785  39.173 181.316  38.173 218.763   38.51
#Mann= 3 , 0 , 0
       0    .035       0       0    .035       0 218.763    .035       0
Bank Sta=0,218.763
XS Rating Curve= 0
Exp/Cntr=.3,.1

Type RM Length L Ch R = 1 ,490     ,160.072,160.072,160.072
XS GIS Cut Line= 2
      5308119.69     15925407.97      5308195.34     15925690.26
#Sta/Elev= 23
       0  39.459  30.328  39.747  59.918  40.121  64.094  41.719  69.606  42.096
  74.954  40.988  82.287  36.988 103.268    34.6 120.856  34.042 127.014  32.464
 130.981  30.768 136.749  30.469  143.77  29.114  145.86  28.143 157.257  27.129
 175.325  31.056  180.42  34.321 191.864  36.056 203.888  41.709 211.398  42.146
 237.444  40.384 267.241  40.341 293.274   40.39
#Mann= 3 , 0 , 0
       0    .035       0       0    .035       0 293.274    .035       0
Bank Sta=0,293.274
XS Rating Curve= 0
Exp/Cntr=.3,.1

Type RM Length L Ch R = 1 ,489     ,147.178,147.178,147.178
XS GIS Cut Line= 3
      5307956.92     15925490.52      5308071.62     15925722.11
      5308071.62     15925722.11
#Sta/Elev= 25
       0  38.967  25.581  39.281  39.157  39.521  42.959  40.226  50.174  40.007
  54.409  39.219  59.826  36.677  70.315  34.895  85.449  33.665  89.491  31.417
  94.203  29.154  99.373  28.133 107.789  27.119 116.033  27.812 126.001  30.732
 130.144  31.066 136.591  30.974 145.876  34.183  166.27  36.394 170.522  36.952
 182.096  41.627 193.714  42.077 196.673  41.296 228.363  40.177 259.921  40.082
#Mann= 3 , 0 , 0
       0    .035       0       0    .035       0 259.921    .035       0
Bank Sta=0,259.921
XS Rating Curve= 0
Exp/Cntr=.3,.1

Type RM Length L Ch R = 1 ,488     ,171.129,171.129,171.129
XS GIS Cut Line= 2
      5307819.59     15925616.67      5307988.94     15925784.22
#Sta/Elev= 26
       0  40.758  13.632  40.141  20.846   37.91  36.319  37.677  38.071  42.703
  43.816  42.402  45.082  35.692  54.951  33.632  62.411  31.801  62.874  30.843
   67.92  29.938  74.803  27.779  83.727  26.778  89.344  30.394  93.415   31.03
  97.759   31.69 112.254   32.09  124.14   32.06 137.313  36.893 155.486  38.556
  167.73  40.318 172.772   42.11 178.455  42.297   179.6  41.621 207.769  40.131
 239.623  39.777
#Mann= 3 , 0 , 0
       0    .035       0       0    .035       0 239.623    .035       0
Bank Sta=0,239.623
XS Rating Curve= 0
Exp/Cntr=.3,.1

Type RM Length L Ch R = 1 ,487     ,154.396,154.396,154.396
XS GIS Cut Line= 2
      5307711.75     15925749.21      5307877.36       15925904.
#Sta/Elev= 21
       0   41.27  23.323  41.145  27.215  41.115  30.338  39.944  35.617  36.358
  42.736  35.138  45.512  34.242  46.365  30.823  51.818  28.753  59.754  28.297
  67.772  27.123  74.386  29.921  83.317  30.568 106.027  32.336 117.133  35.581
  143.11  37.411 151.791  41.726 164.501  41.558 170.381  39.009 200.463  38.547
 227.047  38.661
#Mann= 3 , 0 , 0
       0    .035       0       0    .035       0 227.047    .035       0
Bank Sta=0,227.047
XS Rating Curve= 0
Exp/Cntr=.3,.1

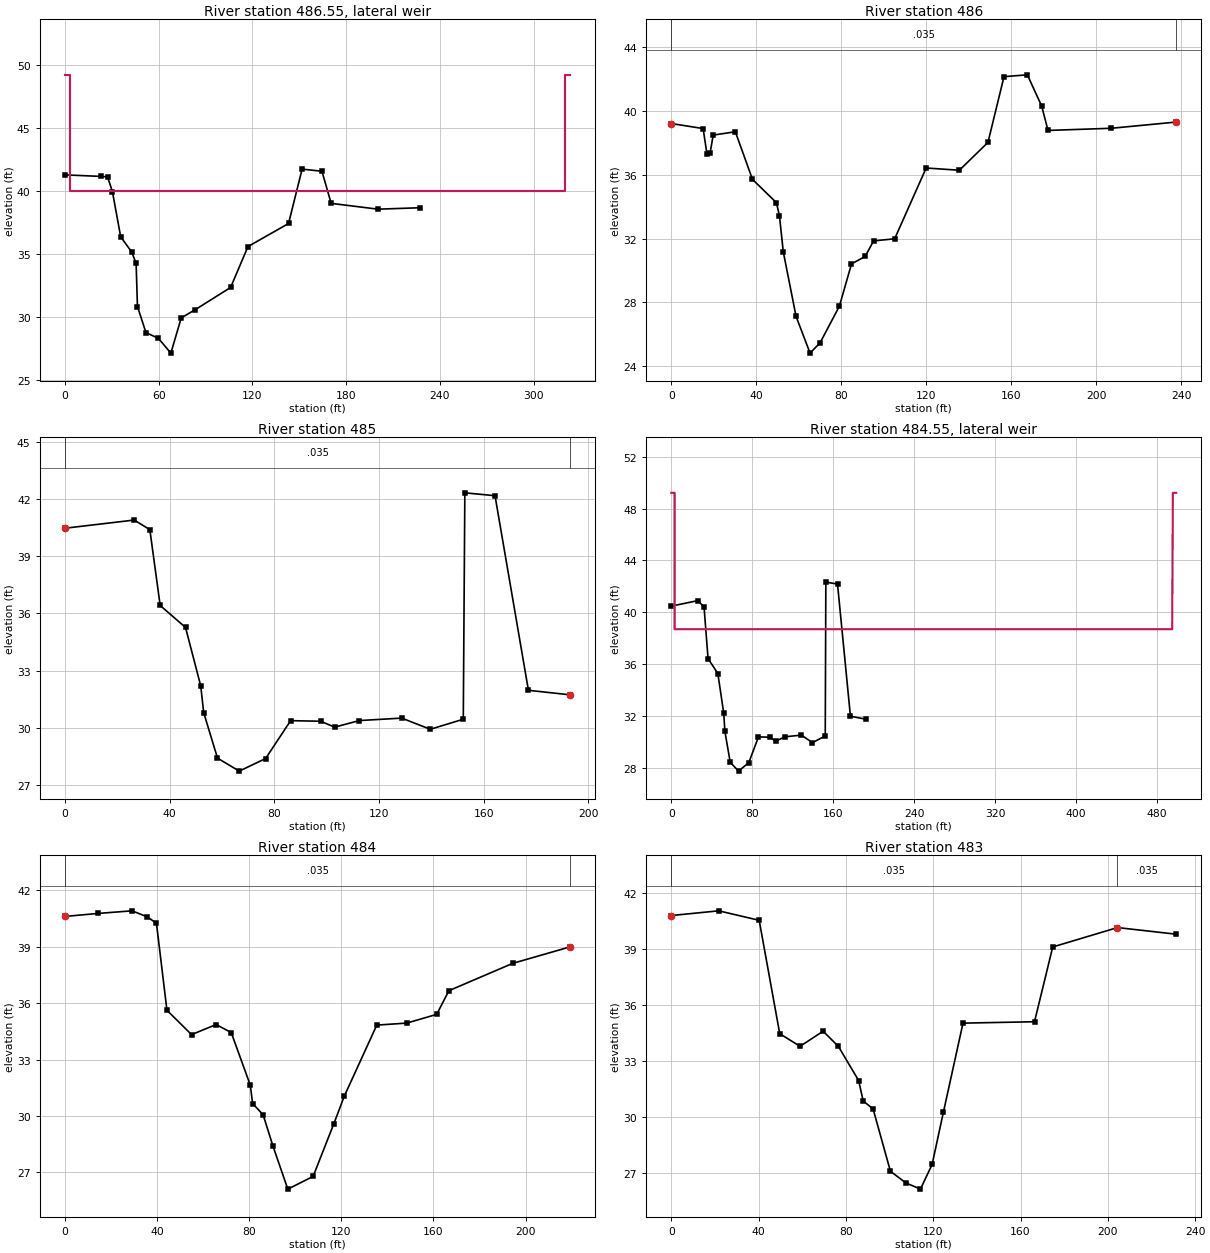
Type RM Length L Ch R = 6 ,486.55  ,,,
Lateral Weir Pos= 0
Lateral Weir End=                ,                ,        ,c04
Lateral Weir Distance=3.281
Lateral Weir WD=9.843
Lateral Weir Coef=3.01
Lateral Weir Is Ogee= 0
Lateral Weir WSCriteria=-1
Lateral Weir SE= 6
       0   49.21    3.28   49.21    3.28      40     320      40     320   49.21
  323.28   49.21

Type RM Length L Ch R = 1 ,486     ,262.73,262.73,262.73
XS GIS Cut Line= 3
        5307602.     15925873.85      5307790.29     15926016.47
      5307790.29     15926016.47
#Sta/Elev= 27
       0  39.203  14.993  38.888  16.795  37.277  18.225  37.336  19.741  38.478
  30.144  38.688  38.202  35.705  49.462  34.245  50.899  33.419  52.684  31.175
  58.711  27.119  65.299   24.82  70.016  25.469  79.101  27.762  84.783  30.407
  91.207  30.876  95.184   31.85 105.095  31.982 119.908  36.417 135.531  36.276
  148.99  38.022 156.535  42.139 167.523  42.254 174.281  40.292 177.228   38.77
 207.106  38.907 237.536  39.295
#Mann= 3 , 0 , 0
       0    .035       0       0    .035       0 237.536    .035       0
Bank Sta=0,237.536
XS Rating Curve= 0
Exp/Cntr=.3,.1

Type RM Length L Ch R = 1 ,485     ,176.969,176.969,176.969
XS GIS Cut Line= 3
      5307492.03      15926131.1      5307670.28     15926203.51
      5307670.28     15926203.51
#Sta/Elev= 21
       0  40.469   26.44  40.896  32.408  40.394  36.348  36.421  46.037  35.269
  51.854  32.205  52.972   30.81  58.251  28.422  66.562   27.74  76.637  28.399
  86.194  30.384  97.625  30.354 103.051  30.046 112.497   30.39 128.622  30.518
 139.573  29.934 152.172  30.459 152.769  42.323 164.298  42.172  177.06  31.975
 192.927  31.739
#Mann= 3 , 0 , 0
       0    .035       0       0    .035       0 192.927    .035       0
Bank Sta=0,192.927
XS Rating Curve= 0
Exp/Cntr=.3,.1

Type RM Length L Ch R = 6 ,484.55  ,,,
Lateral Weir Pos= 3
Lateral Weir End=                ,                ,        ,c05
Lateral Weir Distance=3.281
Lateral Weir WD=9.843
Lateral Weir Coef=3.01
Lateral Weir Is Ogee= 0
Lateral Weir WSCriteria=-1
Lateral Weir SE= 6
       0   49.21    3.28   49.21    3.28   38.69  495.08   38.69  495.68   49.21
     499   49.21

Type RM Length L Ch R = 1 ,484     ,177.001,177.001,177.001
XS GIS Cut Line= 3
       5307408.6     15926253.08      5307578.58     15926391.21
      5307578.58     15926391.21
#Sta/Elev= 23
       0  40.617  14.495  40.778  29.127  40.915  35.502  40.604  39.692  40.262
  44.252  35.627  54.941  34.331   65.61  34.865  72.169  34.442  80.479  31.631
  81.453  30.666  86.014  30.069  90.269  28.412  96.752  26.112  107.74  26.788
 116.732   29.59 121.309  31.066 135.384  34.836 148.409  34.944 161.411  35.407
 166.693  36.667 194.409   38.12 219.268  38.996
#Mann= 3 , 0 , 0
       0    .035       0       0    .035       0 219.268    .035       0
Bank Sta=0,219.268
XS Rating Curve= 0
Exp/Cntr=.3,.1

Type RM Length L Ch R = 1 ,483     ,159.252,159.252,159.252
XS GIS Cut Line= 3
      5307294.09     15926340.68      5307420.47     15926534.02
      5307420.47     15926534.02
#Sta/Elev= 20
       0  40.794  21.732  41.047  40.276  40.538  49.685  34.455  58.996  33.776
   69.58  34.587  76.565   33.77  85.837  31.939  87.923  30.843  92.454  30.417
 100.404   27.07 107.467  26.447  114.15  26.112 119.491  27.434 124.665   30.24
 133.645   35.02 166.404  35.095 174.757  39.108 204.419  40.148 231.309  39.793
#Mann= 3 , 0 , 0
       0    .035       0       0    .035       0 204.419    .035       0
Bank Sta=0,204.419
XS Rating Curve= 0
Exp/Cntr=.3,.1

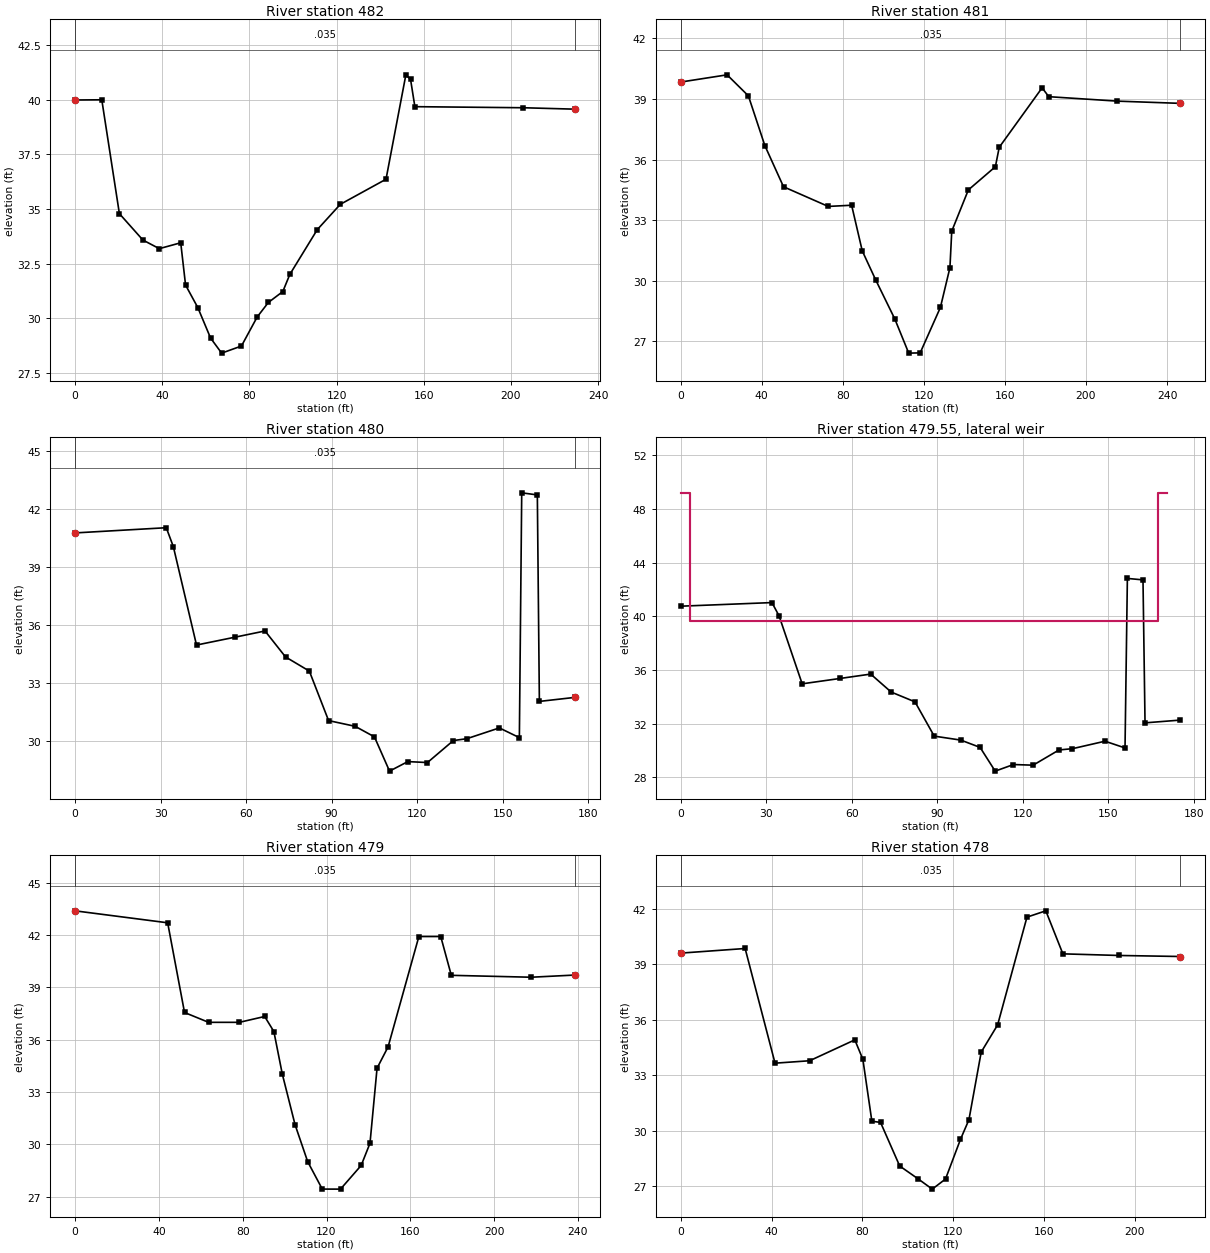
Type RM Length L Ch R = 1 ,482     ,202.953,202.953,202.953
XS GIS Cut Line= 2
       5307185.7     15926429.72       5307258.6     15926646.69
#Sta/Elev= 23
       0  39.984  12.277  39.993  20.354  34.783  31.142  33.576  38.665  33.182
  48.494  33.451  50.712  31.516  56.319  30.489  62.192  29.091  67.274  28.402
  76.352  28.727  83.573  30.056  88.688  30.719  95.335   31.22  98.537  32.001
 111.138  34.052 121.716   35.21  142.68  36.358 151.785  41.135 153.947  40.922
 155.922  39.678 205.633  39.629 229.282  39.564
#Mann= 3 , 0 , 0
       0    .035       0       0    .035       0 229.282    .035       0
Bank Sta=0,229.282
XS Rating Curve= 0
Exp/Cntr=.3,.1

Type RM Length L Ch R = 1 ,481     ,264.469,264.469,264.469
XS GIS Cut Line= 2
      5306991.31     15926446.26      5307037.66     15926688.06
#Sta/Elev= 22
       0  39.839  22.904  40.197  33.415  39.154  41.519  36.696  50.748  34.652
  72.818  33.678  84.357  33.737  89.603  31.476  96.152  30.056 105.682    28.1
  112.53  26.411 118.186  26.424 128.169  28.675 132.871  30.646 133.766  32.451
 141.952  34.495 155.302  35.646 157.201  36.608  178.36  39.554  181.65  39.114
 215.459  38.894 246.617  38.783
#Mann= 3 , 0 , 0
       0    .035       0       0    .035       0 246.617    .035       0
Bank Sta=0,246.617
XS Rating Curve= 0
Exp/Cntr=.3,.1

Type RM Length L Ch R = 1 ,480     ,145.571,145.571,145.571
XS GIS Cut Line= 3
      5306786.42      15926454.4      5306744.69     15926623.92
      5306744.69     15926623.92
#Sta/Elev= 22
       0  40.758  32.001  41.027  34.491  40.043  42.602   34.97  55.932  35.371
  66.634  35.696  73.816  34.357  82.175  33.625  88.921   31.07  98.248  30.774
 105.003   30.23 110.299  28.461 116.716  28.953 123.596  28.904 132.677  30.039
 137.405  30.135 148.812  30.692  155.83   30.19 156.657  42.828 162.133   42.72
 162.848   32.06 175.262  32.267
#Mann= 3 , 0 , 0
       0    .035       0       0    .035       0 175.262    .035       0
Bank Sta=0,175.262
XS Rating Curve= 0
Exp/Cntr=.3,.1

Type RM Length L Ch R = 6 ,479.55  ,,,
Lateral Weir Pos= 0
Lateral Weir End=                ,                ,        ,c04
Lateral Weir Distance=3.281
Lateral Weir WD=9.843
Lateral Weir Coef=3.01
Lateral Weir Is Ogee= 0
Lateral Weir WSCriteria=-1
Lateral Weir SE= 6
       0   49.21    3.28   49.21    3.28   39.67  167.32   39.67  167.32   49.21
   170.6   49.21

Type RM Length L Ch R = 1 ,479     ,171.654,171.654,171.654
XS GIS Cut Line= 2
      5306655.54      15926404.3      5306593.96     15926634.15
#Sta/Elev= 21
       0  43.389  44.209  42.703  52.247  37.562  63.747  36.998  78.406  36.998
  90.499  37.333  94.885   36.47  98.907  34.032  104.99  31.132  111.01  29.016
 117.972  27.441 126.683  27.438 136.545  28.796 140.751  30.069 144.121   34.37
  149.39  35.594 164.072  41.916 174.514  41.916 179.551  39.692  217.68  39.583
 238.468  39.708
#Mann= 3 , 0 , 0
       0    .035       0       0    .035       0 238.468    .035       0
Bank Sta=0,238.468
XS Rating Curve= 0
Exp/Cntr=.3,.1

Type RM Length L Ch R = 1 ,478     ,150.722,150.722,150.722
XS GIS Cut Line= 3
      5306487.04     15926364.63      5306420.87     15926573.85
      5306420.87     15926573.85
#Sta/Elev= 21
       0  39.596  28.376  39.846  41.535  33.645  56.775  33.776   76.66  34.905
  80.203  33.855  84.173  30.505  87.982  30.443  96.424  28.084 104.639  27.379
 110.755  26.834 116.588  27.379 123.176  29.524 126.903  30.587 132.306  34.245
 139.537  35.715 152.451  41.542 160.748  41.883 168.258  39.557 192.894  39.469
 220.016  39.413
#Mann= 3 , 0 , 0
       0    .035       0       0    .035       0 220.016    .035       0
Bank Sta=0,220.016
XS Rating Curve= 0
Exp/Cntr=.3,.1