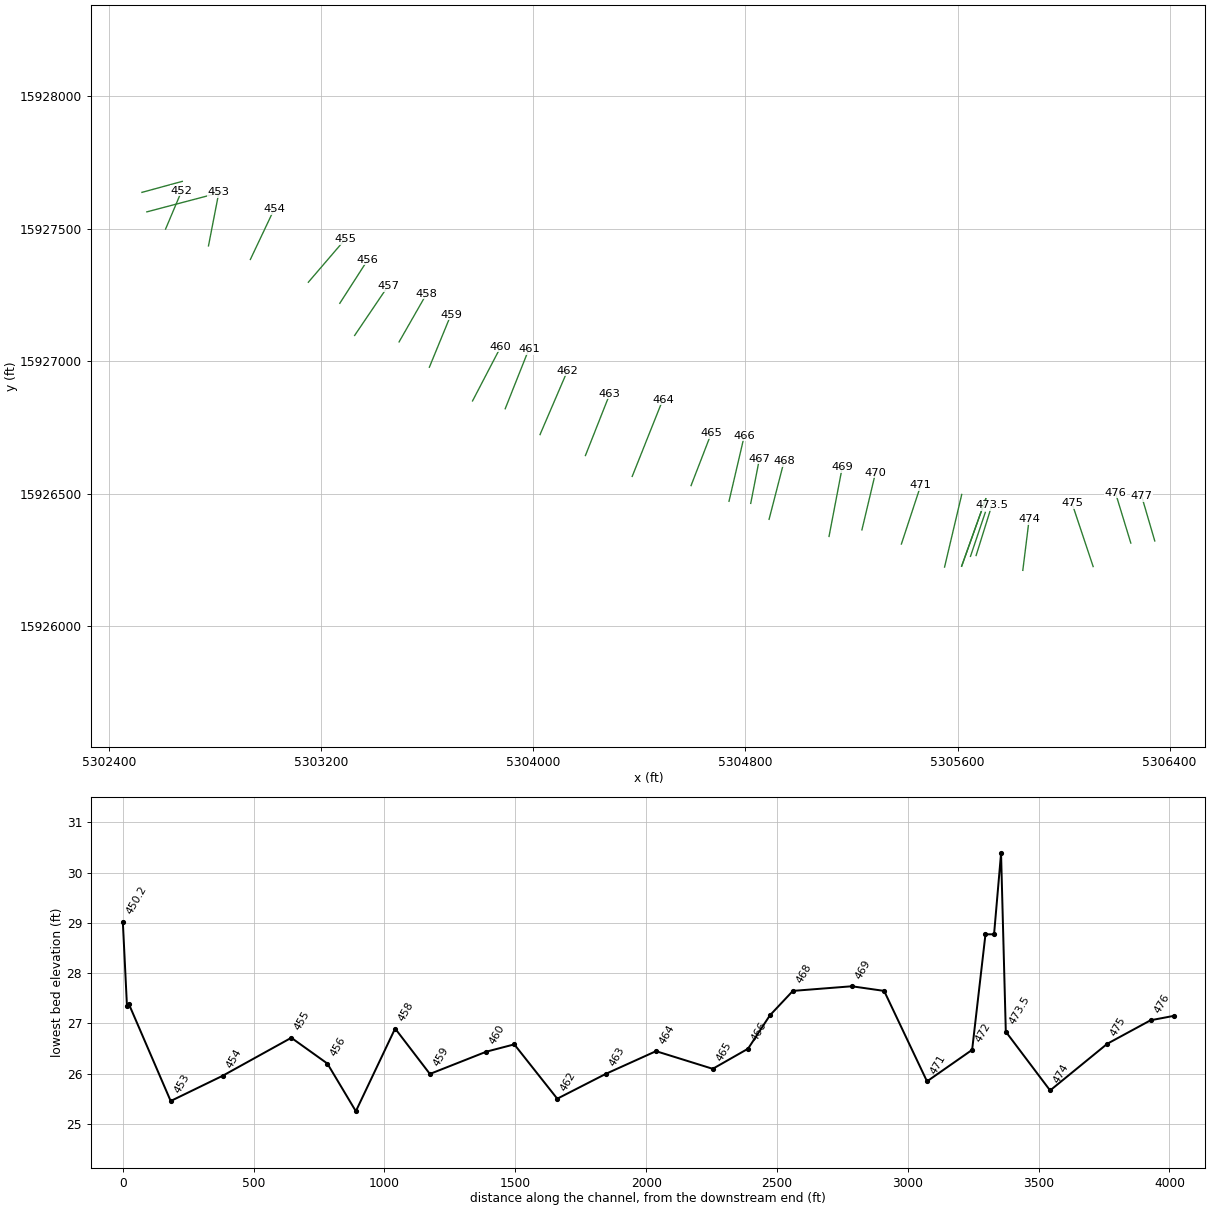
HEC-RAS study ozz_def.prj: ozzeri

--- ozz_def.g04 (geometry) --- (continued)

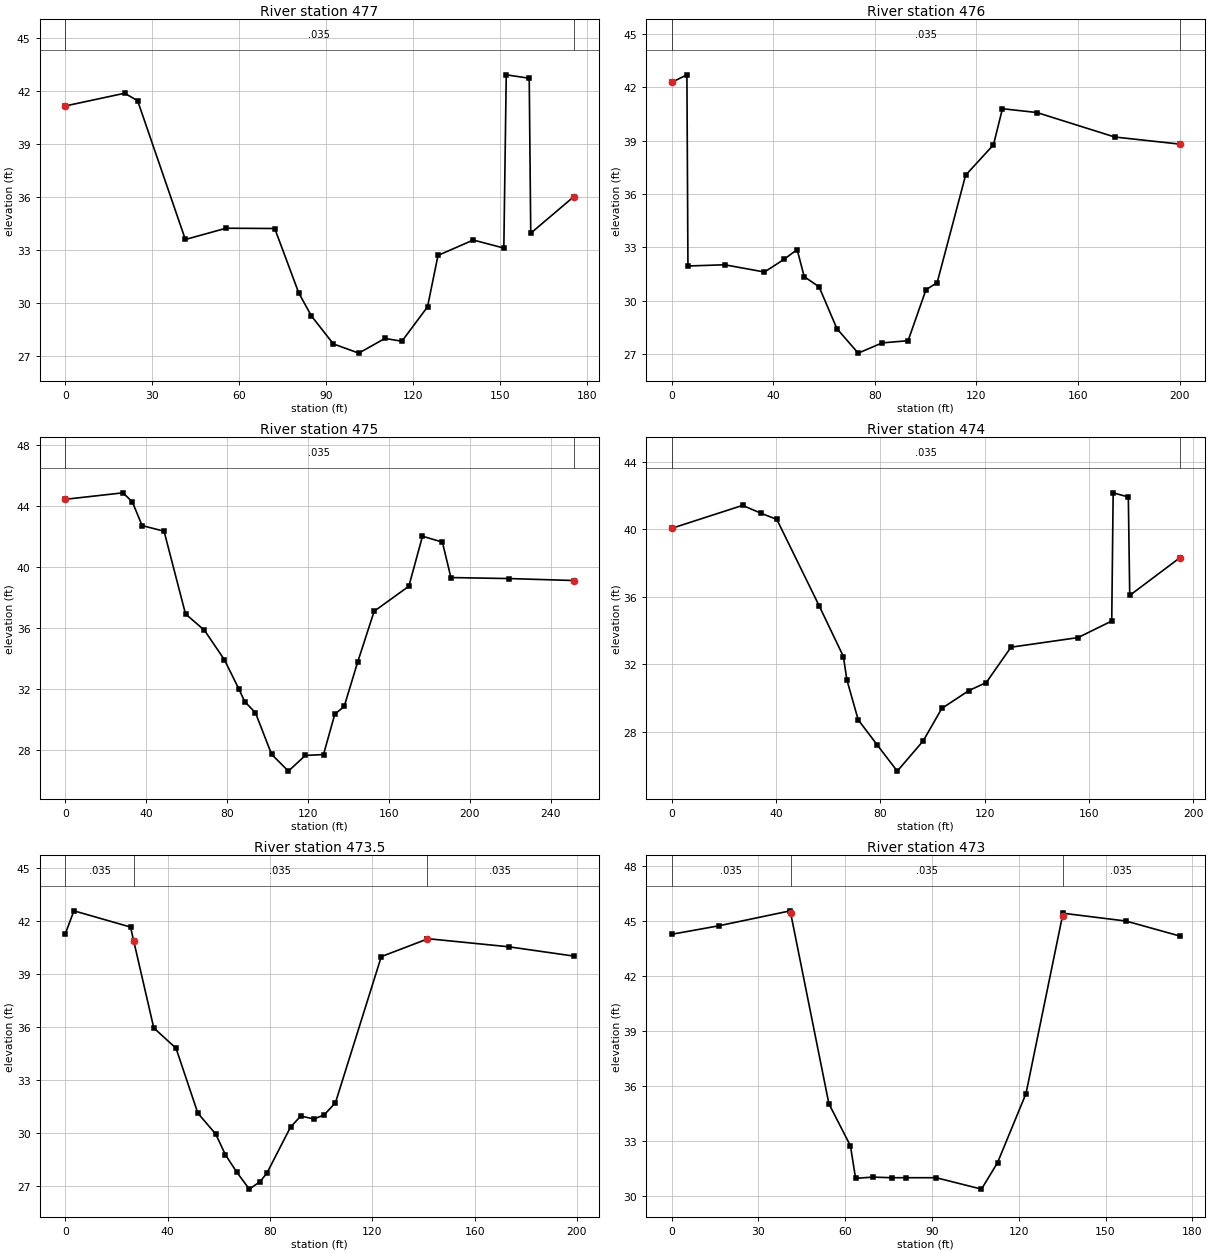
Type RM Length L Ch R = 1 ,477     ,89.108,89.108,89.108
XS GIS Cut Line= 3
      5306343.96     15926322.44      5306294.82     15926490.35
      5306294.82     15926490.35
#Sta/Elev= 20
       0  41.161  20.489  41.883   24.97  41.463  41.444  33.593  55.482  34.232
  72.277  34.216  80.554  30.564  84.905  29.265  92.484  27.674  101.27  27.152
 110.285  27.986 116.132  27.825 124.974  29.774 128.589   32.69 140.751  33.563
 151.299  33.107 152.133  42.927 160.056  42.733 160.584   33.95 175.341  36.007
#Mann= 3 , 0 , 0
       0    .035       0       0    .035       0 175.341    .035       0
Bank Sta=0,175.341
XS Rating Curve= 0
Exp/Cntr=.3,.1

Type RM Length L Ch R = 1 ,476     ,165.19,165.19,165.19
XS GIS Cut Line= 3
      5306253.58      15926314.6      5306195.37     15926504.99
      5306195.37     15926504.99
#Sta/Elev= 21
       0  42.267   5.997  42.687   6.404  31.955  20.853  32.024  36.522  31.617
   44.36  32.339  49.393  32.881  52.188  31.355  58.045  30.784  65.059  28.438
  73.435  27.064  82.897  27.638  93.091  27.762 100.121  30.623 104.524   31.02
 115.725  37.051 126.696  38.757  130.23  40.784 143.786  40.571 174.452  39.196
 200.138  38.796
#Mann= 3 , 0 , 0
       0    .035       0       0    .035       0 200.138    .035       0
Bank Sta=0,200.138
XS Rating Curve= 0
Exp/Cntr=.3,.1

Type RM Length L Ch R = 1 ,475     ,218.766,218.766,218.766
XS GIS Cut Line= 3
      5306111.55     15926225.95      5306032.02     15926463.91
      5306032.02     15926463.91
#Sta/Elev= 25
       0  44.446  28.556  44.872  33.169  44.278  38.025   42.72  48.871  42.352
  59.469  36.919  68.809   35.85  78.658  33.921  85.942  31.969  88.727  31.165
  94.055   30.43 102.024  27.703 110.331  26.598 118.694  27.628 127.697  27.687
 133.271  30.338 137.907  30.843 144.574  33.757 152.733  37.096 169.888   38.74
 176.617  42.021 186.463  41.637 190.669  39.308 219.603  39.242 251.293  39.114
#Mann= 3 , 0 , 0
       0    .035       0       0    .035       0 251.293    .035       0
Bank Sta=0,251.293
XS Rating Curve= 0
Exp/Cntr=.3,.1

Type RM Length L Ch R = 1 ,474     ,169.291,169.291,169.291
XS GIS Cut Line= 2
      5305846.16     15926211.71      5305870.05     15926404.27
#Sta/Elev= 21
       0  40.066  27.178  41.427  34.409  40.951  40.302  40.597  56.631   35.44
  65.814  32.464  67.159  31.079   71.49  28.714  78.816  27.215   86.47  25.669
  96.411  27.464 103.553   29.39 113.963  30.449 120.568  30.919 130.056  33.018
 155.725  33.586 168.671   34.57 169.219  42.172  175.03  41.926 175.568  36.089
 194.836  38.327
#Mann= 3 , 0 , 0
       0    .035       0       0    .035       0 194.836    .035       0
Bank Sta=0,194.836
XS Rating Curve= 0
Exp/Cntr=.3,.1

Type RM Length L Ch R = 1 ,473.5   ,18.176,18.176,18.176
XS GIS Cut Line= 2
      5305669.98     15926267.65      5305729.23     15926456.73
#Sta/Elev= 23
       0  41.273   3.412  42.585  25.525  41.667  26.772  40.879  34.613  35.958
  43.307   34.81  51.837  31.135  58.825  29.954  62.631  28.773  67.093  27.789
  71.949  26.837  76.181  27.264  78.871  27.756  88.058  30.348   92.06  30.971
  97.211  30.807 101.214  31.037  105.61  31.726 123.524  39.993 141.306  40.978
 141.568   41.01 173.294  40.551 198.655  40.026
#Mann= 3 , 0 , 0
       0    .035       0  26.772    .035       0 141.306    .035       0
Bank Sta=26.772,141.306
XS Rating Curve= 0
Exp/Cntr=.3,.1

Type RM Length L Ch R = 1 ,473     ,26.739,26.739,26.739
XS GIS Cut Line= 2
      5305648.79     15926264.44      5305704.63     15926430.28
#Sta/Elev= 18
       0  44.291  16.207  44.751   41.01  45.571  41.109  45.472  54.364  35.039
  61.811  32.743  63.583  30.971  69.554  31.037   76.05  31.004  81.004  31.004
  91.437  31.004 107.119  30.381 112.664  31.824 122.507  35.597 135.138  45.308
 135.269   45.44 157.087  45.013 175.755  44.193
#Mann= 3 , 0 , 0
       0    .035       0  41.109    .035       0 135.138    .035       0
Bank Sta=41.109,135.138
XS Rating Curve= 0
Exp/Cntr=.3,.1

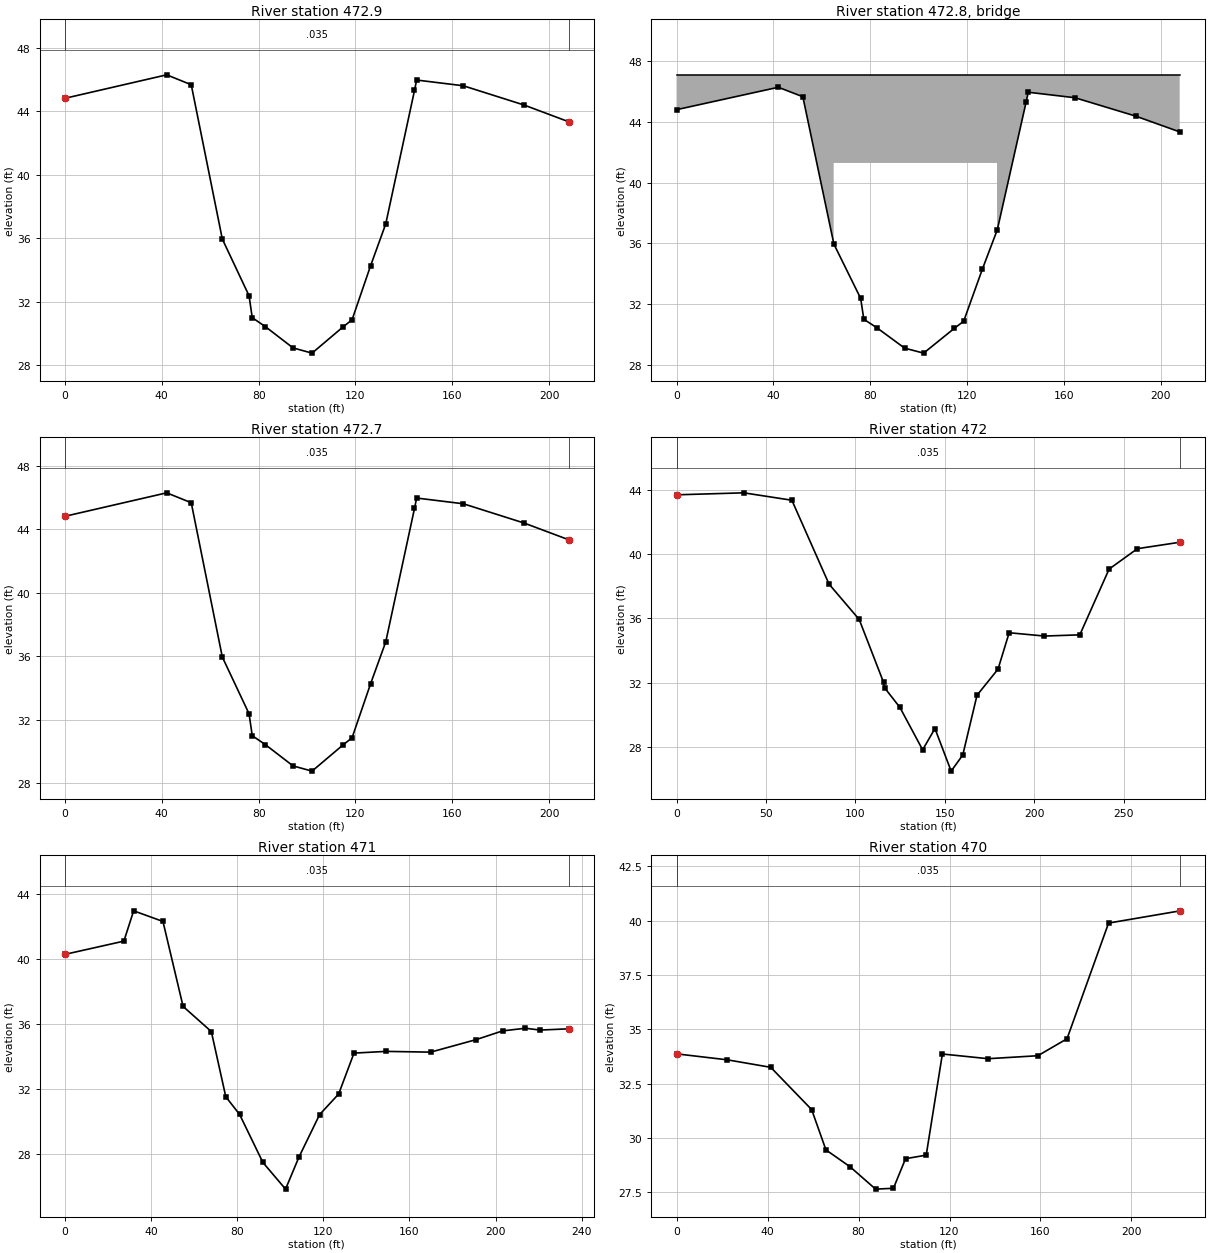
Type RM Length L Ch R = 1 ,472.9   ,32.808,32.808,32.808
XS GIS Cut Line= 2
      5305615.49      15926227.4       5305706.5     15926481.76
#Sta/Elev= 18
       0  44.816  42.028  46.293  52.165  45.669  64.993  35.958   76.05  32.382
  77.362  31.004  82.743  30.446  94.226  29.101 102.067  28.773 114.797  30.413
 118.602  30.873  126.28  34.285 132.513  36.909  144.39  45.308 145.276  45.965
 164.567  45.604 189.698   44.39 208.071   43.34
#Mann= 3 , 0 , 0
       0    .035       0       0    .035       0 208.071    .035       0
Bank Sta=0,208.071
XS Rating Curve= 0
Exp/Cntr=.3,.1

Type RM Length L Ch R = 3 ,472.8   ,,,
BEGIN DESCRIPTION:
ponte di meati
END DESCRIPTION:
Bridge Culvert--1,0,-1,-1, 0
Deck Dist Width WeirC Skew NumUp NumDn MinLoCord MaxHiCord MaxSubmerge Is_Ogee
1.64,29.528,2.61,0, 11, 11, , , .95, 0, 0,0,,
       0  42.028  52.133  64.895  64.895  82.021 132.382 132.382 164.337 189.501
 207.841
  47.113  47.113  47.113  47.113  47.113  47.113  47.113  47.113  47.113  47.113
  47.113
  41.306  41.306  41.306  35.958  41.306  41.306  41.306  36.909  41.306  41.306
  41.306
       0  42.028  52.133  64.895  64.895  82.021 132.382 132.382 164.337 189.501
 207.841
  47.113  47.113  47.113  47.113  47.113  47.113  47.113  47.113  47.113  47.113
  47.113
  41.306  41.306  41.306  35.958  41.306  41.306  41.306  36.909  41.306  41.306
  41.306
BR Coef=-1 , 0 , 0 ,1.25, 0 ,,,.8,-1,2,0,
WSPro=,,,, 1 ,,,, 0 ,,,, 0 ,,,,-1 ,-1 ,-1 , 0 , 0 , 0 , 0 , 0
BC Design=,, 0 ,, 0 ,,,,,,
BC HTab Sub Flow Pts= 40

Type RM Length L Ch R = 1 ,472.7   ,50.984,50.984,50.984
XS GIS Cut Line= 2
      5305615.49      15926227.4       5305706.5     15926481.76
#Sta/Elev= 18
       0  44.816  42.028  46.293  52.165  45.669  64.993  35.958   76.05  32.382
  77.362  31.004  82.743  30.446  94.226  29.101 102.067  28.773 114.797  30.413
 118.602  30.873  126.28  34.285 132.513  36.909  144.39  45.308 145.276  45.965
 164.567  45.604 189.698   44.39 208.071   43.34
#Mann= 3 , 0 , 0
       0    .035       0       0    .035       0 208.071    .035       0
Bank Sta=0,208.071
XS Rating Curve= 0
Exp/Cntr=.3,.1

Type RM Length L Ch R = 1 ,472     ,172.441,172.441,172.441
XS GIS Cut Line= 2
      5305550.98     15926224.02      5305615.78     15926497.93
#Sta/Elev= 20
       0  43.698  37.595  43.822  64.491   43.36  85.269  38.133 102.149  35.928
 115.738  32.018 116.506  31.647 124.911  30.446 137.621  27.805 144.511  29.131
 153.566  26.476 160.072   27.48 168.038  31.207 179.777  32.831 186.014  35.102
 205.719  34.895 225.525   34.97 241.906  39.068 257.746  40.341 281.693  40.745
#Mann= 3 , 0 , 0
       0    .035       0       0    .035       0 281.693    .035       0
Bank Sta=0,281.693
XS Rating Curve= 0
Exp/Cntr=.3,.1

Type RM Length L Ch R = 1 ,471     ,163.944,163.944,163.944
XS GIS Cut Line= 2
      5305388.19     15926311.09      5305461.15     15926532.61
#Sta/Elev= 21
       0  40.289  27.349  41.102  31.896  42.966  45.505  42.313  54.852  37.087
  67.972  35.541  74.685  31.532  81.112   30.44  91.906  27.493 102.441   25.85
 108.609  27.805 118.268  30.436 127.096  31.699 134.226  34.216  149.15  34.321
 169.829  34.275 190.968  35.046 203.212  35.581 213.773  35.745 220.686  35.633
 233.914  35.709
#Mann= 3 , 0 , 0
       0    .035       0       0    .035       0 233.914    .035       0
Bank Sta=0,233.914
XS Rating Curve= 0
Exp/Cntr=.3,.1

Type RM Length L Ch R = 1 ,470     ,123.458,123.458,123.458
XS GIS Cut Line= 2
      5305239.24      15926364.3      5305290.42     15926579.69
#Sta/Elev= 16
       0  33.875  22.385  33.599  41.411  33.255  59.393  31.309  65.673  29.455
  76.309  28.675  87.503  27.648  95.351  27.687 100.679  29.049 109.761  29.213
 116.867  33.868 136.952  33.652 158.852  33.789 171.673   34.57 189.938  39.895
 221.444  40.459
#Mann= 3 , 0 , 0
       0    .035       0       0    .035       0 221.444    .035       0
Bank Sta=0,221.444
XS Rating Curve= 0
Exp/Cntr=.3,.1

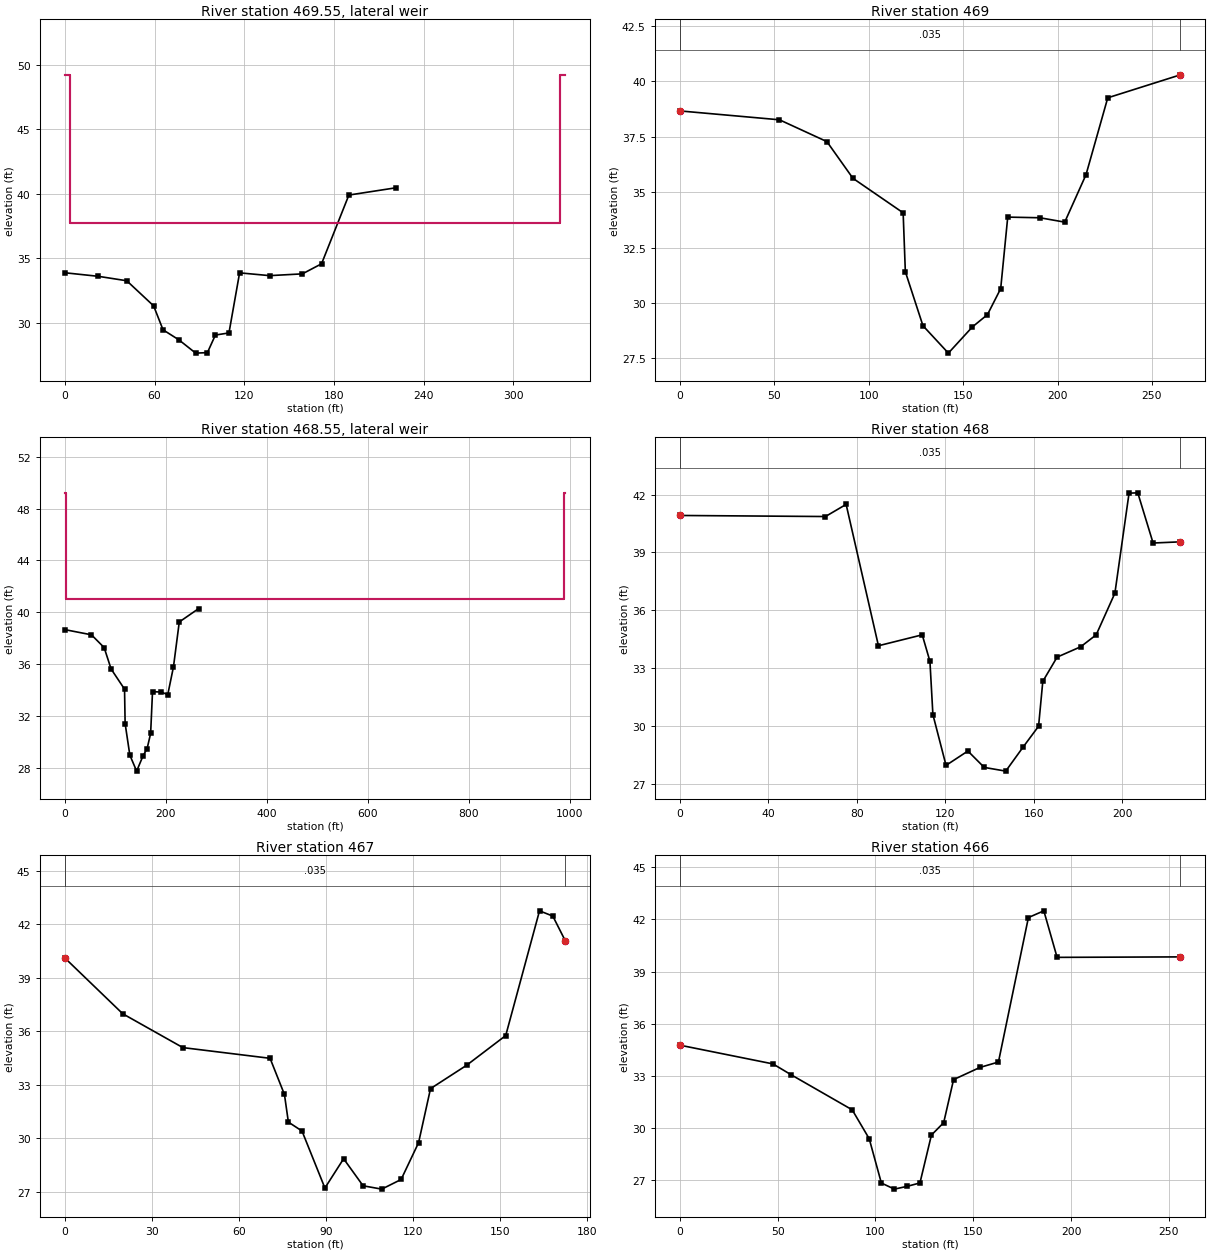
Type RM Length L Ch R = 6 ,469.55  ,,,
Lateral Weir Pos= 3
Lateral Weir End=                ,                ,        ,c01
Lateral Weir Distance=3.281
Lateral Weir WD=9.843
Lateral Weir Coef=3.01
Lateral Weir Is Ogee= 0
Lateral Weir WSCriteria=-1
Lateral Weir SE= 6
       0   49.21    3.28   49.21    3.28   37.73  331.37   37.73  331.37   49.21
  334.65   49.21

Type RM Length L Ch R = 1 ,469     ,225.23,225.23,225.23
XS GIS Cut Line= 2
      5305115.16     15926339.63      5305164.93     15926599.87
#Sta/Elev= 17
       0  38.658   52.73  38.258  77.854  37.274  91.644   35.62 118.235  34.065
 119.396  31.411 128.724  28.976 142.185   27.74 154.905  28.921 162.887  29.475
 169.895  30.646 173.629  33.871 190.679  33.842 203.816  33.645 215.105  35.787
 226.604  39.249 265.079  40.285
#Mann= 3 , 0 , 0
       0    .035       0       0    .035       0 265.079    .035       0
Bank Sta=0,265.079
XS Rating Curve= 0
Exp/Cntr=.3,.1

Type RM Length L Ch R = 6 ,468.55  ,,,
Lateral Weir Pos= 0
Lateral Weir End=                ,                ,        ,c02
Lateral Weir Distance=3.281
Lateral Weir WD=9.843
Lateral Weir Coef=3.01
Lateral Weir Is Ogee= 0
Lateral Weir WSCriteria=-1
Lateral Weir SE= 6
       0  49.213   3.281  49.213   3.281   41.01 987.533   41.01 987.533  49.213
 990.814  49.213

Type RM Length L Ch R = 1 ,468     ,87.828,87.828,87.828
XS GIS Cut Line= 3
      5304888.98     15926404.17      5304945.47      15926622.8
      5304945.47      15926622.8
#Sta/Elev= 22
       0  40.915  65.778   40.86  75.121   41.49  89.718  34.154 109.514  34.721
 112.995  33.346 114.334  30.584 120.272  27.946 130.148  28.691 137.533  27.841
 147.257  27.648 155.052  28.888 162.093  29.977 164.006  32.306 170.466  33.563
 181.132  34.101 188.136  34.721 196.591  36.883 202.986  42.073 206.932   42.09
 213.852  39.485 226.191  39.547
#Mann= 3 , 0 , 0
       0    .035       0       0    .035       0 226.191    .035       0
Bank Sta=0,226.191
XS Rating Curve= 0
Exp/Cntr=.3,.1

Type RM Length L Ch R = 1 ,467     ,83.53,83.53,83.53
XS GIS Cut Line= 3
      5304819.82     15926464.27      5304852.72     15926633.33
      5304852.72     15926633.33
#Sta/Elev= 19
       0  40.121  19.974  36.991  40.696  35.095  70.748  34.495  75.705  32.467
   77.06  30.919  81.755   30.42  89.649  27.224  96.102  28.865 102.812  27.349
 109.252  27.162 115.922  27.703 121.936  29.764 126.053  32.795 138.468  34.101
 151.975  35.771 163.625  42.762 168.209  42.467  172.51  41.083
#Mann= 3 , 0 , 0
       0    .035       0       0    .035       0  172.51    .035       0
Bank Sta=0,172.51
XS Rating Curve= 0
Exp/Cntr=.3,.1

Type RM Length L Ch R = 1 ,466     ,134.875,134.875,134.875
XS GIS Cut Line= 2
      5304737.83     15926472.28      5304795.77     15926720.34
#Sta/Elev= 18
       0   34.77  47.572  33.694   56.86  33.071  88.087  31.056  96.788  29.396
 103.002   26.85 109.665  26.499 116.198   26.66  122.73  26.854 128.599  29.606
 134.865  30.318 139.925  32.792 153.396  33.491 162.871  33.802 178.189  42.103
 186.076   42.49 192.861  39.816 255.902  39.843
#Mann= 3 , 0 , 0
       0    .035       0       0    .035       0 255.902    .035       0
Bank Sta=0,255.902
XS Rating Curve= 0
Exp/Cntr=.3,.1

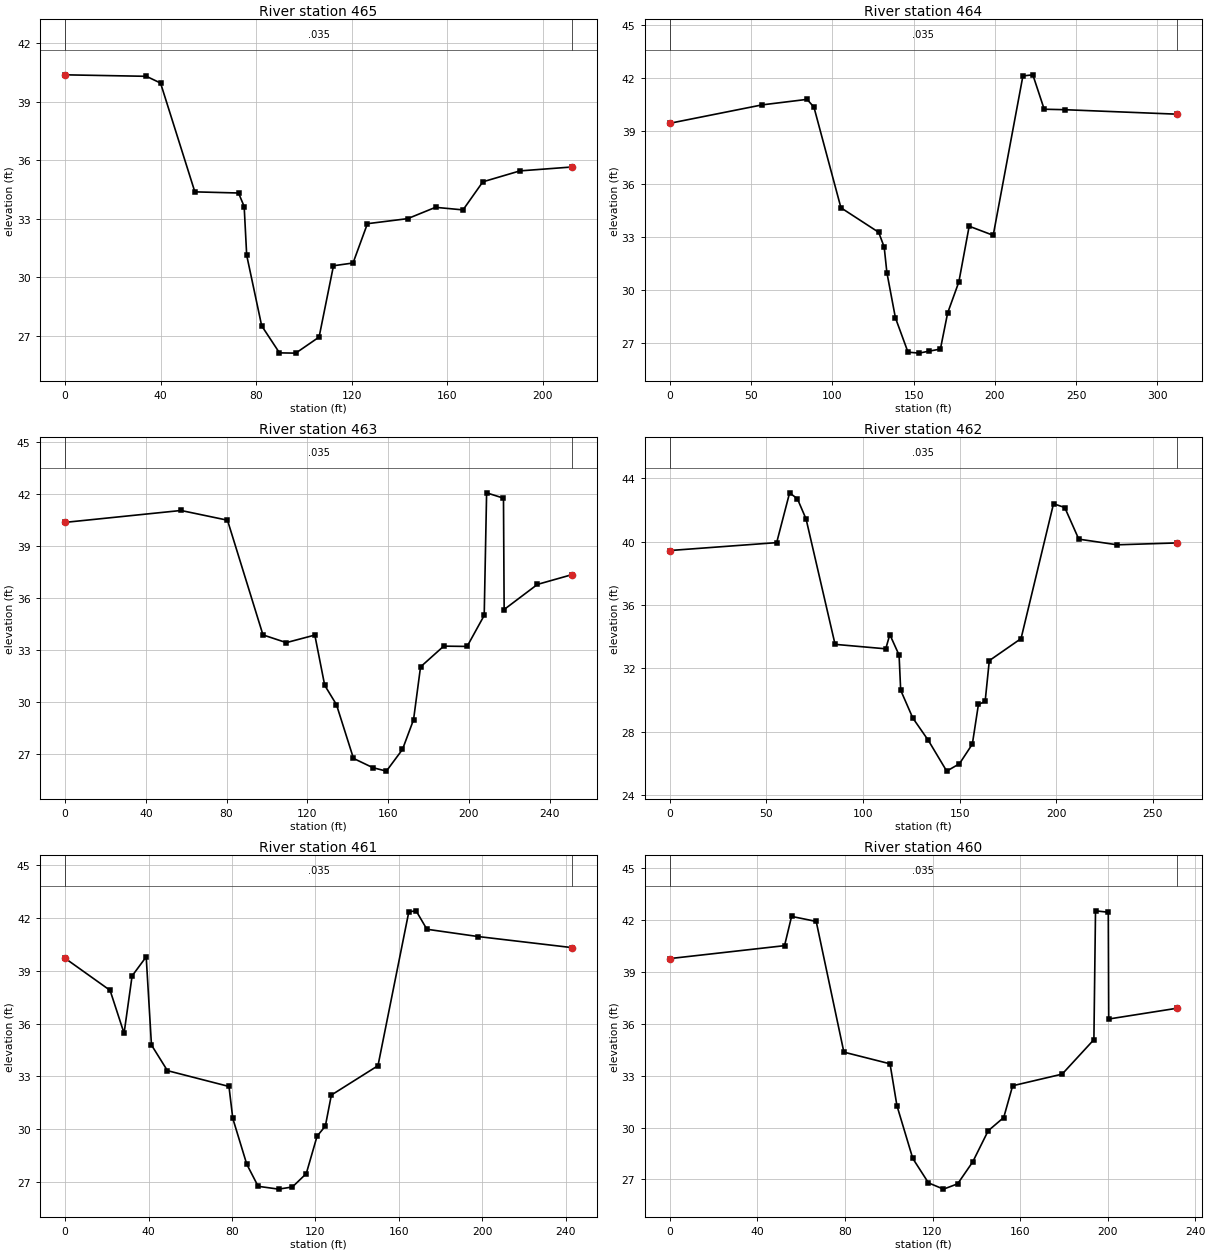
Type RM Length L Ch R = 1 ,465     ,216.831,216.831,216.831
XS GIS Cut Line= 2
      5304594.72      15926531.5      5304671.13     15926729.07
#Sta/Elev= 20
       0  40.384  34.016  40.308  39.948  39.961  54.304  34.377  72.592  34.318
  74.948  33.622  76.007  31.122   82.28    27.5  89.734  26.112  96.542  26.099
 106.312  26.923 112.333  30.584 120.525  30.725 126.545  32.743 143.402  33.002
 155.052  33.583 166.562  33.451 174.865  34.892 190.384  35.453 212.136  35.653
#Mann= 3 , 0 , 0
       0    .035       0       0    .035       0 212.136    .035       0
Bank Sta=0,212.136
XS Rating Curve= 0
Exp/Cntr=.3,.1

Type RM Length L Ch R = 1 ,464     ,190.978,190.978,190.978
XS GIS Cut Line= 3
      5304372.74     15926566.11      5304488.16     15926855.64
      5304488.16     15926855.64
#Sta/Elev= 22
       0  39.452  56.736  40.492  84.423  40.804  88.648  40.361 105.246  34.672
 128.481  33.284 131.867  32.444 133.517   31.01 138.763  28.448 146.496  26.506
  153.31   26.45 159.688  26.565  166.45   26.68 170.899   28.72 177.792  30.476
 184.147  33.629 198.937  33.114 217.208  42.129  223.32  42.192 230.305  40.246
 242.831   40.22 311.778  39.967
#Mann= 3 , 0 , 0
       0    .035       0       0    .035       0 311.778    .035       0
Bank Sta=0,311.778
XS Rating Curve= 0
Exp/Cntr=.3,.1

Type RM Length L Ch R = 1 ,463     ,186.483,186.483,186.483
XS GIS Cut Line= 3
      5304196.23     15926644.78      5304288.35     15926877.82
      5304288.35     15926877.82
#Sta/Elev= 22
       0  40.367  57.428  41.053  80.443  40.492  98.028  33.868 109.587  33.422
 123.717  33.858 128.612  30.958 134.432  29.843 142.874  26.736 152.477  26.201
 159.176  26.001 167.139  27.251 172.631  28.967 176.102  32.021 187.585  33.219
 199.173  33.202 207.644  34.993 208.835  42.073 217.198  41.765 217.526  35.335
 234.032  36.785 251.089  37.346
#Mann= 3 , 0 , 0
       0    .035       0       0    .035       0 251.089    .035       0
Bank Sta=0,251.089
XS Rating Curve= 0
Exp/Cntr=.3,.1

Type RM Length L Ch R = 1 ,462     ,164.206,164.206,164.206
XS GIS Cut Line= 2
        5304025.     15926723.88      5304128.44     15926964.63
#Sta/Elev= 24
       0  39.442  55.266  39.941  61.965  43.087  66.001   42.71  70.482  41.434
  85.489  33.514 111.716  33.232 113.825  34.134 118.612  32.835 119.439  30.617
 125.699  28.865 133.783  27.441 143.261  25.505 149.846  25.971 156.526  27.211
 159.669  29.715  163.15  29.911 165.305  32.487 181.729  33.878  198.53  42.398
  204.35  42.159 211.604  40.161 231.509  39.803 262.238  39.921
#Mann= 3 , 0 , 0
       0    .035       0       0    .035       0 262.238    .035       0
Bank Sta=0,262.238
XS Rating Curve= 0
Exp/Cntr=.3,.1

Type RM Length L Ch R = 1 ,461     ,106.759,106.759,106.759
XS GIS Cut Line= 2
      5303893.57     15926821.19      5303982.84     15927045.87
#Sta/Elev= 23
       0  39.705  21.558  37.884  28.264  35.443  32.113  38.704  38.871   39.79
  41.401  34.777  49.055   33.32  78.563  32.421  80.394  30.607  87.093  28.002
  92.559  26.745 102.343  26.585 108.957  26.706 115.623  27.464  120.81  29.593
 124.787  30.171 127.657  31.932 150.023  33.602  164.81  42.349 168.307  42.405
 173.465  41.358 197.894  40.945 243.002  40.315
#Mann= 3 , 0 , 0
       0    .035       0       0    .035       0 243.002    .035       0
Bank Sta=0,243.002
XS Rating Curve= 0
Exp/Cntr=.3,.1

Type RM Length L Ch R = 1 ,460     ,215.814,215.814,215.814
XS GIS Cut Line= 3
      5303770.34     15926850.69       5303876.8     15927054.92
       5303876.8     15927054.92
#Sta/Elev= 21
       0   39.78  52.392  40.528  55.614  42.221   66.86  41.929  79.505  34.367
 100.591  33.691 103.743   31.27 110.984  28.215 118.156  26.801 125.016   26.44
 131.473  26.745 138.369  28.015 145.433  29.816 152.536  30.584 156.614  32.421
 179.229  33.094 193.734  35.089 194.475  42.543 200.312  42.461 200.502  36.283
 231.532  36.903
#Mann= 3 , 0 , 0
       0    .035       0       0    .035       0 231.532    .035       0
Bank Sta=0,231.532
XS Rating Curve= 0
Exp/Cntr=.3,.1

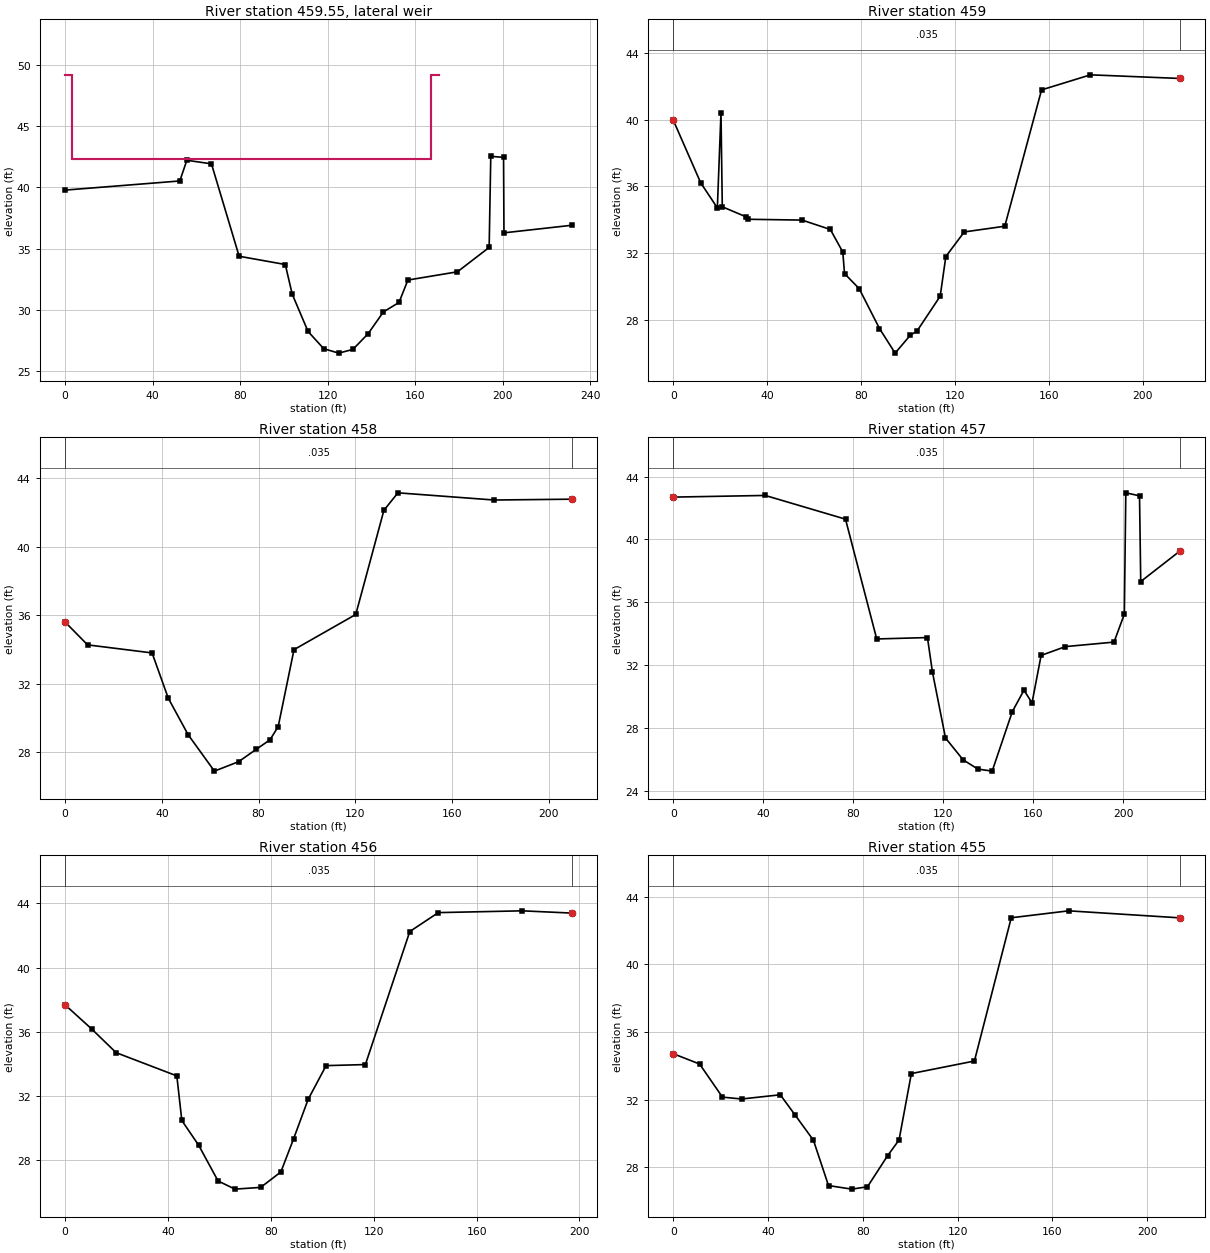
Type RM Length L Ch R = 6 ,459.55  ,,,
Lateral Weir Pos= 0
Lateral Weir End=                ,                ,        ,c02
Lateral Weir Distance=3.281
Lateral Weir WD=9.843
Lateral Weir Coef=3.01
Lateral Weir Is Ogee= 0
Lateral Weir WSCriteria=-1
Lateral Weir SE= 6
       0  49.213   3.281  49.213   3.281  42.323 167.323  42.323 167.323  49.213
 170.604  49.213

Type RM Length L Ch R = 1 ,459     ,132.874,132.874,132.874
XS GIS Cut Line= 2
      5303607.55     15926978.05      5303688.68     15927175.56
#Sta/Elev= 23
       0  39.974  11.667   36.22  18.763  34.715  20.308   40.43  20.866  34.783
  30.912  34.183   31.86  34.032  54.875  33.983  66.909  33.419  72.215  32.067
  72.953  30.771  79.196  29.869  87.851  27.474  94.505  25.997 100.978   27.07
 103.842  27.323 113.714  29.413 116.119  31.795 123.953  33.271 141.234  33.615
 156.909  41.798 177.753  42.703 215.935  42.484
#Mann= 3 , 0 , 0
       0    .035       0       0    .035       0 215.935    .035       0
Bank Sta=0,215.935
XS Rating Curve= 0
Exp/Cntr=.3,.1

Type RM Length L Ch R = 1 ,458     ,150.066,150.066,150.066
XS GIS Cut Line= 2
      5303493.31     15927073.49      5303597.18     15927255.18
#Sta/Elev= 16
       0  35.604   9.295  34.272  35.971  33.802  42.671  31.158  50.863  29.032
  61.755    26.9  71.808  27.454  79.108  28.179  84.741  28.727  88.133  29.498
  94.678  33.993 120.236  36.047 131.867  42.129 137.664   43.15 177.451   42.73
 209.633  42.779
#Mann= 3 , 0 , 0
       0    .035       0       0    .035       0 209.633    .035       0
Bank Sta=0,209.633
XS Rating Curve= 0
Exp/Cntr=.3,.1

Type RM Length L Ch R = 1 ,457     ,108.924,108.924,108.924
XS GIS Cut Line= 2
      5303325.66      15927097.9       5303451.8     15927284.28
#Sta/Elev= 21
       0  42.697  40.843  42.802  76.535  41.293  90.407  33.668 112.963  33.757
  115.18  31.562 120.981  27.365 128.816  25.974 135.381  25.387 141.729  25.256
 150.686  29.045 155.863  30.407 159.442    29.6 163.484  32.621 174.304  33.182
 195.886  33.468 200.479  35.246 201.132  42.969 207.228  42.779 207.766  37.323
 225.256  39.272
#Mann= 3 , 0 , 0
       0    .035       0       0    .035       0 225.256    .035       0
Bank Sta=0,225.256
XS Rating Curve= 0
Exp/Cntr=.3,.1

Type RM Length L Ch R = 1 ,456     ,137.73,137.73,137.73
XS GIS Cut Line= 3
      5303269.65     15927219.06        5303375.     15927382.81
        5303375.     15927382.81
#Sta/Elev= 18
       0  37.677  10.351  36.171  19.833  34.701  43.432  33.255  45.374  30.479
  51.923  28.937  59.462  26.713   66.03  26.204  76.033  26.312  83.891  27.274
  88.862   29.35  94.478  31.788 101.476  33.894 116.752   33.96 134.012  42.244
 145.108  43.422 177.717  43.533 197.047  43.392
#Mann= 3 , 0 , 0
       0    .035       0       0    .035       0 197.047    .035       0
Bank Sta=0,197.047
XS Rating Curve= 0
Exp/Cntr=.3,.1

Type RM Length L Ch R = 1 ,455     ,262.336,262.336,262.336
XS GIS Cut Line= 3
      5303150.98     15927298.62       5303289.8     15927460.37
       5303289.8     15927460.37
#Sta/Elev= 17
       0  34.715  11.083  34.108  20.741  32.152  28.822  32.041  45.154   32.29
  51.332  31.109   59.14  29.606  65.512  26.926  75.322  26.716  81.949  26.854
  90.456  28.691  95.282  29.619 100.479  33.543 127.103  34.285 142.651  42.749
 166.893  43.159 213.917  42.743
#Mann= 3 , 0 , 0
       0    .035       0       0    .035       0 213.917    .035       0
Bank Sta=0,213.917
XS Rating Curve= 0
Exp/Cntr=.3,.1

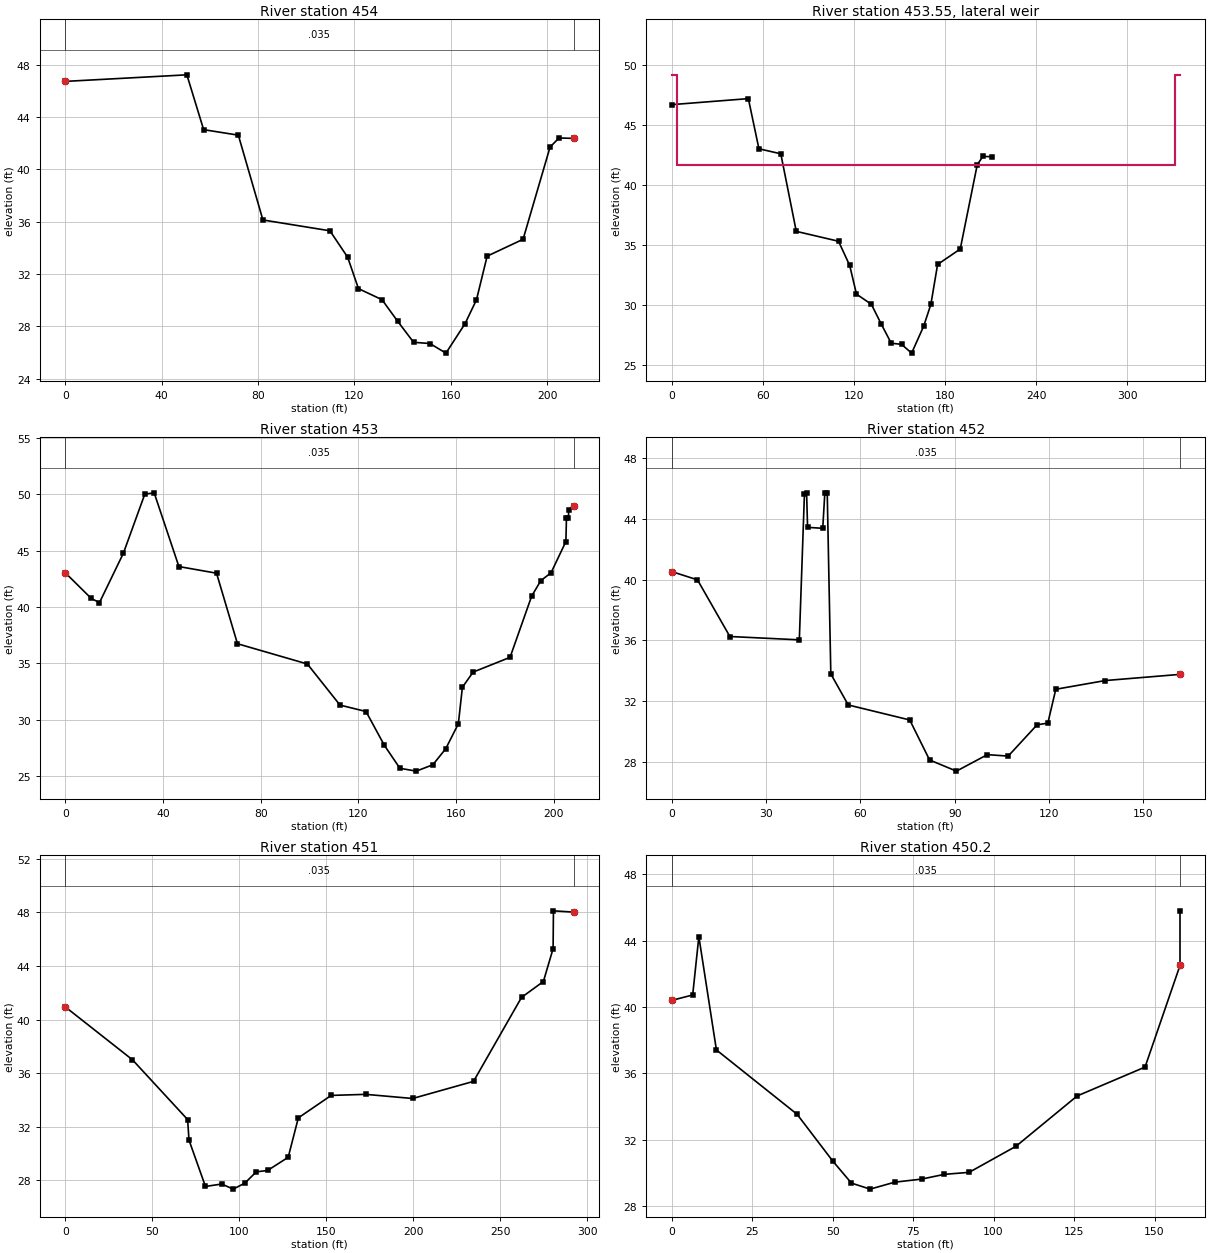
Type RM Length L Ch R = 1 ,454     ,198.72,198.72,198.72
XS GIS Cut Line= 2
      5302932.25     15927384.42      5303022.41     15927574.74
#Sta/Elev= 20
       0  46.722  50.482  47.224  57.434  43.035  71.837  42.615  82.028  36.135
 109.836  35.308 117.195  33.287 121.673  30.889 131.447  30.043 137.927  28.399
 144.551  26.788 151.325  26.696 157.966  25.961 165.879  28.205 170.643  30.036
 175.062  33.369 189.977  34.659 201.178  41.709 204.902  42.398 210.912  42.369
#Mann= 3 , 0 , 0
       0    .035       0       0    .035       0 210.912    .035       0
Bank Sta=0,210.912
XS Rating Curve= 0
Exp/Cntr=.3,.1

Type RM Length L Ch R = 6 ,453.55  ,,,
Lateral Weir Pos= 3
Lateral Weir End=                ,                ,        ,c01
Lateral Weir Distance=3.281
Lateral Weir WD=9.843
Lateral Weir Coef=3.01
Lateral Weir Is Ogee= 0
Lateral Weir WSCriteria=-1
Lateral Weir SE= 6
       0  49.213   3.281  49.213   3.281  41.667 331.365  41.667 331.365  49.213
 334.646  49.213

Type RM Length L Ch R = 1 ,453     ,159.908,159.908,159.908
XS GIS Cut Line= 2
      5302774.28     15927435.63      5302813.58     15927638.16
#Sta/Elev= 29
       0  43.041  10.666  40.758  14.022  40.387  23.832  44.774  32.579      50
  36.411  50.115  46.532  43.583  61.939  42.995  70.505  36.745  99.108  34.951
  112.48  31.309 123.117  30.741  130.64   27.74 136.995  25.709 143.707  25.459
 150.479  26.024 155.732  27.438 160.909  29.649 162.569   32.89 166.952  34.232
 182.077  35.541 190.919  40.965 194.685  42.339 198.842  43.028 204.928  45.797
 205.167  47.927 205.971   47.92 206.099  48.625 208.058  48.976
#Mann= 3 , 0 , 0
       0    .035       0       0    .035       0 208.058    .035       0
Bank Sta=0,208.058
XS Rating Curve= 0
Exp/Cntr=.3,.1

Type RM Length L Ch R = 1 ,452     ,7.251,7.251,7.251
XS GIS Cut Line= 2
      5302612.43     15927499.18      5302673.56       15927644.
#Sta/Elev= 22
       0  40.545   8.209  39.997  18.504  36.263  40.591  36.043  42.218  45.676
  42.904  45.699  43.219  43.458  48.038  43.396  48.694  45.709  49.465  45.735
  50.607  33.793  56.155  31.749  75.705  30.761  82.011  28.123  90.554  27.388
 100.374  28.474 107.014  28.379 116.188   30.44  119.61  30.554 122.146  32.785
 137.894   33.36  161.64  33.766
#Mann= 3 , 0 , 0
       0    .035       0       0    .035       0  161.64    .035       0
Bank Sta=0,161.64
XS Rating Curve= 0
Exp/Cntr=.3,.1

Type RM Length L Ch R = 1 ,451     ,15.748,15.748,15.748
XS GIS Cut Line= 2
      5302541.73     15927563.94      5302823.95     15927638.39
#Sta/Elev= 21
       0  40.955  38.632  37.008  70.361  32.546  71.158  31.014  80.617  27.556
  89.957  27.736  96.581  27.356 103.228  27.802 109.829  28.645 116.329  28.747
 128.176  29.731 133.999  32.671 152.884  34.347 172.743  34.426 199.701  34.117
 234.705  35.394 262.306   41.66 274.869  42.844 280.446  45.302 280.643  48.117
 292.192  48.022
#Mann= 3 , 0 , 0
       0    .035       0       0    .035       0 292.192    .035       0
Bank Sta=0,292.192
XS Rating Curve= 0
Exp/Cntr=.3,.1

Type RM Length L Ch R = 1 ,450.2   ,65.617,65.617,65.617
XS GIS Cut Line= 3
      5302523.23      15927637.5      5302675.43     15927679.04
      5302675.43     15927679.04
#Sta/Elev= 17
       0    40.4   6.528  40.728   8.443  44.249  13.896  37.415   38.95  33.537
  50.016  30.721   55.84  29.386  61.654  29.022  69.314  29.442  77.615  29.626
  84.738  29.914  92.402  30.033 106.978  31.607 125.965  34.639  147.06  36.381
  157.92  42.507  157.92  45.801
#Mann= 3 , 0 , 0
       0    .035       0       0    .035       0  157.92    .035       0
Bank Sta=0,157.92
XS Rating Curve= 0
Exp/Cntr=.3,.1

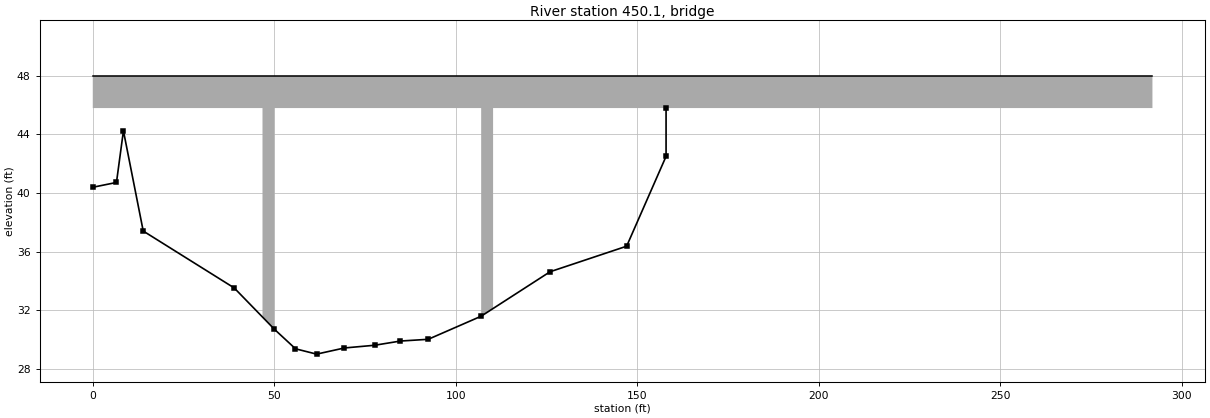
Type RM Length L Ch R = 3 ,450.1   ,,,
BEGIN DESCRIPTION:
A11
END DESCRIPTION:
Bridge Culvert--1,0,-1,-1, 0
Deck Dist Width WeirC Skew NumUp NumDn MinLoCord MaxHiCord MaxSubmerge Is_Ogee
1.64,62.336,2.61,0, 27, 27, , , .95, 0, 0,0,,
       0  38.615  46.752  46.752  50.033  50.033  70.341   71.03  80.446  89.764
  96.391 106.988 106.988 110.269 110.269 116.109 127.953  133.76 152.657 172.507
 199.475 234.449 262.041 274.573 280.151 280.315 291.896
  47.999  47.999  47.999  47.999  47.999  47.999  47.999  47.999  47.999  47.999
  47.999  47.999  47.999  47.999  47.999  47.999  47.999  47.999  47.999  47.999
  47.999  47.999  47.999  47.999  47.999  47.999  47.999
  45.801  45.801  45.801   30.84  30.709  45.801  45.801  45.801  45.801  45.801
  45.801  45.801  31.594  31.824  45.801  45.801  45.801  45.801  45.801  45.801
  45.801  45.801  45.801  45.801  45.801  45.801  45.801
       0  38.615  46.752  46.752  50.033  50.033  70.341   71.03  80.446  89.764
  96.391 106.988 106.988 110.269 110.269 116.109 127.953  133.76 152.657 172.507
 199.475 234.449 262.041 274.573 280.151 280.315 291.896
  47.999  47.999  47.999  47.999  47.999  47.999  47.999  47.999  47.999  47.999
  47.999  47.999  47.999  47.999  47.999  47.999  47.999  47.999  47.999  47.999
  47.999  47.999  47.999  47.999  47.999  47.999  47.999
  45.801  45.801  45.801   30.84  30.709  45.801  45.801  45.801  45.801  45.801
  45.801  45.801  31.594  31.824  45.801  45.801  45.801  45.801  45.801  45.801
  45.801  45.801  45.801  45.801  45.801  45.801  45.801
BR Coef=-1 , 0 , 0 ,1.25, 0 ,,,.8,-1,2,0,
WSPro=,,,, 1 ,,,, 0 ,,,, 0 ,,,,-1 ,-1 ,-1 , 0 , 0 , 0 , 0 , 0
BC Design=,, 0 ,, 0 ,,,,,,
BC HTab Sub Flow Pts= 40