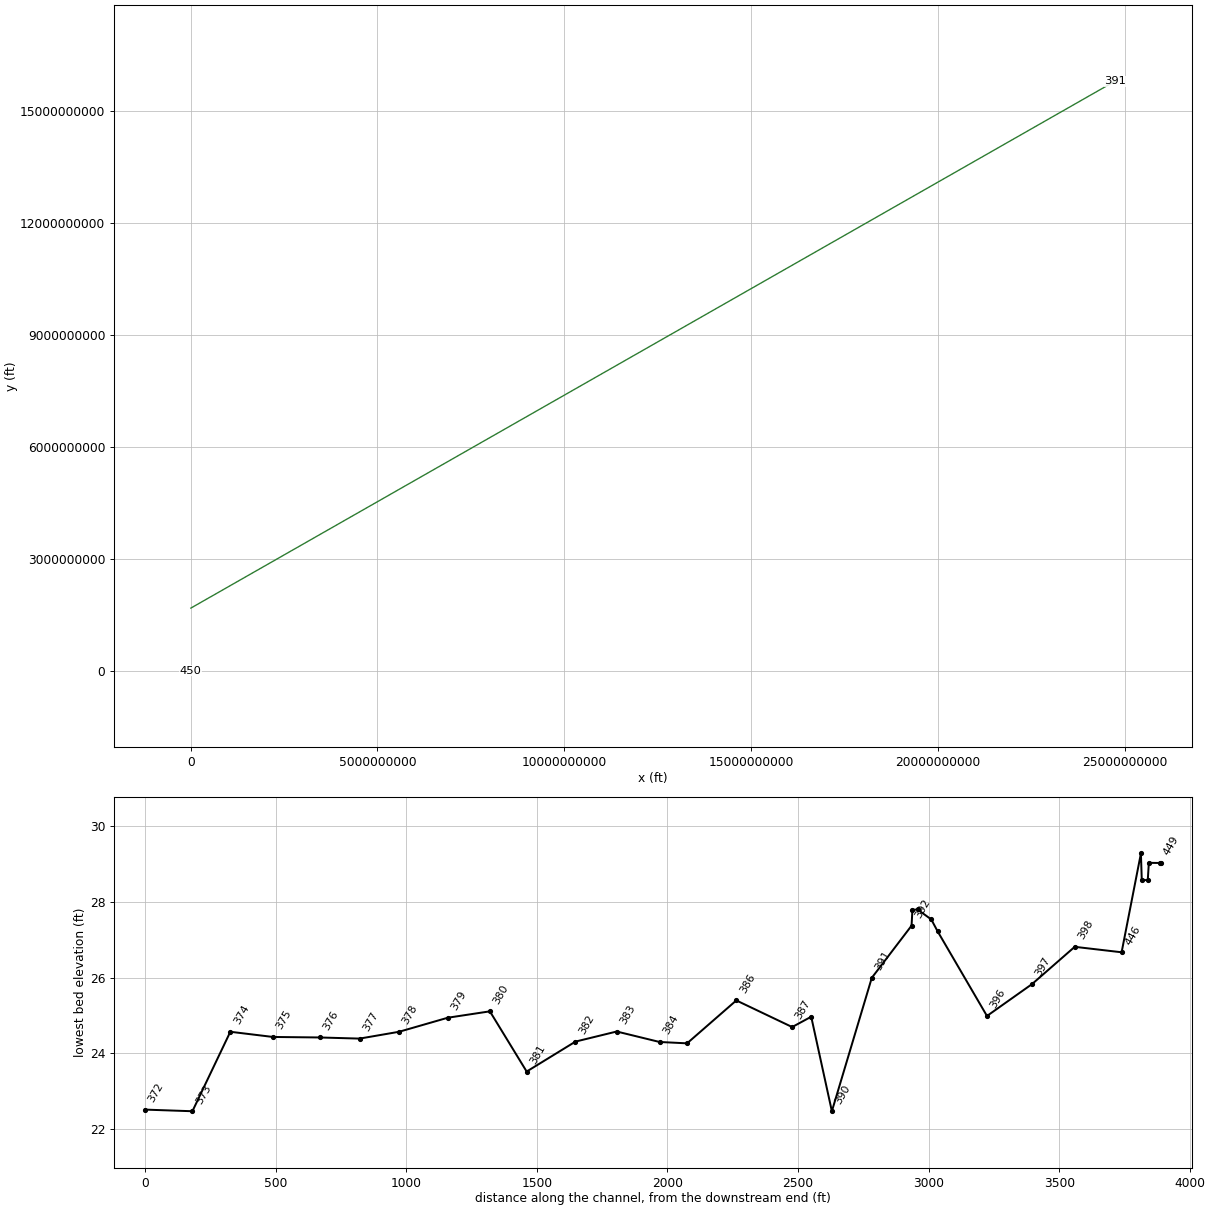
HEC-RAS study ozz_def.prj: ozzeri

--- ozz_def.g04 (geometry) --- (continued)

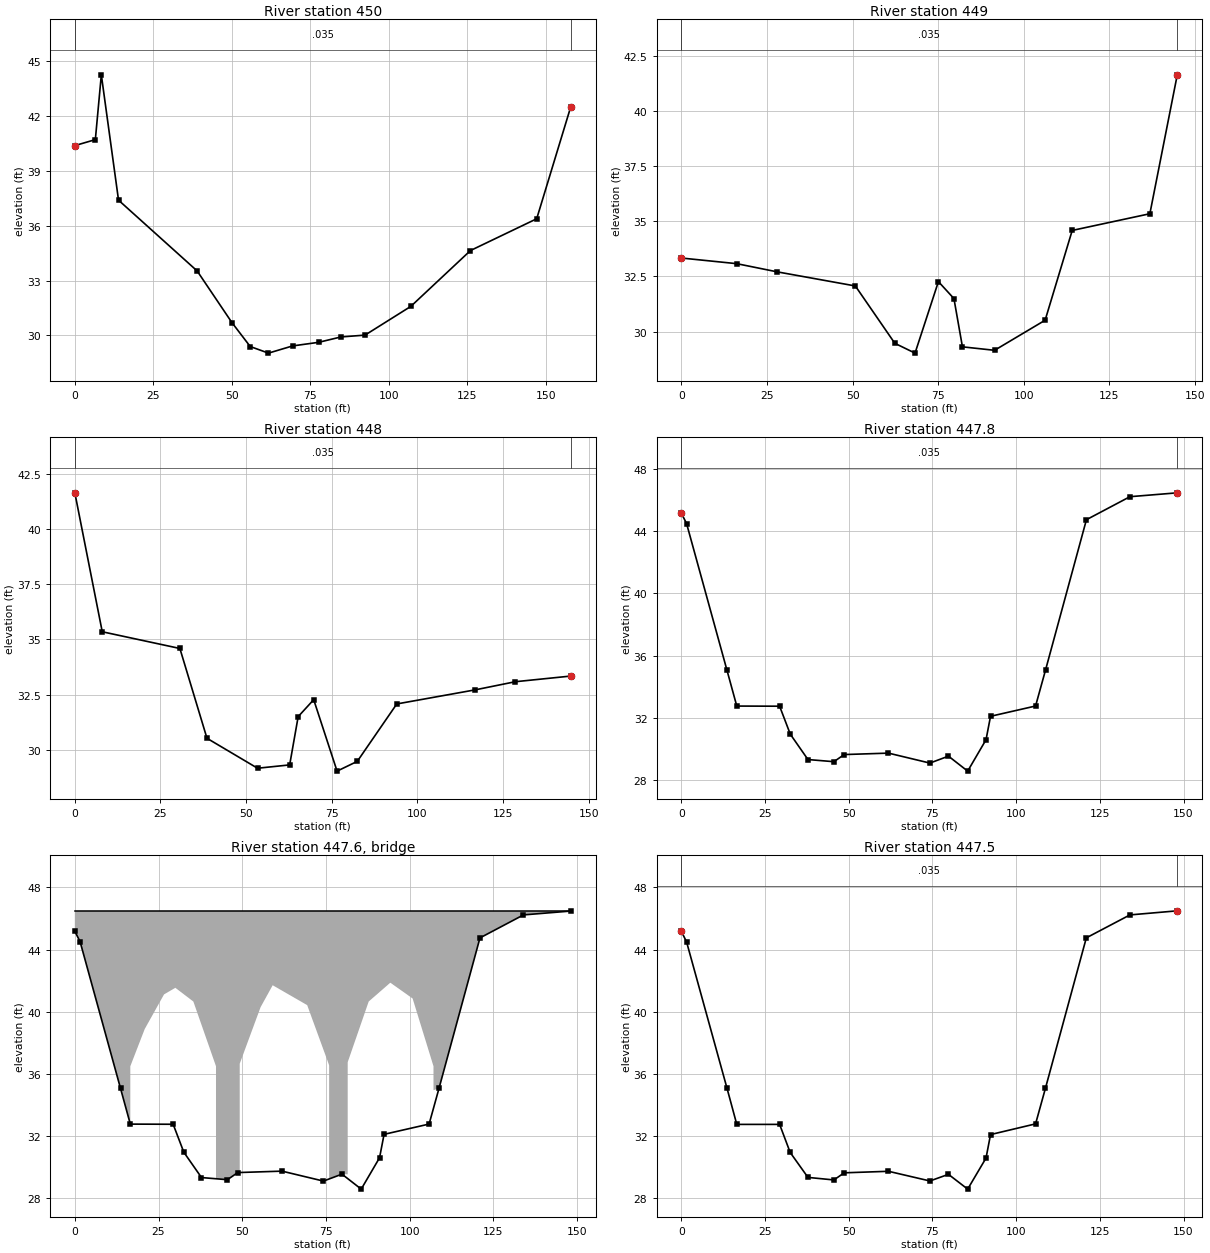
Type RM Length L Ch R = 1 ,450     ,5.249,5.249,5.249
XS GIS Cut Line= 2
      5302523.23      15927637.5      5302675.43     15927679.04
#Sta/Elev= 16
       0  40.387   6.529  40.715   8.432  44.259  13.911  37.402  38.944   33.53
      50  30.709   55.84  29.396  61.647  29.035  69.324  29.429  77.625  29.626
  84.744  29.921  92.388   30.02 106.988  31.594 125.951  34.646 147.047  36.385
 157.907   42.52
#Mann= 3 , 0 , 0
       0    .035       0       0    .035       0 157.907    .035       0
Bank Sta=0,157.907
XS Rating Curve= 0
Exp/Cntr=.3,.1

Type RM Length L Ch R = 1 ,449     ,41.503,41.503,41.503
XS GIS Cut Line= 2
      5302664.07      15927695.7       5302529.3     15927647.05
#Sta/Elev= 14
       0  33.337  16.171  33.081  27.982   32.71   50.81   32.07  62.333  29.472
  68.238  29.026  75.062  32.267  79.596  31.499  82.077  29.311  91.457  29.154
  106.22  30.518 114.127  34.587 136.798  35.344   144.8   41.64
#Mann= 3 , 0 , 0
       0    .035       0       0    .035       0   144.8    .035       0
Bank Sta=0,144.8
XS Rating Curve= 0
Exp/Cntr=.3,.1

Type RM Length L Ch R = 1 ,448     ,4.134,4.134,4.134
XS GIS Cut Line= 2
      5302518.18     15927681.82      5302454.53      15927660.3
#Sta/Elev= 14
       0   41.64   8.002  35.344  30.669  34.587  38.576  30.518  53.343   29.16
   62.72  29.311  65.203  31.499  69.738  32.267  76.558  29.029  82.464  29.472
   93.99  32.073 116.818   32.71 128.629  33.081   144.8  33.337
#Mann= 3 , 0 , 0
       0    .035       0       0    .035       0   144.8    .035       0
Bank Sta=0,144.8
XS Rating Curve= 0
Exp/Cntr=.3,.1

Type RM Length L Ch R = 1 ,447.8   ,22.966,22.966,22.966
#Sta/Elev= 20
       0  45.171   1.575  44.498  13.648  35.056  16.568  32.759  29.364  32.749
  32.546  30.951  37.828  29.318  45.571   29.18  48.655  29.639  61.877  29.731
  74.245  29.091   79.79  29.537  85.531  28.573   91.01  30.594  92.356    32.1
 105.807  32.762 108.793  35.085 120.997  44.747  133.99  46.227  148.13  46.476
#Mann= 3 , 0 , 0
       0    .035       0       0    .035       0  148.13    .035       0
Bank Sta=0,148.13
XS Rating Curve= 0
Exp/Cntr=.3,.1

Type RM Length L Ch R = 3 ,447.6   ,,,
BEGIN DESCRIPTION:
Ponte FFSS
END DESCRIPTION:
Bridge Culvert--1,0,-1,-1, 0
Deck Dist Width WeirC Skew NumUp NumDn MinLoCord MaxHiCord MaxSubmerge Is_Ogee
1.64,19.685,2.61,0, 30, 30, , , .95, 0, 0,0,,
       0   1.575  13.648  16.568  16.568  20.866   26.64   30.02    35.4  42.159
  42.159  45.571  49.245  49.245  55.479  59.088   69.39  75.951  75.951  81.496
  81.496  87.762  94.226 100.886 107.119 107.119  108.76 120.965  133.99  148.13
   46.49   46.49   46.49   46.49   46.49   46.49   46.49   46.49   46.49   46.49
   46.49   46.49   46.49   46.49   46.49   46.49   46.49   46.49   46.49   46.49
   46.49   46.49   46.49   46.49   46.49   46.49   46.49   46.49   46.49   46.49
  45.177  44.488  35.072  32.743  36.483  38.878  41.109  41.535   40.65  36.483
  29.199  29.167  29.626  36.647  40.289  41.699   40.42  36.549  29.199  29.528
  36.745   40.65  41.864  40.846  36.483  34.941  35.072  44.751  46.227   46.26
       0   1.575  13.648  16.568  16.568  20.866   26.64   30.02    35.4  42.159
  42.159  45.571  49.245  49.245  55.479  59.088   69.39  75.951  75.951  81.496
  81.496  87.762  94.226 100.886 107.119 107.119  108.76 120.965  133.99  148.13
   46.49   46.49   46.49   46.49   46.49   46.49   46.49   46.49   46.49   46.49
   46.49   46.49   46.49   46.49   46.49   46.49   46.49   46.49   46.49   46.49
   46.49   46.49   46.49   46.49   46.49   46.49   46.49   46.49   46.49   46.49
  45.177  44.488  35.072  32.743  36.483  38.878  41.109  41.535   40.65  36.483
  29.199  29.167  29.626  36.647  40.289  41.699   40.42  36.549  29.199  29.528
  36.745   40.65  41.864  40.846  36.483  34.941  35.072  44.751  46.227   46.26
BR Coef=-1 , 0 , 0 ,1.25, 0 ,,,.8,-1,2,0,
WSPro=,,,, 1 ,,,, 0 ,,,, 0 ,,,,-1 ,-1 ,-1 , 0 , 0 , 0 , 0 , 0
BC Design=,, 0 ,, 0 ,,,,,,

Type RM Length L Ch R = 1 ,447.5   ,3.281,3.281,3.281
#Sta/Elev= 20
       0  45.177   1.575  44.488  13.648  35.072  16.568  32.743  29.364  32.743
  32.513  30.938  37.828  29.331  45.571  29.167  48.655  29.626  61.877  29.724
  74.245  29.101   79.79  29.528  85.531  28.576   91.01  30.577  92.356  32.087
 105.807  32.776  108.76  35.072 120.965  44.751  133.99  46.227  148.13   46.49
#Mann= 3 , 0 , 0
       0    .035       0       0    .035       0  148.13    .035       0
Bank Sta=0,148.13
XS Rating Curve= 0
Exp/Cntr=.3,.1

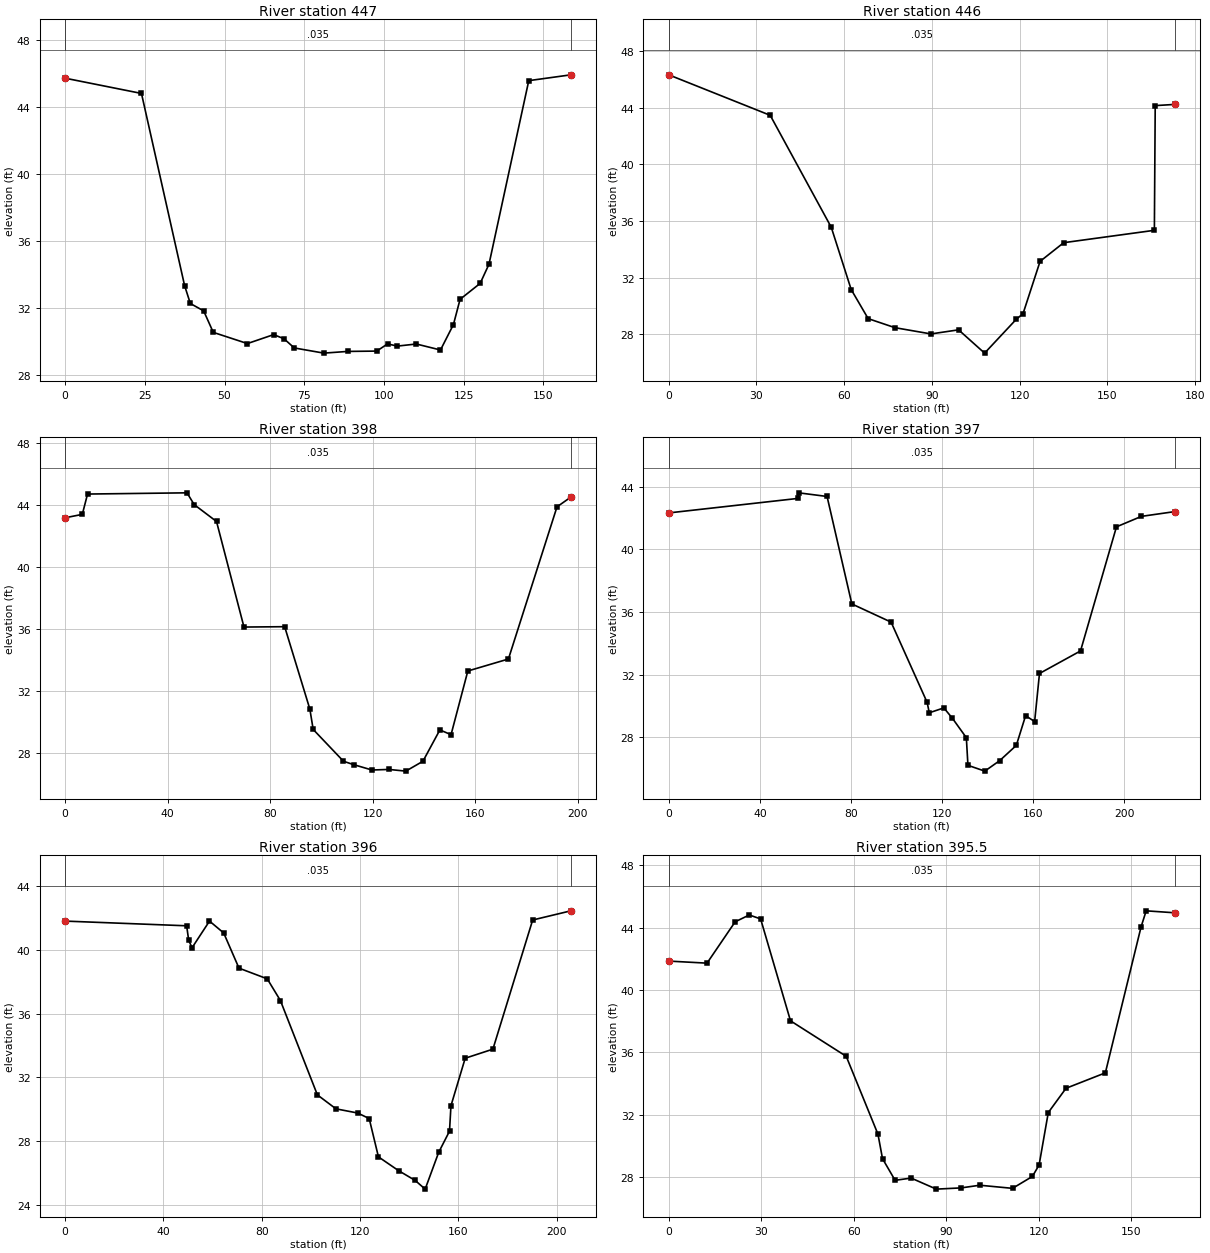
Type RM Length L Ch R = 1 ,447     ,73.885,73.885,73.885
XS GIS Cut Line= 2
      5302486.75     15927707.84      5302635.89     15927750.89
#Sta/Elev= 23
       0  45.702  23.953   44.79   37.48   33.31  39.272  32.244  43.458  31.801
   46.47  30.518  57.175  29.849  65.417  30.384  68.655  30.135  71.883  29.587
  81.155  29.278  88.606   29.38  97.743    29.4 101.119  29.829 104.209  29.698
 110.154  29.823 117.726  29.465 121.791  30.988 123.865  32.493 130.167  33.445
 132.936   34.59 145.407  45.554 158.615  45.902
#Mann= 3 , 0 , 0
       0    .035       0       0    .035       0 158.615    .035       0
Bank Sta=0,158.615
XS Rating Curve= 0
Exp/Cntr=.3,.1

Type RM Length L Ch R = 1 ,446     ,179.495,179.495,179.495
XS GIS Cut Line= 2
      5302450.95     15927764.21      5302613.55     15927822.01
#Sta/Elev= 16
       0  46.312  34.692  43.455  55.574  35.551  62.385  31.158  68.192  29.104
  77.379  28.465  89.665  28.025  99.108  28.314 108.009   26.67 118.825  29.055
 121.155  29.455 126.982  33.146 135.066  34.465 166.073  35.338 166.362   44.14
 172.979  44.222
#Mann= 3 , 0 , 0
       0    .035       0       0    .035       0 172.979    .035       0
Bank Sta=0,172.979
XS Rating Curve= 0
Exp/Cntr=.3,.1

Type RM Length L Ch R = 1 ,398     ,163.517,163.517,163.517
XS GIS Cut Line= 2
      5302355.58     15927892.42      5302520.11     15927993.11
#Sta/Elev= 22
       0  43.169   6.716  43.389    8.76  44.701  47.549   44.78  50.348  44.019
  59.052   42.93   69.76  36.115   85.63  36.138  95.453  30.817  96.752  29.505
 108.566  27.451 112.562  27.231 119.675  26.886 126.266  26.923 132.877  26.814
 139.547  27.451 146.152  29.475 150.509  29.167 157.054  33.278 172.884  34.052
 191.827  43.875 197.241  44.505
#Mann= 3 , 0 , 0
       0    .035       0       0    .035       0 197.241    .035       0
Bank Sta=0,197.241
XS Rating Curve= 0
Exp/Cntr=.3,.1

Type RM Length L Ch R = 1 ,397     ,172.343,172.343,172.343
XS GIS Cut Line= 2
      5302252.26     15927992.29      5302420.28      15928137.3
#Sta/Elev= 22
       0  42.323  56.673  43.248  57.034  43.606  69.501  43.373  80.374  36.509
  97.608  35.348 113.438   30.22  114.38  29.557 120.778  29.869 124.528  29.206
  130.65  27.966 131.352  26.201 138.763   25.83 145.338  26.506 152.592  27.474
  156.67  29.373 160.633  28.996 162.766  32.067 180.781  33.507 196.562  41.434
 207.543  42.103 222.074  42.405
#Mann= 3 , 0 , 0
       0    .035       0       0    .035       0 222.074    .035       0
Bank Sta=0,222.074
XS Rating Curve= 0
Exp/Cntr=.3,.1

Type RM Length L Ch R = 1 ,396     ,189.075,189.075,189.075
XS GIS Cut Line= 2
      5302153.58      15928073.2       5302262.7     15928247.41
#Sta/Elev= 24
       0  41.804  49.469  41.509  50.312  40.594  51.683  40.135   58.77  41.804
  64.547   41.06  70.774  38.852   82.27  38.182  87.625  36.821 102.677  30.902
 110.243  30.026 119.094  29.764 123.763  29.416 127.523  27.014 135.725  26.148
 142.454  25.538 146.539   24.99 152.041  27.297 156.444  28.625 157.037   30.22
 162.831  33.202 174.108   33.77 190.289  41.873  205.84  42.448
#Mann= 3 , 0 , 0
       0    .035       0       0    .035       0  205.84    .035       0
Bank Sta=0,205.84
XS Rating Curve= 0
Exp/Cntr=.3,.1

Type RM Length L Ch R = 1 ,395.5   ,24.081,24.081,24.081
XS GIS Cut Line= 2
      5302018.11     15928169.16      5302073.59     15928323.33
#Sta/Elev= 23
       0  41.854  12.415  41.722  21.535  44.373  26.122  44.813  29.806   44.56
  39.501  38.022  57.585  35.745  67.884  30.748  69.357   29.18  73.442  27.789
  78.648  27.933  86.834  27.224  94.872  27.303 100.925  27.474 111.552  27.274
 117.995  28.038 120.171   28.77 123.153  32.136 128.904  33.694 141.676  34.685
 153.255  44.042 154.918  45.079 164.134  44.954
#Mann= 3 , 0 , 0
       0    .035       0       0    .035       0 164.134    .035       0
Bank Sta=0,164.134
XS Rating Curve= 0
Exp/Cntr=.3,.1

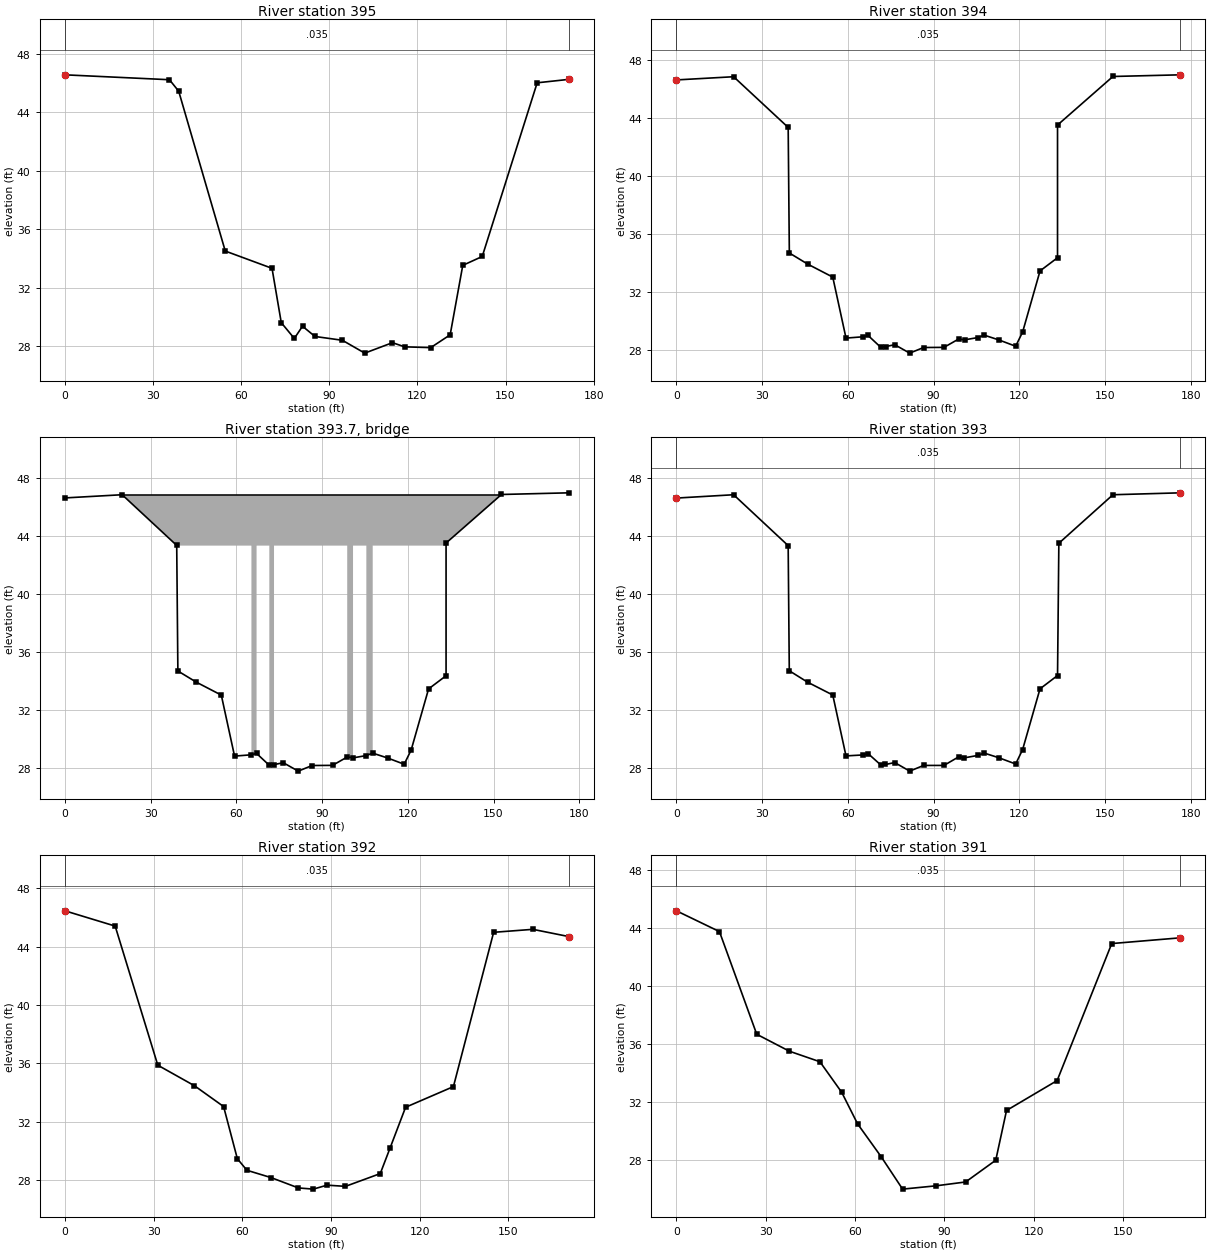
Type RM Length L Ch R = 1 ,395     ,52.526,52.526,52.526
XS GIS Cut Line= 3
      5301993.37     15928171.56      5302053.61     15928331.23
      5302053.61     15928331.23
#Sta/Elev= 19
       0  46.572  35.568  46.237  38.717  45.453  54.573  34.518  70.495  33.337
  73.645  29.619  78.084   28.54  80.879  29.377  85.118  28.675  94.449  28.415
 102.067  27.536 111.509  28.251 115.646  27.966 124.534  27.913 131.152  28.789
  135.44   33.54  142.07  34.147 160.774  46.027 171.532   46.26
#Mann= 3 , 0 , 0
       0    .035       0       0    .035       0 171.532    .035       0
Bank Sta=0,171.532
XS Rating Curve= 0
Exp/Cntr=.3,.1

Type RM Length L Ch R = 1 ,394     ,19.685,19.685,19.685
XS GIS Cut Line= 3
      5301976.61     15928163.94      5302055.51     15928378.51
      5302057.58     15928384.09
#Sta/Elev= 27
       0  46.627  20.016  46.847  39.108  43.353  39.514  34.701  45.909  33.937
  54.715  33.038   59.35  28.835  65.243  28.924  67.057  29.019  71.519  28.199
  73.176  28.248  76.401  28.379  81.644  27.799  86.503  28.186  93.635  28.196
  98.796  28.773 100.833  28.714 105.469  28.871 107.703  29.039 112.923  28.704
 118.727  28.274 121.175  29.259 127.261  33.465 133.383  34.373 133.383  43.517
 152.776  46.864 176.329  46.978
#Mann= 3 , 0 , 0
       0    .035       0       0    .035       0 176.329    .035       0
Bank Sta=0,176.329
XS Rating Curve= 0
Exp/Cntr=.3,.1

Type RM Length L Ch R = 3 ,393.7   ,,,
BEGIN DESCRIPTION:
Ponte di Montuolo
END DESCRIPTION:
Bridge Culvert--1,0,-1,-1, 0
Deck Dist Width WeirC Skew NumUp NumDn MinLoCord MaxHiCord MaxSubmerge Is_Ogee
1.64,16.404,2.61,0, 20, 20, , , .95, 0, 0,0,,
  20.013  39.108  65.256  65.256   67.06   67.06  71.522  71.522  73.163  73.163
  98.786  98.786  100.82  100.82 105.479 105.479  107.71  107.71 133.399 152.789
   46.85   46.85   46.85   46.85   46.85   46.85   46.85   46.85   46.85   46.85
   46.85   46.85   46.85   46.85   46.85   46.85   46.85   46.85   46.85   46.85
   46.85   43.34   43.34  28.904  29.003   43.34   43.34  28.215  28.248   43.34
   43.34  28.773  28.707   43.34   43.34  28.871  29.035   43.34   43.34   46.85
  20.013  39.108  65.256  65.256   67.06   67.06  71.522  71.522  73.163  73.163
  98.786  98.786  100.82  100.82 105.479 105.479  107.71  107.71 133.399 152.789
   46.85   46.85   46.85   46.85   46.85   46.85   46.85   46.85   46.85   46.85
   46.85   46.85   46.85   46.85   46.85   46.85   46.85   46.85   46.85   46.85
   46.85   43.34   43.34  28.904  29.003   43.34   43.34  28.215  28.248   43.34
   43.34  28.773  28.707   43.34   43.34  28.871  29.035   43.34   43.34   46.85
BR Coef=-1 , 0 , 0 ,1.25, 0 ,,,.8,-1,2,0,
WSPro=,,,, 1 ,,,, 0 ,,,, 0 ,,,,-1 ,-1 ,-1 , 0 , 0 , 0 , 0 , 0
BC Design=,, 0 ,, 0 ,,,,,,
BC HTab Sub Flow Pts= 40

Type RM Length L Ch R = 1 ,393     ,3.281,3.281,3.281
XS GIS Cut Line= 3
      5301969.88     15928186.38      5302038.09     15928372.28
      5302040.16     15928377.89
#Sta/Elev= 27
       0  46.621  20.013   46.85  39.108   43.34  39.501  34.711  45.899  33.924
  54.724  33.038   59.35  28.839  65.256  28.904   67.06  29.003  71.522  28.215
  73.163  28.248  76.411  28.379   81.66  27.789  86.516  28.182  93.635  28.182
  98.786  28.773  100.82  28.707 105.479  28.871  107.71  29.035 112.927  28.707
 118.734  28.281 121.161  29.265 127.264  33.465 133.399  34.383 133.858  43.504
 152.789   46.85 176.345  46.982
#Mann= 3 , 0 , 0
       0    .035       0       0    .035       0 176.345    .035       0
Bank Sta=0,176.345
XS Rating Curve= 0
Exp/Cntr=.3,.1

Type RM Length L Ch R = 1 ,392     ,152.165,152.165,152.165
XS GIS Cut Line= 3
      5301956.46     15928203.08      5301992.19     15928340.19
      5301992.19     15928340.22
#Sta/Elev= 19
       0  46.467  16.975   45.42  31.388  35.876  43.799  34.465  53.648  33.038
  58.301  29.455  61.539  28.665   69.76  28.159   78.94  27.454  83.986  27.372
  88.625  27.644  94.865  27.562 106.631  28.438 109.987  30.213 115.197  32.989
 131.378  34.406 144.977  44.993 158.238  45.197 170.387  44.701
#Mann= 3 , 0 , 0
       0    .035       0       0    .035       0 170.387    .035       0
Bank Sta=0,170.387
XS Rating Curve= 0
Exp/Cntr=.3,.1

Type RM Length L Ch R = 1 ,391     ,152.854,152.854,152.854
XS GIS Cut Line= 2
       5301848.11689156561.6797924742834665.348415796768277.5556
#Sta/Elev= 16
       0  45.164  14.449  43.734  26.975  36.663  37.946  35.495  48.202   34.77
  55.535  32.661  60.856  30.492  68.793  28.225  75.981  25.997  87.169  26.224
  97.162   26.49 107.277  27.989 110.896  31.414 127.897  33.474 146.243   42.91
 169.252  43.304
#Mann= 3 , 0 , 0
       0    .035       0       0    .035       0 169.252    .035       0
Bank Sta=0,169.252
XS Rating Curve= 0
Exp/Cntr=.3,.1

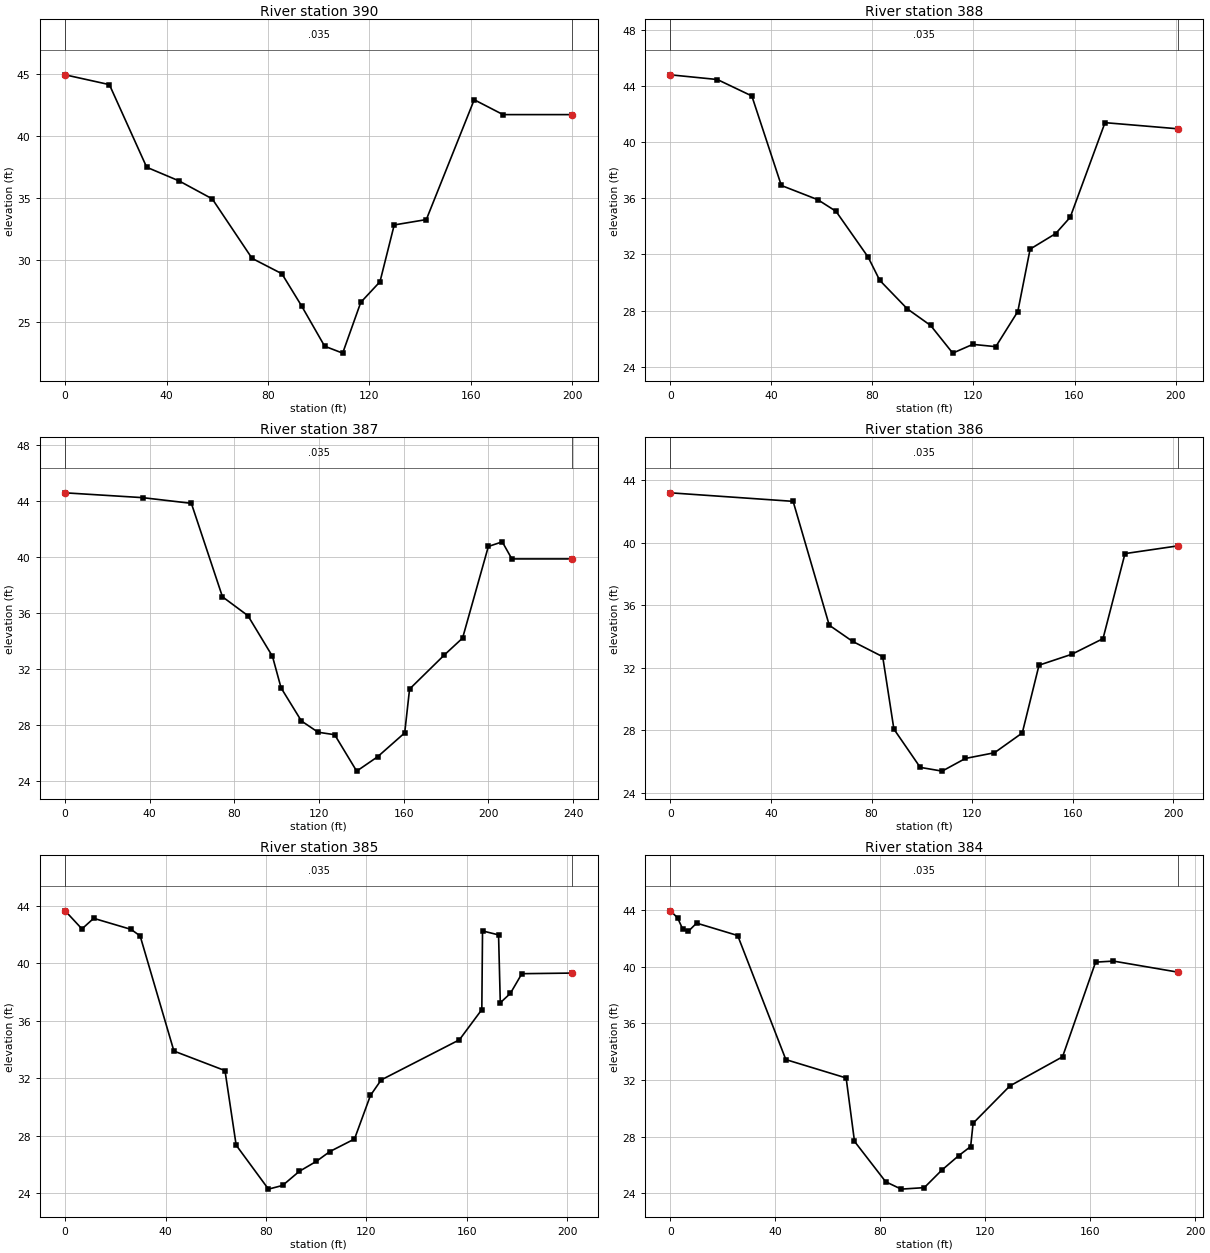
Type RM Length L Ch R = 1 ,390     ,79.068,79.068,79.068
XS GIS Cut Line= 2
      5301743.93     15928169.52      5301748.98     15928157.35
#Sta/Elev= 17
       0  44.944  17.448  44.154  32.165  37.484  44.938  36.381  58.025  34.931
  73.737  30.128  85.492  28.888  93.291  26.283 102.375  23.035 109.488  22.477
 116.627  26.578 124.199  28.238  129.82  32.825 142.487  33.258 161.378  42.933
 172.749  41.732 200.118  41.732
#Mann= 3 , 0 , 0
       0    .035       0       0    .035       0 200.118    .035       0
Bank Sta=0,200.118
XS Rating Curve= 0
Exp/Cntr=.3,.1

Type RM Length L Ch R = 1 ,388     ,72.966,72.966,72.966
XS GIS Cut Line= 2
      5301707.55     15928135.76      5301661.84     15928197.64
#Sta/Elev= 19
       0  44.783  18.576  44.449  32.231  43.278  43.911  36.906  58.323  35.896
  65.561  35.066  78.287  31.804  82.874  30.154  93.783  28.123 103.035  26.939
 111.788   24.97 119.715  25.594 128.832   25.43 137.552  27.933 142.425  32.375
 152.543  33.481 158.301  34.642 172.077  41.378  200.86  40.942
#Mann= 3 , 0 , 0
       0    .035       0       0    .035       0  200.86    .035       0
Bank Sta=0,200.86
XS Rating Curve= 0
Exp/Cntr=.3,.1

Type RM Length L Ch R = 1 ,387     ,213.747,213.747,213.747
XS GIS Cut Line= 2
      5301654.49     15928068.83      5301523.46     15928269.32
#Sta/Elev= 20
       0   44.58  36.585  44.236  59.642  43.829  74.334  37.152  86.362  35.804
  97.966  32.897 102.024  30.646 111.637  28.281 119.521  27.477 127.352    27.3
 137.756  24.698 147.661  25.725 160.446  27.431 162.753  30.561 179.127  32.989
 187.802  34.203 199.977  40.748 206.542  41.079 211.086  39.859 239.695  39.859
#Mann= 3 , 0 , 0
       0    .035       0       0    .035       0 239.695    .035       0
Bank Sta=0,239.695
XS Rating Curve= 0
Exp/Cntr=.3,.1

Type RM Length L Ch R = 1 ,386     ,188.484,188.484,188.484
XS GIS Cut Line= 2
      5301442.81     15927973.82      5301357.02     15928156.36
#Sta/Elev= 16
       0  43.189  48.793  42.644  63.159  34.728  72.441  33.694  84.423  32.713
  88.871  28.087  99.337   25.64 108.058    25.4 117.323  26.211 128.875  26.575
 139.931  27.841 146.585  32.172 159.583  32.867 172.037  33.868 180.781  39.304
 201.739  39.797
#Mann= 3 , 0 , 0
       0    .035       0       0    .035       0 201.739    .035       0
Bank Sta=0,201.739
XS Rating Curve= 0
Exp/Cntr=.3,.1

Type RM Length L Ch R = 1 ,385     ,105.381,105.381,105.381
XS GIS Cut Line= 3
      5301244.23     15927923.75      5301185.73     15928116.73
      5301185.73     15928116.73
#Sta/Elev= 24
       0  43.645    6.69  42.385  11.371  43.123  26.276  42.352  29.882  41.896
  43.343  33.881  63.694   32.52  68.146  27.329  81.014  24.268  86.647  24.524
  93.323  25.509 100.072  26.198 105.472  26.883 115.302  27.759 121.663  30.794
 125.935   31.87 157.103  34.665  166.04  36.768 166.319  42.247 172.707  41.969
 173.402  37.244 177.405  37.894 181.995  39.268 202.136  39.311
#Mann= 3 , 0 , 0
       0    .035       0       0    .035       0 202.136    .035       0
Bank Sta=0,202.136
XS Rating Curve= 0
Exp/Cntr=.3,.1

Type RM Length L Ch R = 1 ,384     ,163.878,163.878,163.878
XS GIS Cut Line= 2
      5301145.47      15927891.7       5301087.3     15928075.56
#Sta/Elev= 21
       0  43.944   2.733  43.445   4.744  42.628   6.847  42.503   9.974  43.077
  25.633  42.201   43.99  33.445  66.972  32.149  70.154  27.674  82.054  24.823
  87.963  24.304  96.752  24.409 103.333  25.627 109.829   26.66 114.429   27.31
 115.361  28.953  129.37  31.585 149.455  33.642 162.051  40.322 168.845  40.397
 193.343  39.619
#Mann= 3 , 0 , 0
       0    .035       0       0    .035       0 193.343    .035       0
Bank Sta=0,193.343
XS Rating Curve= 0
Exp/Cntr=.3,.1

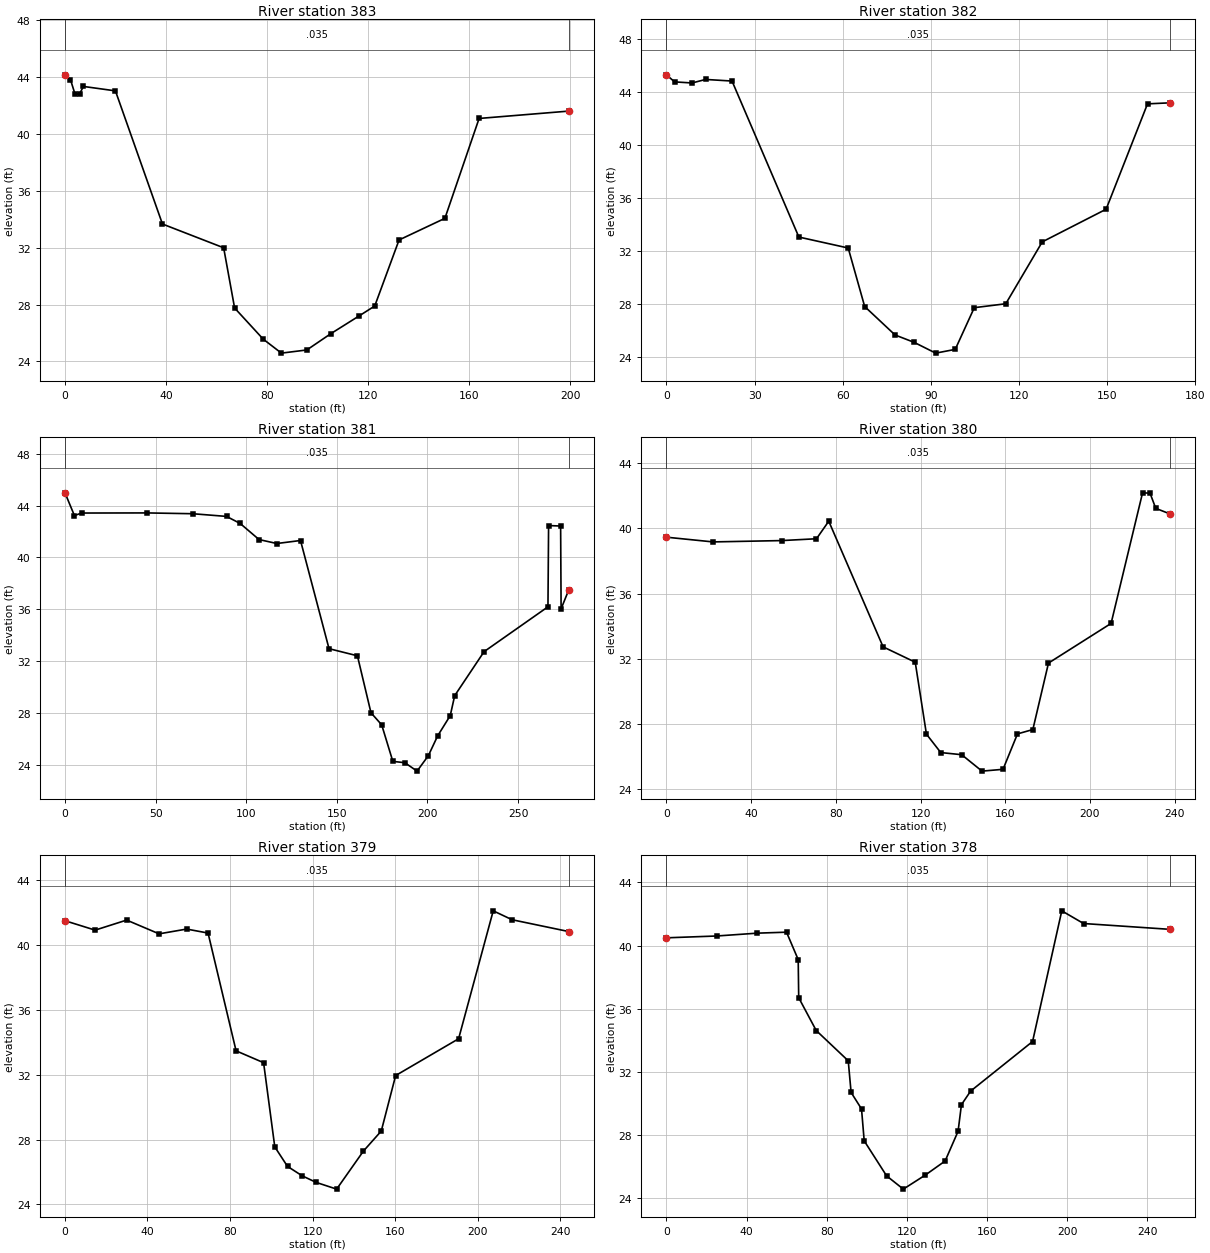
Type RM Length L Ch R = 1 ,383     ,157.874,157.874,157.874
XS GIS Cut Line= 2
       5300989.7     15927842.36      5300925.95     15928031.23
#Sta/Elev= 19
       0   44.17   2.185  43.825   4.012  42.792   5.856  42.851   7.287  43.353
  19.977  43.041  38.596  33.668  62.835  31.995  67.172  27.756  78.501  25.564
  85.702   24.58  95.771  24.803 105.322  25.955 116.614  27.215 122.661  27.897
 132.293  32.546 150.446  34.068 163.986  41.099 199.498  41.617
#Mann= 3 , 0 , 0
       0    .035       0       0    .035       0 199.498    .035       0
Bank Sta=0,199.498
XS Rating Curve= 0
Exp/Cntr=.3,.1

Type RM Length L Ch R = 1 ,382     ,186.877,186.877,186.877
XS GIS Cut Line= 2
       5300846.1     15927791.27      5300783.46     15927950.89
#Sta/Elev= 18
       0  45.292   2.762   44.76    8.72  44.678  13.314  44.944  22.326  44.823
  45.082  33.064  61.883  32.238   67.49  27.828  77.835  25.682   84.35  25.125
  91.673  24.314  98.327  24.596 104.813   27.74 115.538  28.035 127.959    32.7
 149.701  35.161 163.793  43.104 171.539  43.182
#Mann= 3 , 0 , 0
       0    .035       0       0    .035       0 171.539    .035       0
Bank Sta=0,171.539
XS Rating Curve= 0
Exp/Cntr=.3,.1

Type RM Length L Ch R = 1 ,381     ,140.814,140.814,140.814
XS GIS Cut Line= 2
      5300705.45     15927633.43      5300606.33     15927892.52
#Sta/Elev= 27
       0  44.977   5.207  43.222   9.131  43.419  45.289  43.428  70.466  43.366
  89.124  43.159  96.627  42.618 107.073  41.375 116.886   41.07 129.951  41.302
 145.676  32.963 161.342  32.415 168.822  28.025 174.741   27.09 180.883  24.275
 187.536  24.173 194.245  23.524 200.479  24.715 205.633  26.247 212.559  27.805
 215.007  29.341 231.214  32.733  266.47  36.191 266.818  42.454 273.458  42.418
  273.72  36.033 277.953  37.497
#Mann= 3 , 0 , 0
       0    .035       0       0    .035       0 277.953    .035       0
Bank Sta=0,277.953
XS Rating Curve= 0
Exp/Cntr=.3,.1

Type RM Length L Ch R = 1 ,380     ,160.892,160.892,160.892
XS GIS Cut Line= 2
      5300555.51     15927627.49      5300471.29     15927849.93
#Sta/Elev= 20
       0  39.452  21.988  39.163  54.472  39.245  70.853  39.357  76.647  40.433
  102.31   32.73 117.484  31.788 122.776  27.379 129.541   26.25 139.419  26.119
 149.029  25.112 158.947  25.223 165.774  27.395 173.031  27.661 180.413  31.736
  209.98  34.167 224.843  42.172 228.373  42.152 231.073   41.22 237.923  40.873
#Mann= 3 , 0 , 0
       0    .035       0       0    .035       0 237.923    .035       0
Bank Sta=0,237.923
XS Rating Curve= 0
Exp/Cntr=.3,.1

Type RM Length L Ch R = 1 ,379     ,186.713,186.713,186.713
XS GIS Cut Line= 3
      5300391.63     15927590.65      5300316.24      15927822.8
      5300316.24     15927822.83
#Sta/Elev= 20
       0  41.512  14.616  40.932  29.895  41.552   45.62  40.702   58.97  40.997
  69.357  40.751  82.936  33.481  96.273  32.749 101.699  27.552 107.864  26.348
     115  25.764 121.739  25.361 131.686  24.944 144.695  27.297  153.32   28.53
 160.285  31.955 190.804  34.226 207.585  42.123 216.752  41.572 244.209  40.843
#Mann= 3 , 0 , 0
       0    .035       0       0    .035       0 244.209    .035       0
Bank Sta=0,244.209
XS Rating Curve= 0
Exp/Cntr=.3,.1

Type RM Length L Ch R = 1 ,378     ,151.115,151.115,151.115
XS GIS Cut Line= 2
      5300219.26     15927538.68      5300130.09     15927773.56
#Sta/Elev= 22
       0  40.489  25.072  40.604  45.374  40.784  59.951  40.846  65.778  39.108
   66.03  36.696  74.764  34.619  90.761    32.7  92.188  30.696  97.392  29.652
   98.73  27.631 109.918  25.413 118.264  24.573 129.314  25.469  139.14  26.355
 145.607  28.238  147.28  29.921  151.87  30.781 182.799  33.921 197.379  42.198
 208.264  41.394 251.542  41.024
#Mann= 3 , 0 , 0
       0    .035       0       0    .035       0 251.542    .035       0
Bank Sta=0,251.542
XS Rating Curve= 0
Exp/Cntr=.3,.1

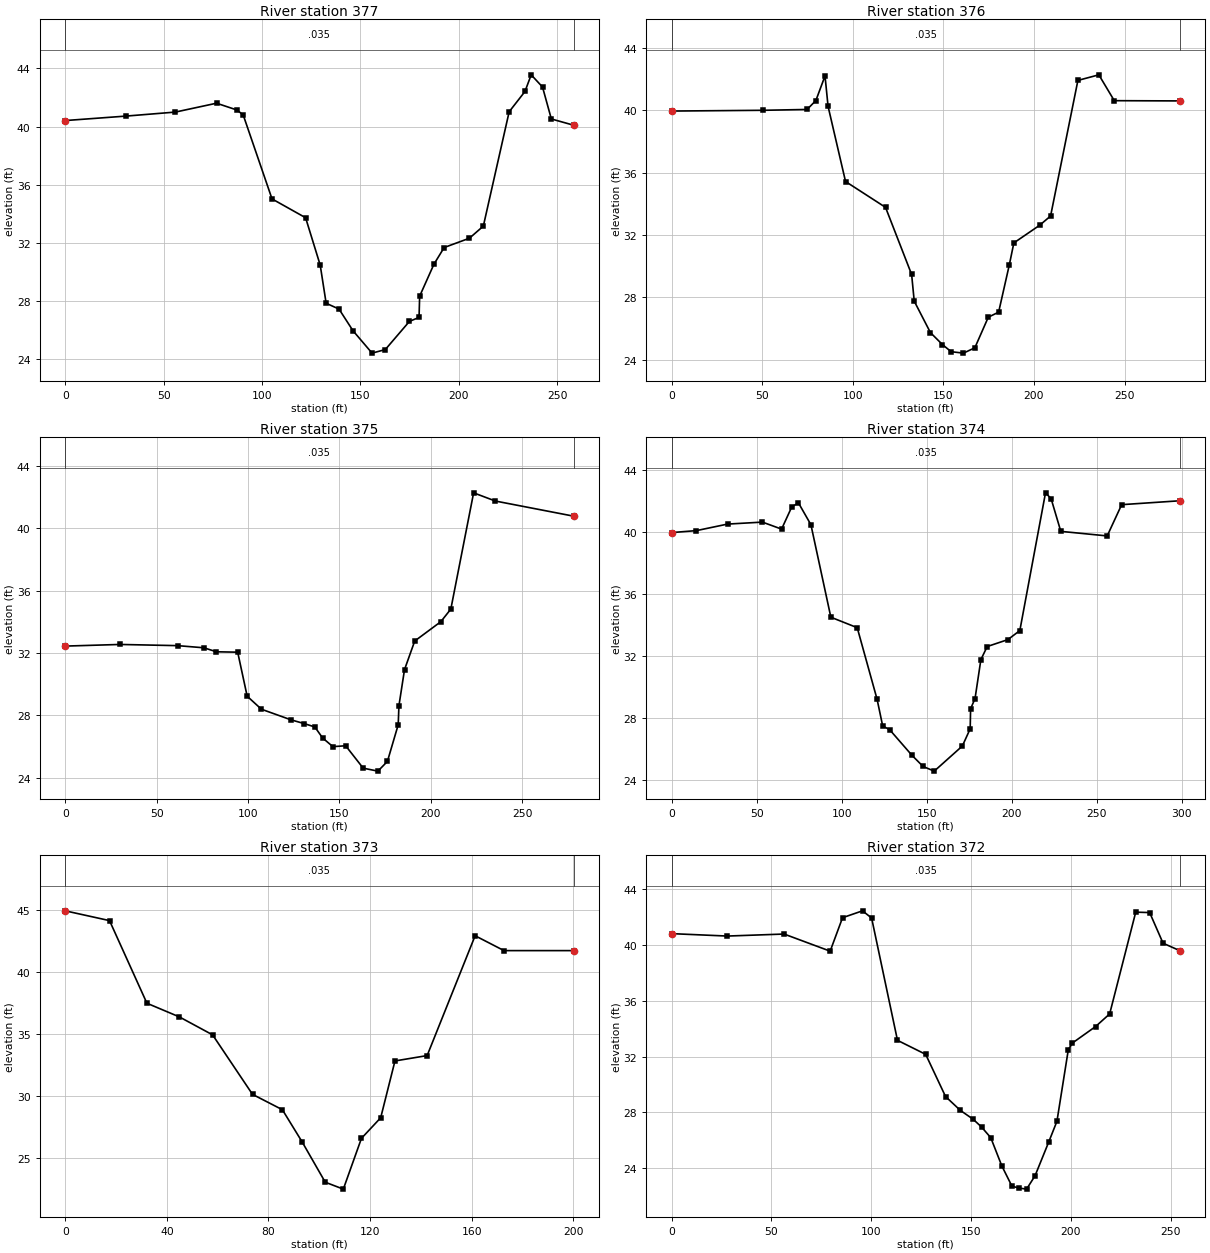
Type RM Length L Ch R = 1 ,377     ,153.084,153.084,153.084
XS GIS Cut Line= 2
      5300099.21     15927457.81      5300063.06     15927537.47
#Sta/Elev= 27
       0  40.413  31.033  40.722  56.001  40.997  76.936  41.608  87.467  41.132
  90.518  40.784 105.128  35.016 122.198   33.72 129.639  30.449 132.641  27.828
  139.19  27.428 146.293  25.935 155.991  24.393  162.72  24.639  174.97  26.578
 179.869  26.854 180.177  28.314 187.444  30.518 192.631  31.667 205.453  32.306
 212.553  33.143 225.679   41.02 233.707  42.415  236.88  43.563 242.638  42.723
 247.119  40.522 258.402  40.095
#Mann= 3 , 0 , 0
       0    .035       0       0    .035       0 258.402    .035       0
Bank Sta=0,258.402
XS Rating Curve= 0
Exp/Cntr=.3,.1

Type RM Length L Ch R = 1 ,376     ,178.084,178.084,178.084
XS GIS Cut Line= 2
      5299962.43     15927400.36      5299924.97     15927476.35
#Sta/Elev= 25
       0  39.944  50.614  39.993  74.728  40.046  79.603  40.617  84.649  42.198
  86.335  40.246  95.974  35.427 118.054   33.77 132.464  29.465 133.894  27.756
 142.848  25.738 149.449  24.974 154.281  24.514 161.053  24.423 167.356  24.764
 174.777  26.726 180.486  27.051 186.388  30.082 188.891   31.49  203.13  32.621
  209.17  33.215 224.249  41.909  235.81  42.267 244.331   40.61  280.61  40.594
#Mann= 3 , 0 , 0
       0    .035       0       0    .035       0  280.61    .035       0
Bank Sta=0,280.61
XS Rating Curve= 0
Exp/Cntr=.3,.1

Type RM Length L Ch R = 1 ,375     ,163.583,163.583,163.583
XS GIS Cut Line= 2
      5299808.83     15927322.74      5299677.95     15927567.68
#Sta/Elev= 26
       0  32.441   29.97  32.546  61.509   32.47  75.853  32.333  82.753  32.077
   94.36  32.051  99.544  29.232 107.339  28.399 123.458  27.723 130.712   27.48
 136.549  27.264  140.85  26.555  146.44  26.004 153.425   26.06 163.018  24.626
 171.073  24.436 176.266  25.059 182.169  27.405 182.569  28.625 185.617  30.932
 191.204  32.766 205.476  34.003 210.958   34.81 223.422  42.254 235.299  41.729
 278.084  40.761
#Mann= 3 , 0 , 0
       0    .035       0       0    .035       0 278.084    .035       0
Bank Sta=0,278.084
XS Rating Curve= 0
Exp/Cntr=.3,.1

Type RM Length L Ch R = 1 ,374     ,145.144,145.144,145.144
XS GIS Cut Line= 2
      5299672.64     15927250.39      5299633.37     15927313.78
#Sta/Elev= 30
       0   39.97    14.6  40.098  32.871  40.518  53.386  40.646  64.656  40.194
  70.686  41.634   74.59  41.886  81.913  40.479  93.642  34.508 109.154  33.832
 120.853  29.206 124.131   27.49 128.245  27.247 141.227   25.61  147.92  24.872
 154.475  24.573 171.007  26.194 175.617  27.306  175.86  28.599 178.461  29.252
 181.909  31.772 185.633  32.615 197.776  33.061  204.82  33.645 219.928  42.536
 223.222  42.159 228.924  40.049 256.217  39.754 264.728  41.772 299.049  42.024
#Mann= 3 , 0 , 0
       0    .035       0       0    .035       0 299.049    .035       0
Bank Sta=0,299.049
XS Rating Curve= 0
Exp/Cntr=.3,.1

Type RM Length L Ch R = 1 ,373     ,181.824,181.824,181.824
XS GIS Cut Line= 2
      5299552.56     15927156.14      5299546.52     15927166.83
#Sta/Elev= 17
       0  44.944  17.448  44.154  32.165  37.484  44.938  36.381  58.025  34.931
  73.737  30.128  85.492  28.888  93.291  26.283 102.375  23.035 109.488  22.477
 116.627  26.578 124.199  28.238  129.82  32.825 142.487  33.258 161.378  42.933
 172.749  41.732 200.118  41.732
#Mann= 3 , 0 , 0
       0    .035       0       0    .035       0 200.118    .035       0
Bank Sta=0,200.118
XS Rating Curve= 0
Exp/Cntr=.3,.1

Type RM Length L Ch R = 1 ,372     ,170.571,170.571,170.571
XS GIS Cut Line= 2
      5299400.98     15927075.52      5299349.48     15927156.04
#Sta/Elev= 29
       0  40.787  27.828  40.614  56.312  40.758   79.39  39.534  85.587  41.926
  95.594  42.418 100.154  41.903 113.107  33.159 127.238  32.156 137.188   29.14
   144.6   28.15 150.978   27.52  155.23  26.959 159.836  26.198 165.354  24.186
 170.446   22.73  173.96  22.598 177.769   22.52 182.008  23.471 188.825  25.873
 192.986  27.372 198.691    32.5 200.755  32.969 212.329  34.144 219.386  35.046
 232.447  42.323 239.429  42.293 246.145  40.102 254.626  39.564
#Mann= 3 , 0 , 0
       0    .035       0       0    .035       0 254.626    .035       0
Bank Sta=0,254.626
XS Rating Curve= 0
Exp/Cntr=.3,.1