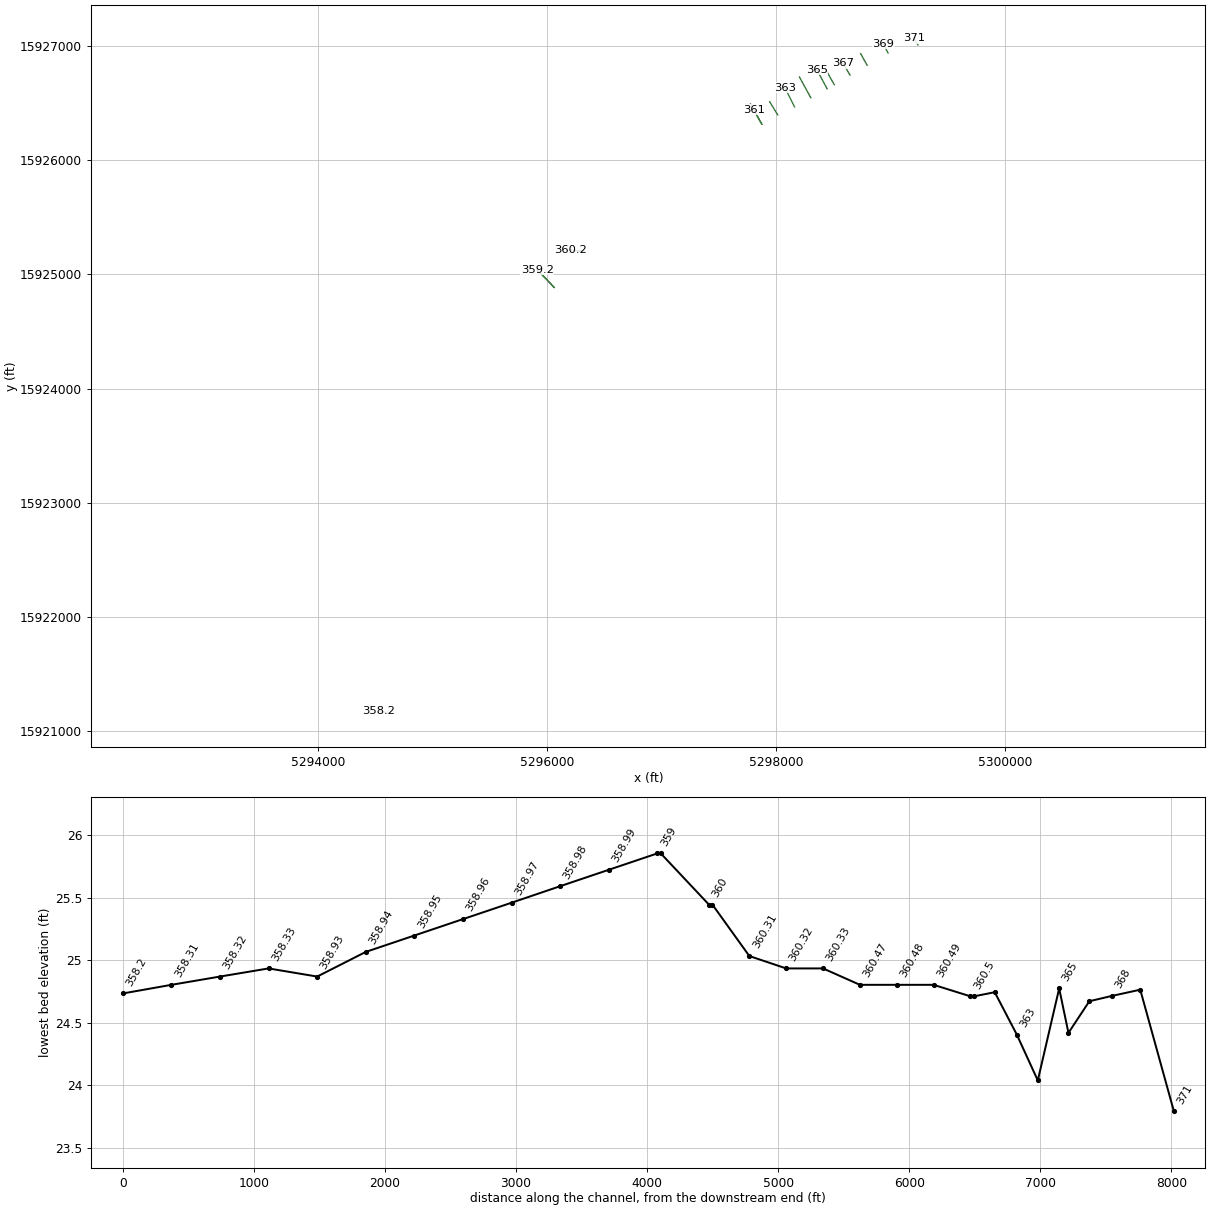
HEC-RAS study ozz_def.prj: ozzeri

--- ozz_def.g04 (geometry) --- (continued)

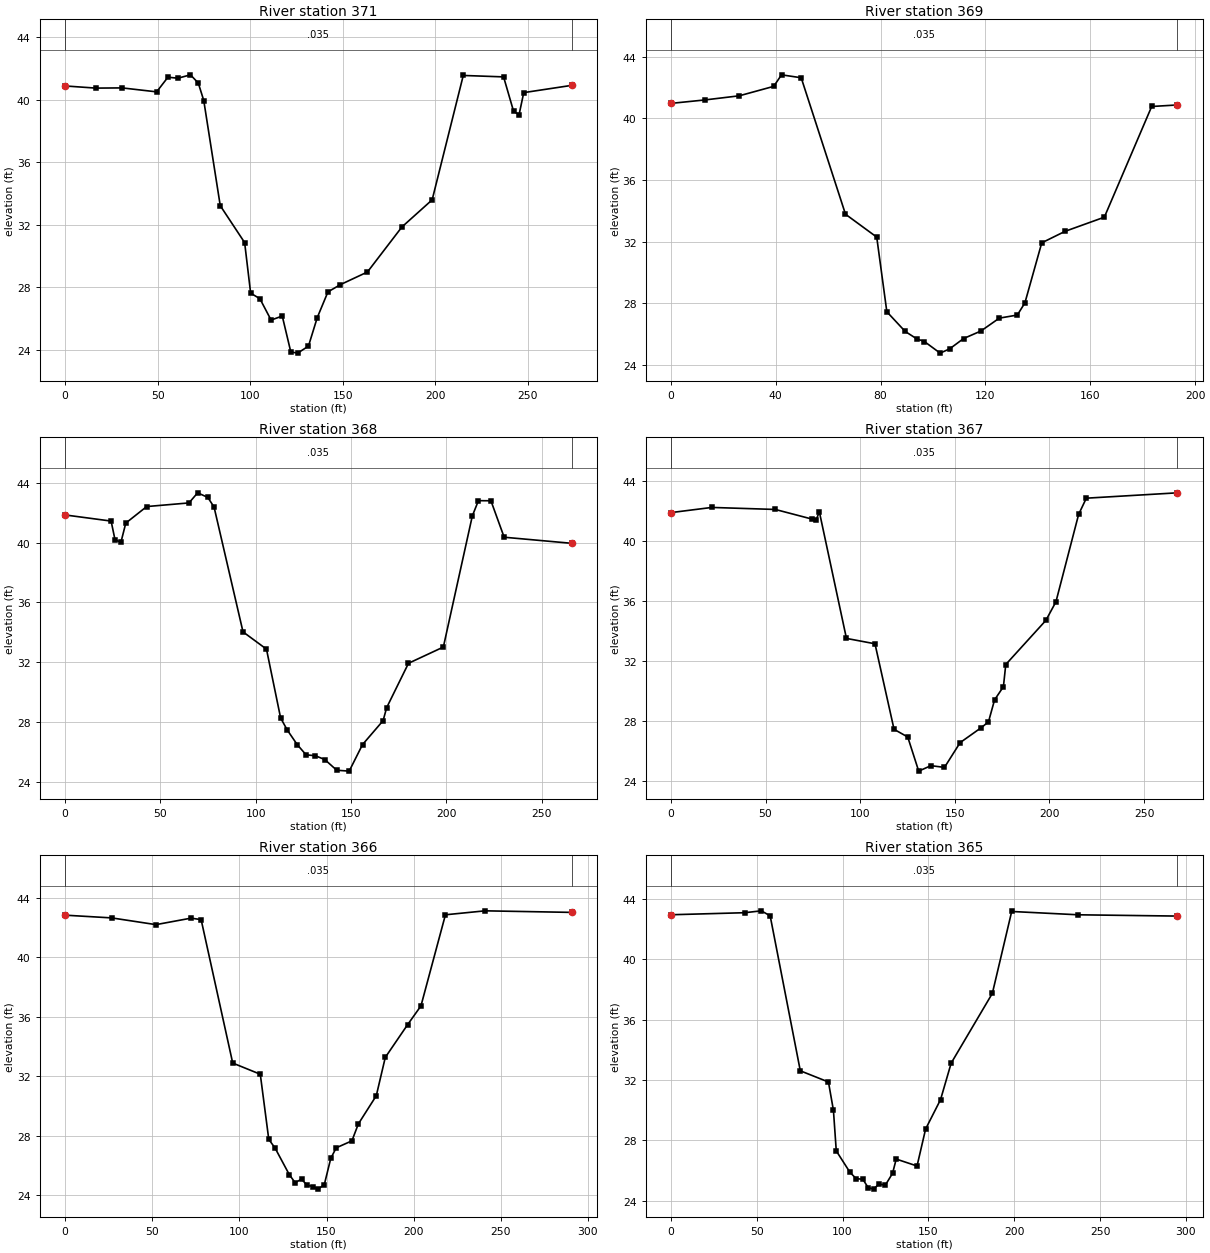
Type RM Length L Ch R = 1 ,371     ,256.627,256.627,256.627
XS GIS Cut Line= 2
      5299237.57     15927009.32       5299202.1     15927067.03
#Sta/Elev= 30
       0  40.896  16.568  40.758  30.846  40.771  49.465  40.518  55.581  41.457
  60.965  41.391  67.753  41.608  71.975  41.083  74.934  39.964  83.848  33.232
  97.028  30.869 100.269  27.635 105.285  27.274 111.322  25.909 117.359  26.168
 121.972  23.871 125.673  23.793 131.526  24.242 136.266  26.063 142.051  27.713
 148.812  28.179 163.392  28.986 182.041   31.87 198.379  33.606  215.19  41.568
 236.985  41.476 242.408  39.265 245.371  39.068 247.874  40.469  273.72  40.932
#Mann= 3 , 0 , 0
       0    .035       0       0    .035       0  273.72    .035       0
Bank Sta=0,273.72
XS Rating Curve= 0
Exp/Cntr=.3,.1

Type RM Length L Ch R = 1 ,369     ,213.911,213.911,213.911
XS GIS Cut Line= 2
      5298976.77     15926937.93      5298933.63     15927020.93
#Sta/Elev= 24
       0  40.965  12.927  41.188  26.083  41.457  39.226   42.07  42.208  42.818
  49.715  42.628  66.608  33.776   78.53   32.29  82.385  27.448  89.357  26.175
  93.809  25.689  96.696  25.518 102.726  24.764 106.391  25.046 111.654  25.709
 118.268  26.198 125.289  27.034 132.159  27.234 135.053  28.022  141.48  31.919
 150.404  32.667 165.364  33.583 183.422  40.764 193.205  40.863
#Mann= 3 , 0 , 0
       0    .035       0       0    .035       0 193.205    .035       0
Bank Sta=0,193.205
XS Rating Curve= 0
Exp/Cntr=.3,.1

Type RM Length L Ch R = 1 ,368     ,174.344,174.344,174.344
XS GIS Cut Line= 2
      5298793.27     15926831.53      5298736.88     15926932.81
#Sta/Elev= 30
       0  41.844  24.134  41.434  26.168   40.19  29.272  40.013  31.834  41.299
  42.802  42.405  64.984  42.648  69.521  43.323  74.856  43.018   78.15  42.372
  93.337  34.026 105.646  32.871 113.064  28.271 116.522   27.47 121.762   26.49
  126.43  25.804 131.257  25.745 136.237  25.489  142.52  24.774 149.049  24.715
  156.04   26.49 166.841  28.091 168.701  28.957 180.154  31.926 198.455  33.012
 213.652  41.778 216.844  42.799 223.412  42.792 230.348  40.354 265.715  39.948
#Mann= 3 , 0 , 0
       0    .035       0       0    .035       0 265.715    .035       0
Bank Sta=0,265.715
XS Rating Curve= 0
Exp/Cntr=.3,.1

Type RM Length L Ch R = 1 ,367     ,159.547,159.547,159.547
XS GIS Cut Line= 2
      5298644.16     15926745.14       5298583.6     15926846.98
#Sta/Elev= 24
       0  41.909  21.627  42.254  55.161  42.119  74.472   41.48  76.768  41.417
  78.412  41.972  92.746   33.52 107.818  33.163 117.887  27.461 125.128  26.946
 130.915  24.672 137.379  25.036 144.531  24.921 152.792  26.572 164.003  27.575
 167.772  27.956 170.997  29.426 175.666  30.302 176.906  31.781 198.081  34.721
 203.399  35.958 215.397  41.791 219.462  42.871 267.536  43.228
#Mann= 3 , 0 , 0
       0    .035       0       0    .035       0 267.536    .035       0
Bank Sta=0,267.536
XS Rating Curve= 0
Exp/Cntr=.3,.1

Type RM Length L Ch R = 1 ,366     ,70.768,70.768,70.768
XS GIS Cut Line= 2
       5298506.4     15926661.38      5298434.48     15926788.48
#Sta/Elev= 27
       0  42.828  26.772  42.644  52.136  42.192  72.244  42.628  78.051   42.53
  96.175   32.89 112.001  32.139 116.864  27.766 120.518  27.172 128.615    25.4
 132.014  24.846 135.663  25.095 138.658  24.698 142.195   24.59 145.157  24.419
 148.734  24.724 152.454   26.49 155.577  27.195 164.577  27.664 168.264  28.799
 178.563  30.696 183.727  33.271 196.545  35.472 204.196  36.732 218.238  42.854
 241.007   43.12 290.617  43.015
#Mann= 3 , 0 , 0
       0    .035       0       0    .035       0 290.617    .035       0
Bank Sta=0,290.617
XS Rating Curve= 0
Exp/Cntr=.3,.1

Type RM Length L Ch R = 1 ,365     ,163.058,163.058,163.058
XS GIS Cut Line= 2
      5298443.73     15926625.79      5298353.74     15926792.65
#Sta/Elev= 25
       0  42.949  42.979  43.084  52.723  43.209  57.838  42.874   75.39  32.612
  91.785   31.87  94.685  29.997  96.342  27.306 104.311  25.889 107.953  25.466
 111.808   25.43 114.918  24.875  118.11  24.774  121.23  25.115 124.875   25.03
 129.127   25.82  131.26  26.765 143.389  26.306 148.386  28.757 157.083  30.702
 163.271   33.12 187.267  37.743 198.524  43.166 237.336  42.946 295.013  42.861
#Mann= 3 , 0 , 0
       0    .035       0       0    .035       0 295.013    .035       0
Bank Sta=0,295.013
XS Rating Curve= 0
Exp/Cntr=.3,.1

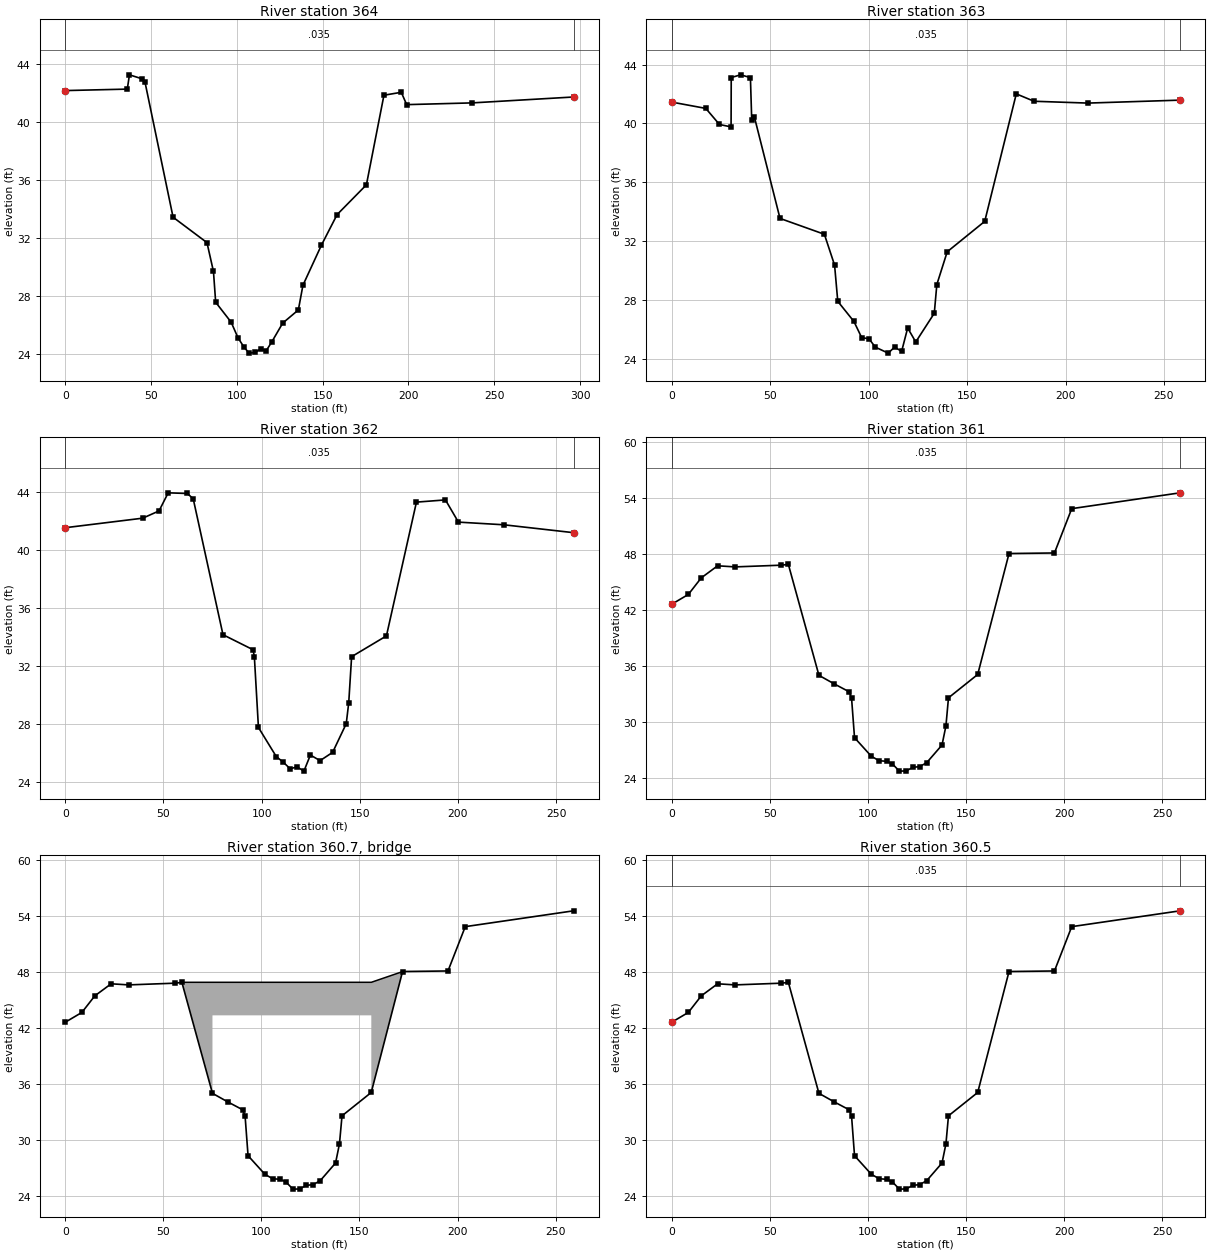
Type RM Length L Ch R = 1 ,364     ,160.531,160.531,160.531
XS GIS Cut Line= 2
      5298301.61     15926546.75      5298202.07     15926728.44
#Sta/Elev= 28
       0  42.185  36.175  42.287  37.431  43.274  44.514  43.009  46.473  42.779
  62.851  33.432  82.602  31.677  86.385  29.682  87.674  27.556  96.706  26.175
 100.689  25.095 104.167  24.455 107.159  24.039 110.869  24.085 113.842  24.347
 117.047   24.19  120.44  24.829 126.739  26.115  135.85  27.024  138.52   28.73
 149.337  31.512 158.435  33.615 175.509  35.673 185.719  41.864  195.82  42.067
 198.967  41.214 237.254  41.335 296.194  41.742
#Mann= 3 , 0 , 0
       0    .035       0       0    .035       0 296.194    .035       0
Bank Sta=0,296.194
XS Rating Curve= 0
Exp/Cntr=.3,.1

Type RM Length L Ch R = 1 ,363     ,168.143,168.143,168.143
XS GIS Cut Line= 2
      5298159.51     15926466.57      5298075.33     15926634.81
#Sta/Elev= 30
       0  41.453  17.333  41.024  24.252  39.934  30.164  39.767  30.243   43.12
  35.003  43.304  39.987  43.117  40.646  40.246  42.041   40.42   55.01  33.553
  77.543  32.477  82.726  30.381  84.344  27.923  92.549  26.555  96.522  25.449
 100.135   25.39 103.415  24.813 109.944  24.406 113.245   24.82 116.762  24.521
 119.836  26.112  123.94  25.164 133.356  27.113 134.649  29.065 139.921  31.289
 158.967  33.353  174.99  42.011 184.009  41.509 211.371  41.385 258.127  41.585
#Mann= 3 , 0 , 0
       0    .035       0       0    .035       0 258.127    .035       0
Bank Sta=0,258.127
XS Rating Curve= 0
Exp/Cntr=.3,.1

Type RM Length L Ch R = 1 ,362     ,158.924,158.924,158.924
XS GIS Cut Line= 2
       5298012.4     15926396.88      5297942.39     15926511.65
#Sta/Elev= 27
       0  41.562  39.455  42.221  47.776  42.723  52.444  43.973  62.188  43.927
  65.177  43.566  80.344   34.17  95.643  33.133  96.319  32.657  98.396  27.762
 107.474  25.751 111.096  25.354 114.577  24.905 118.061  25.039 121.552  24.744
 124.846  25.856 129.783  25.469 136.175   26.04  143.11  28.022 144.386  29.482
 145.843  32.651 163.576  34.088 178.855   43.33 193.619  43.484 200.233  41.949
  223.36  41.765 258.852   41.22
#Mann= 3 , 0 , 0
       0    .035       0       0    .035       0 258.852    .035       0
Bank Sta=0,258.852
XS Rating Curve= 0
Exp/Cntr=.3,.1

Type RM Length L Ch R = 1 ,361     ,26.247,26.247,26.247
XS GIS Cut Line= 2
      5297873.52     15926314.83      5297802.17      15926443.5
#Sta/Elev= 29
       0  42.598   8.497  43.652  15.092   45.43  23.425  46.722  32.316  46.604
  55.971  46.788  59.482  46.873  75.066   34.98  82.907  34.058  90.486  33.215
  91.699  32.539  93.209  28.294 101.795  26.302 105.741  25.827 109.551  25.764
 112.556  25.479 116.053  24.711 119.436  24.728 122.986  25.118 126.434  25.194
     130  25.617 137.812   27.51  139.81   29.57 141.103  32.569 156.002  35.072
 171.965  48.038 195.128  48.097  203.93  52.848 259.124  54.544
#Mann= 3 , 0 , 0
       0    .035       0       0    .035       0 259.124    .035       0
Bank Sta=0,259.124
XS Rating Curve= 0
Exp/Cntr=.3,.1

Type RM Length L Ch R = 3 ,360.7   ,,,
BEGIN DESCRIPTION:
ponte di cerasomma
END DESCRIPTION:
Bridge Culvert--1,0,-1,-1, 0
Deck Dist Width WeirC Skew NumUp NumDn MinLoCord MaxHiCord MaxSubmerge Is_Ogee
1.64,22.966,2.61,0, 6, 6, , , .95, 0, 0,0,,
  59.482  75.066  75.066 156.037 156.037 171.982
  46.883  46.883  46.883  46.883  46.883  48.031
  46.883  34.974   43.34   43.34  35.072  48.031
  59.482  75.066  75.066 156.037 156.037 171.982
  46.883  46.883  46.883  46.883  46.883  48.031
  46.883  34.974   43.34   43.34  35.072  48.031
BR Coef=-1 , 0 , 0 ,1.25, 0 ,,,.8,-1,2,0,
WSPro=,,,, 1 ,,,, 0 ,,,, 0 ,,,,-1 ,-1 ,-1 , 0 , 0 , 0 , 0 , 0
BC Design=,, 0 ,, 0 ,,,,,,
BC HTab Sub Flow Pts= 40

Type RM Length L Ch R = 1 ,360.5   ,281.168,281.168,281.168
XS GIS Cut Line= 2
      5297873.52     15926314.83      5297774.97     15926492.45
#Sta/Elev= 29
       0  42.598   8.497  43.652  15.092   45.43  23.425  46.722  32.316  46.604
  55.971  46.788  59.482  46.873  75.066   34.98  82.907  34.058  90.486  33.215
  91.699  32.539  93.209  28.294 101.795  26.302 105.741  25.827 109.551  25.764
 112.556  25.479 116.053  24.711 119.436  24.728 122.986  25.118 126.434  25.194
     130  25.617 137.812   27.51  139.81   29.57 141.103  32.569 156.002  35.072
 171.965  48.038 195.128  48.097  203.93  52.848 259.124  54.544
#Mann= 3 , 0 , 0
       0    .035       0       0    .035       0 259.124    .035       0
Bank Sta=0,259.124
XS Rating Curve= 0
Exp/Cntr=.3,.1

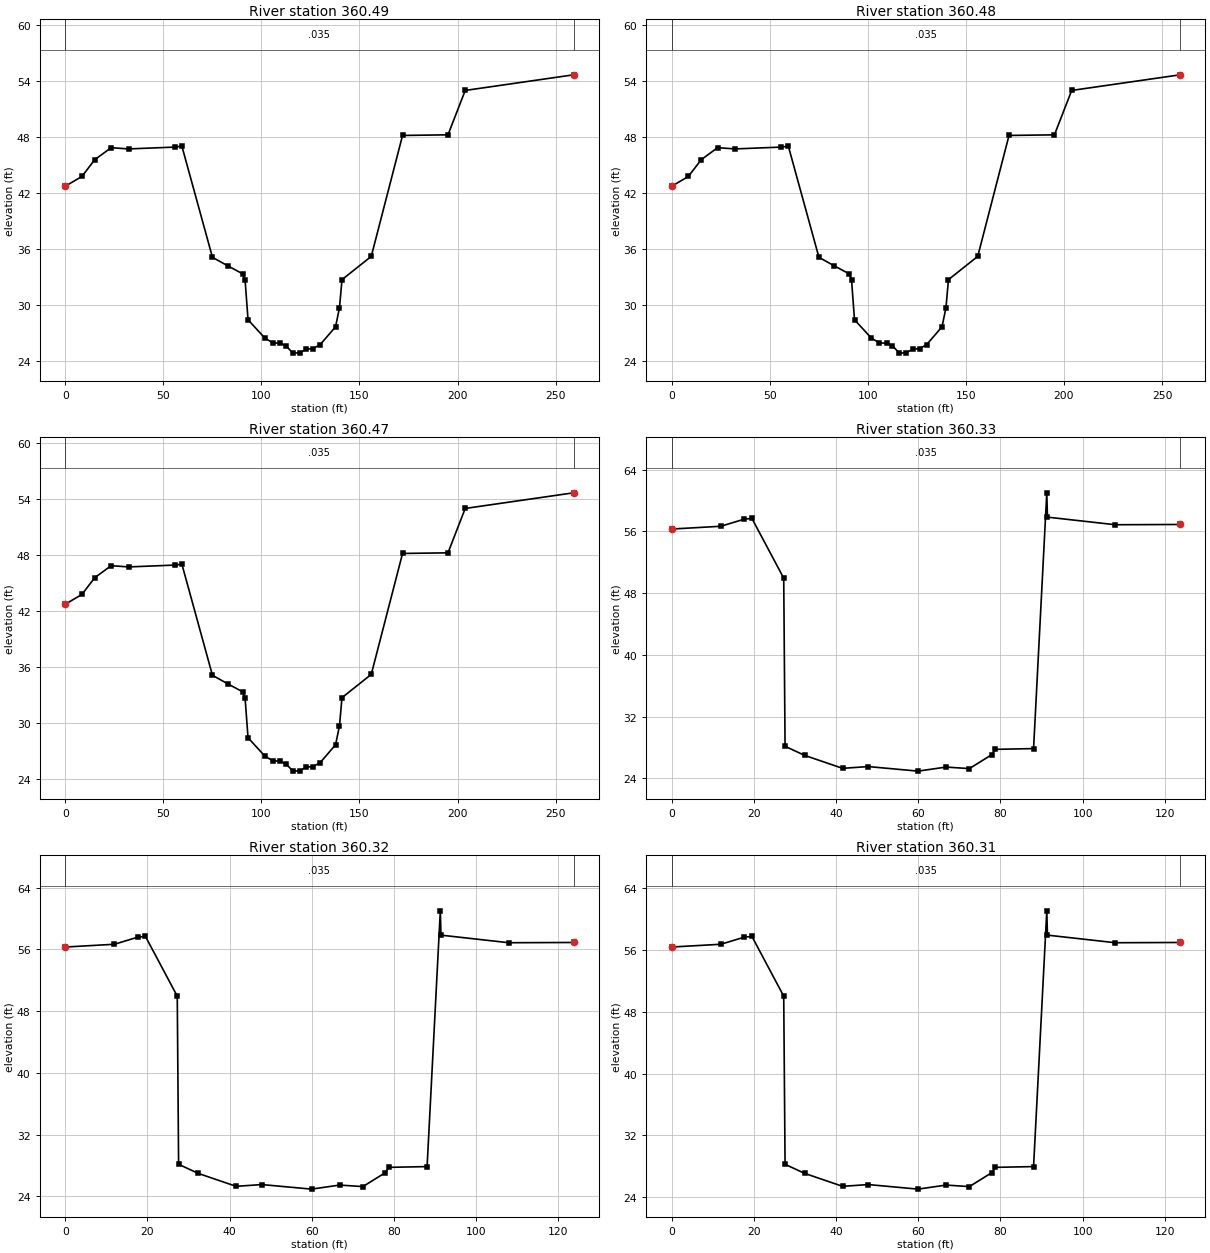
Type RM Length L Ch R = 1 ,360.49  ,281.168,281.168,281.168
BEGIN DESCRIPTION:
come 360.5 z=z+0.03
END DESCRIPTION:
#Sta/Elev= 29
       0  42.684   8.497  43.734  15.092  45.538  23.425  46.818  32.316  46.686
  55.971  46.883  59.482  46.982  75.066  35.072  82.907  34.154  90.486  33.301
  91.699  32.644  93.209  28.379 101.804  26.411 105.741  25.919  109.58  25.853
 112.566  25.591 116.076  24.803 119.455  24.836 122.999   25.23 126.444  25.295
  130.02  25.722 137.828  27.625 139.829  29.659 141.109  32.677 156.037  35.171
 171.982   48.13 195.144  48.196 203.937  52.953 259.154  54.626
#Mann= 3 , 0 , 0
       0    .035       0       0    .035       0 259.154    .035       0
Bank Sta=0,259.154
XS Rating Curve= 0
Exp/Cntr=.3,.1

Type RM Length L Ch R = 1 ,360.48  ,281.168,281.168,281.168
BEGIN DESCRIPTION:
come 360.49 z=z+0.03
END DESCRIPTION:
#Sta/Elev= 29
       0  42.684   8.497  43.734  15.092  45.538  23.425  46.818  32.316  46.686
  55.971  46.883  59.482  46.982  75.066  35.072  82.907  34.154  90.486  33.301
  91.699  32.644  93.209  28.379 101.804  26.411 105.741  25.919  109.58  25.853
 112.566  25.591 116.076  24.803 119.455  24.836 122.999   25.23 126.444  25.295
  130.02  25.722 137.828  27.625 139.829  29.659 141.109  32.677 156.037  35.171
 171.982   48.13 195.144  48.196 203.937  52.953 259.154  54.626
#Mann= 3 , 0 , 0
       0    .035       0       0    .035       0 259.154    .035       0
Bank Sta=0,259.154
XS Rating Curve= 0
Exp/Cntr=.3,.1

Type RM Length L Ch R = 1 ,360.47  ,281.168,281.168,281.168
BEGIN DESCRIPTION:
come 360.48 z=z+0.03
END DESCRIPTION:
#Sta/Elev= 29
       0  42.684   8.497  43.734  15.092  45.538  23.425  46.818  32.316  46.686
  55.971  46.883  59.482  46.982  75.066  35.072  82.907  34.154  90.486  33.301
  91.699  32.644  93.209  28.379 101.804  26.411 105.741  25.919  109.58  25.853
 112.566  25.591 116.076  24.803 119.455  24.836 122.999   25.23 126.444  25.295
  130.02  25.722 137.828  27.625 139.829  29.659 141.109  32.677 156.037  35.171
 171.982   48.13 195.144  48.196 203.937  52.953 259.154  54.626
#Mann= 3 , 0 , 0
       0    .035       0       0    .035       0 259.154    .035       0
Bank Sta=0,259.154
XS Rating Curve= 0
Exp/Cntr=.3,.1

Type RM Length L Ch R = 1 ,360.33  ,281.168,281.168,281.168
BEGIN DESCRIPTION:
come 360.32 z=z-0.03
END DESCRIPTION:
#Sta/Elev= 19
       0  56.299  11.975   56.66  17.651  57.579  19.521  57.677  27.264  49.934
  27.592   28.15  32.382  26.969  41.601  25.295  47.835  25.525  59.941  24.934
  66.765  25.459  72.441  25.262  77.887  27.067  78.773  27.756  88.058  27.854
  91.273  60.991  91.437  57.841  107.94  56.857 123.688   56.89
#Mann= 3 , 0 , 0
       0    .035       0       0    .035       0 123.688    .035       0
Bank Sta=0,123.688
XS Rating Curve= 0
Exp/Cntr=.3,.1

Type RM Length L Ch R = 1 ,360.32  ,281.168,281.168,281.168
BEGIN DESCRIPTION:
come 360.31 z=z-0.03
END DESCRIPTION:
#Sta/Elev= 19
       0  56.299  11.975   56.66  17.651  57.579  19.521  57.677  27.264  49.934
  27.592   28.15  32.382  26.969  41.601  25.295  47.835  25.525  59.941  24.934
  66.765  25.459  72.441  25.262  77.887  27.067  78.773  27.756  88.058  27.854
  91.273  60.991  91.437  57.841  107.94  56.857 123.688   56.89
#Mann= 3 , 0 , 0
       0    .035       0       0    .035       0 123.688    .035       0
Bank Sta=0,123.688
XS Rating Curve= 0
Exp/Cntr=.3,.1

Type RM Length L Ch R = 1 ,360.31  ,281.168,281.168,281.168
BEGIN DESCRIPTION:
come 360.2 z=z-0.03
END DESCRIPTION:
#Sta/Elev= 19
       0  56.398  11.975  56.759  17.651  57.677  19.521  57.776  27.264  50.033
  27.592  28.248  32.382  27.067  41.601  25.394  47.835  25.623  59.941  25.033
  66.765  25.558  72.441  25.361  77.887  27.165  78.773  27.854  88.058  27.953
  91.273  61.089  91.437   57.94  107.94  56.955 123.688  56.988
#Mann= 3 , 0 , 0
       0    .035       0       0    .035       0 123.688    .035       0
Bank Sta=0,123.688
XS Rating Curve= 0
Exp/Cntr=.3,.1

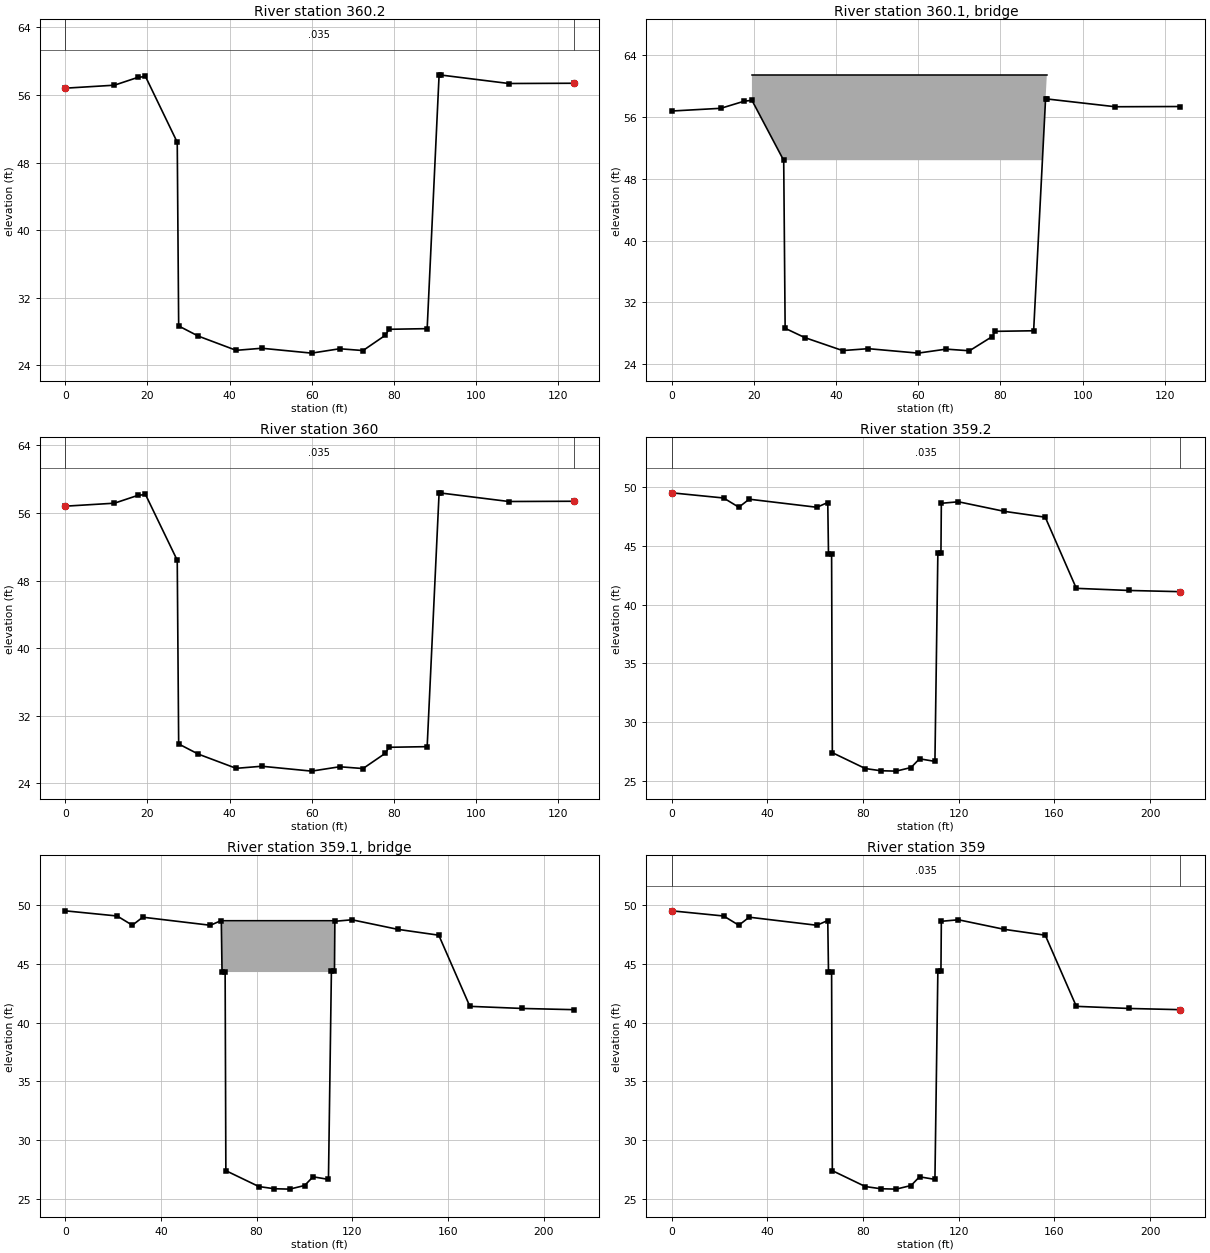
Type RM Length L Ch R = 1 ,360.2   ,26.247,26.247,26.247
XS GIS Cut Line= 2
      5296321.56     15925201.21       5296199.7     15925212.63
#Sta/Elev= 19
       0  56.795  11.972  57.149  17.657  58.071  19.531  58.179  27.257  50.397
  27.605  28.658  32.395  27.454  41.591  25.774  47.828   26.02  59.954  25.443
  66.768  25.961  72.454  25.748  77.894  27.559  78.776  28.264  88.061   28.34
  90.965  58.376   91.43   58.35  107.94  57.349 123.671  57.379
#Mann= 3 , 0 , 0
       0    .035       0       0    .035       0 123.671    .035       0
Bank Sta=0,123.671
XS Rating Curve= 0
Exp/Cntr=.3,.1

Type RM Length L Ch R = 3 ,360.1   ,,,
BEGIN DESCRIPTION:
FFSS Lu-Viareggio
END DESCRIPTION:
Bridge Culvert--1,0,-1,-1, 0
Deck Dist Width WeirC Skew NumUp NumDn MinLoCord MaxHiCord MaxSubmerge Is_Ogee
1.64,22.966,2.61,0, 6, 6, , , .95, 0, 0,0,,
  19.521  19.521  27.264  88.058   90.19  91.273
  61.483  61.483  61.483  61.483  61.483  61.483
  61.483  58.169  50.427  50.427  50.427  61.483
  19.521  19.521  27.264  88.058   90.19  91.273
  61.483  61.483  61.483  61.483  61.483  61.483
  61.483  58.169  50.427  50.427  50.427  61.483
BR Coef=-1 , 0 , 0 ,1.25, 0 ,,,.8,-1,2,0,
WSPro=,,,, 1 ,,,, 0 ,,,, 0 ,,,,-1 ,-1 ,-1 , 0 , 0 , 0 , 0 , 0
BC Design=,, 0 ,, 0 ,,,,,,
BC HTab Sub Flow Pts= 40

Type RM Length L Ch R = 1 ,360     ,368.34,368.34,368.34
XS GIS Cut Line= 2
      5296321.56     15925201.21       5296199.7     15925212.63
#Sta/Elev= 19
       0  56.795  11.972  57.149  17.657  58.071  19.531  58.179  27.257  50.397
  27.605  28.658  32.395  27.454  41.591  25.774  47.828   26.02  59.954  25.443
  66.768  25.961  72.454  25.748  77.894  27.559  78.776  28.264  88.061   28.34
  90.965  58.376   91.43   58.35  107.94  57.349 123.671  57.379
#Mann= 3 , 0 , 0
       0    .035       0       0    .035       0 123.671    .035       0
Bank Sta=0,123.671
XS Rating Curve= 0
Exp/Cntr=.3,.1

Type RM Length L Ch R = 1 ,359.2   ,26.247,26.247,26.247
XS GIS Cut Line= 3
       5296060.3     15924886.52      5295913.19      15925039.3
      5295913.19      15925039.3
#Sta/Elev= 24
       0  49.491  21.719  49.052  28.061  48.268  32.411   48.95  60.686  48.264
  65.243  48.668  65.548  44.298  66.844  44.301  67.149  27.421  80.928  26.073
  87.382  25.886  93.825  25.853 100.069  26.161 103.593    26.9 110.033   26.68
  111.26  44.364 112.546  44.354  112.71  48.602 119.862   48.73 139.049  47.917
 156.145  47.421 169.131  41.378 191.112  41.198 212.467  41.096
#Mann= 3 , 0 , 0
       0    .035       0       0    .035       0 212.467    .035       0
Bank Sta=0,212.467
XS Rating Curve= 0
Exp/Cntr=.3,.1

Type RM Length L Ch R = 3 ,359.1   ,,,
BEGIN DESCRIPTION:
ponte dismesso
END DESCRIPTION:
Bridge Culvert--1,0,-1,-1, 0
Deck Dist Width WeirC Skew NumUp NumDn MinLoCord MaxHiCord MaxSubmerge Is_Ogee
1.64,22.966,2.61,0, 6, 6, , , .95, 0, 0,0,,
  65.256  65.551  66.831 111.253 112.533 112.697
  48.655  48.655  48.655  48.655  48.655  48.589
  48.655  44.291  44.291  44.291  44.357  48.589
  65.256  65.551  66.831 111.253 112.533 112.697
  48.655  48.655  48.655  48.655  48.655  48.589
  48.655  44.291  44.291  44.291  44.357  48.589
BR Coef=-1 , 0 , 0 ,1.25, 0 ,,,.8,-1,2,0,
WSPro=,,,, 1 ,,,, 0 ,,,, 0 ,,,,-1 ,-1 ,-1 , 0 , 0 , 0 , 0 , 0
BC Design=,, 0 ,, 0 ,,,,,,
BC HTab Sub Flow Pts= 40

Type RM Length L Ch R = 1 ,359     ,370.735,370.735,370.735
XS GIS Cut Line= 3
       5296060.3     15924886.52      5295913.19      15925039.3
      5295913.19      15925039.3
#Sta/Elev= 24
       0  49.491  21.719  49.052  28.061  48.268  32.411   48.95  60.686  48.264
  65.243  48.668  65.548  44.298  66.844  44.301  67.149  27.421  80.928  26.073
  87.382  25.886  93.825  25.853 100.069  26.161 103.593    26.9 110.033   26.68
  111.26  44.364 112.546  44.354  112.71  48.602 119.862   48.73 139.049  47.917
 156.145  47.421 169.131  41.378 191.112  41.198 212.467  41.096
#Mann= 3 , 0 , 0
       0    .035       0       0    .035       0 212.467    .035       0
Bank Sta=0,212.467
XS Rating Curve= 0
Exp/Cntr=.3,.1

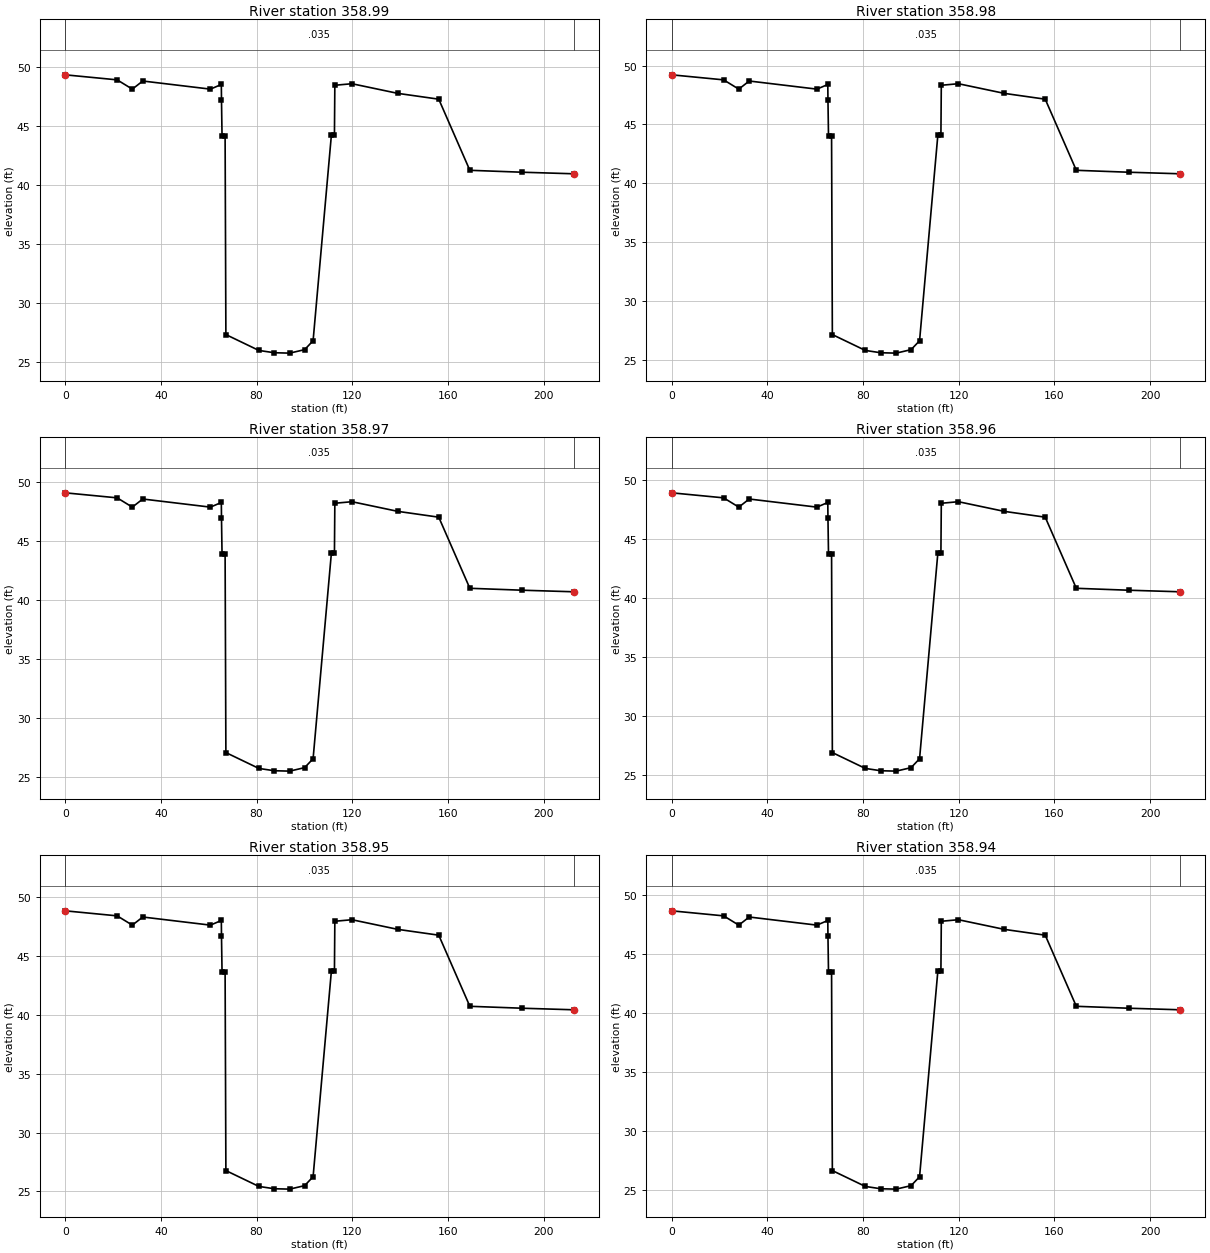
Type RM Length L Ch R = 1 ,358.99  ,370.735,370.735,370.735
BEGIN DESCRIPTION:
come 359 con z=z-0.04
END DESCRIPTION:
#Sta/Elev= 24
       0  49.344  21.719  48.917  28.051   48.13  32.415  48.819  60.696   48.13
  65.256  48.524  65.322  47.211  65.551   44.16  66.831   44.16  67.159  27.297
  80.938  25.951  87.369  25.755  93.832  25.722 100.066  26.017 103.609  26.772
 111.253  44.226 112.533  44.226 112.697  48.458 119.849  48.589 139.042  47.769
 156.135  47.277 169.127   41.24 191.109  41.076 212.467  40.945
#Mann= 3 , 0 , 0
       0    .035       0       0    .035       0 212.467    .035       0
Bank Sta=0,212.467
XS Rating Curve= 0
Exp/Cntr=.3,.1

Type RM Length L Ch R = 1 ,358.98  ,370.735,370.735,370.735
BEGIN DESCRIPTION:
come 358.99 con z=z-0.04
END DESCRIPTION:
#Sta/Elev= 24
       0  49.213  21.719  48.786  28.051  47.999  32.415  48.688  60.696  47.999
  65.256  48.392  65.322   47.08  65.551  44.029  66.831  44.029  67.159  27.165
  80.938   25.82  87.369  25.623  93.832  25.591 100.066  25.886 103.609   26.64
 111.253  44.094 112.533  44.094 112.697  48.327 119.849  48.458 139.042  47.638
 156.135  47.146 169.127  41.109 191.109  40.945 212.467  40.814
#Mann= 3 , 0 , 0
       0    .035       0       0    .035       0 212.467    .035       0
Bank Sta=0,212.467
XS Rating Curve= 0
Exp/Cntr=.3,.1

Type RM Length L Ch R = 1 ,358.97  ,370.735,370.735,370.735
BEGIN DESCRIPTION:
come 358.98 con z=z-0.04
END DESCRIPTION:
#Sta/Elev= 24
       0  49.081  21.719  48.655  28.051  47.867  32.415  48.556  60.696  47.867
  65.256  48.261  65.322  46.949  65.551  43.898  66.831  43.898  67.159  27.034
  80.938  25.689  87.369  25.492  93.832  25.459 100.066  25.755 103.609  26.509
 111.253  43.963 112.533  43.963 112.697  48.196 119.849  48.327 139.042  47.507
 156.135  47.014 169.127  40.978 191.109  40.814 212.467  40.682
#Mann= 3 , 0 , 0
       0    .035       0       0    .035       0 212.467    .035       0
Bank Sta=0,212.467
XS Rating Curve= 0
Exp/Cntr=.3,.1

Type RM Length L Ch R = 1 ,358.96  ,370.735,370.735,370.735
BEGIN DESCRIPTION:
come 358.97 con z=z-0.04
END DESCRIPTION:
#Sta/Elev= 24
       0   48.95  21.719  48.524  28.051  47.736  32.415  48.425  60.696  47.736
  65.256   48.13  65.322  46.818  65.551  43.766  66.831  43.766  67.159  26.903
  80.938  25.558  87.369  25.361  93.832  25.328 100.066  25.623 103.609  26.378
 111.253  43.832 112.533  43.832 112.697  48.064 119.849  48.196 139.042  47.375
 156.135  46.883 169.127  40.846 191.109  40.682 212.467  40.551
#Mann= 3 , 0 , 0
       0    .035       0       0    .035       0 212.467    .035       0
Bank Sta=0,212.467
XS Rating Curve= 0
Exp/Cntr=.3,.1

Type RM Length L Ch R = 1 ,358.95  ,370.735,370.735,370.735
BEGIN DESCRIPTION:
come 358.96 con z=z-0.02
END DESCRIPTION:
#Sta/Elev= 24
       0  48.819  21.719  48.392  28.051  47.605  32.415  48.294  60.696  47.605
  65.256  47.999  65.322  46.686  65.551  43.635  66.831  43.635  67.159  26.772
  80.938  25.427  87.369   25.23  93.832  25.197 100.066  25.492 103.609  26.247
 111.253  43.701 112.533  43.701 112.697  47.933 119.849  48.064 139.042  47.244
 156.135  46.752 169.127  40.715 191.109  40.551 212.467   40.42
#Mann= 3 , 0 , 0
       0    .035       0       0    .035       0 212.467    .035       0
Bank Sta=0,212.467
XS Rating Curve= 0
Exp/Cntr=.3,.1

Type RM Length L Ch R = 1 ,358.94  ,370.735,370.735,370.735
BEGIN DESCRIPTION:
come 358.95 con z=z-0.02
END DESCRIPTION:
#Sta/Elev= 24
       0  48.688  21.719  48.261  28.051  47.474  32.415  48.163  60.696  47.474
  65.256  47.867  65.322  46.555  65.551  43.504  66.831  43.504  67.159   26.64
  80.938  25.295  87.369  25.098  93.832  25.066 100.066  25.361 103.609  26.115
 111.253   43.57 112.533   43.57 112.697  47.802 119.849  47.933 139.042  47.113
 156.135  46.621 169.127  40.584 191.109   40.42 212.467  40.289
#Mann= 3 , 0 , 0
       0    .035       0       0    .035       0 212.467    .035       0
Bank Sta=0,212.467
XS Rating Curve= 0
Exp/Cntr=.3,.1

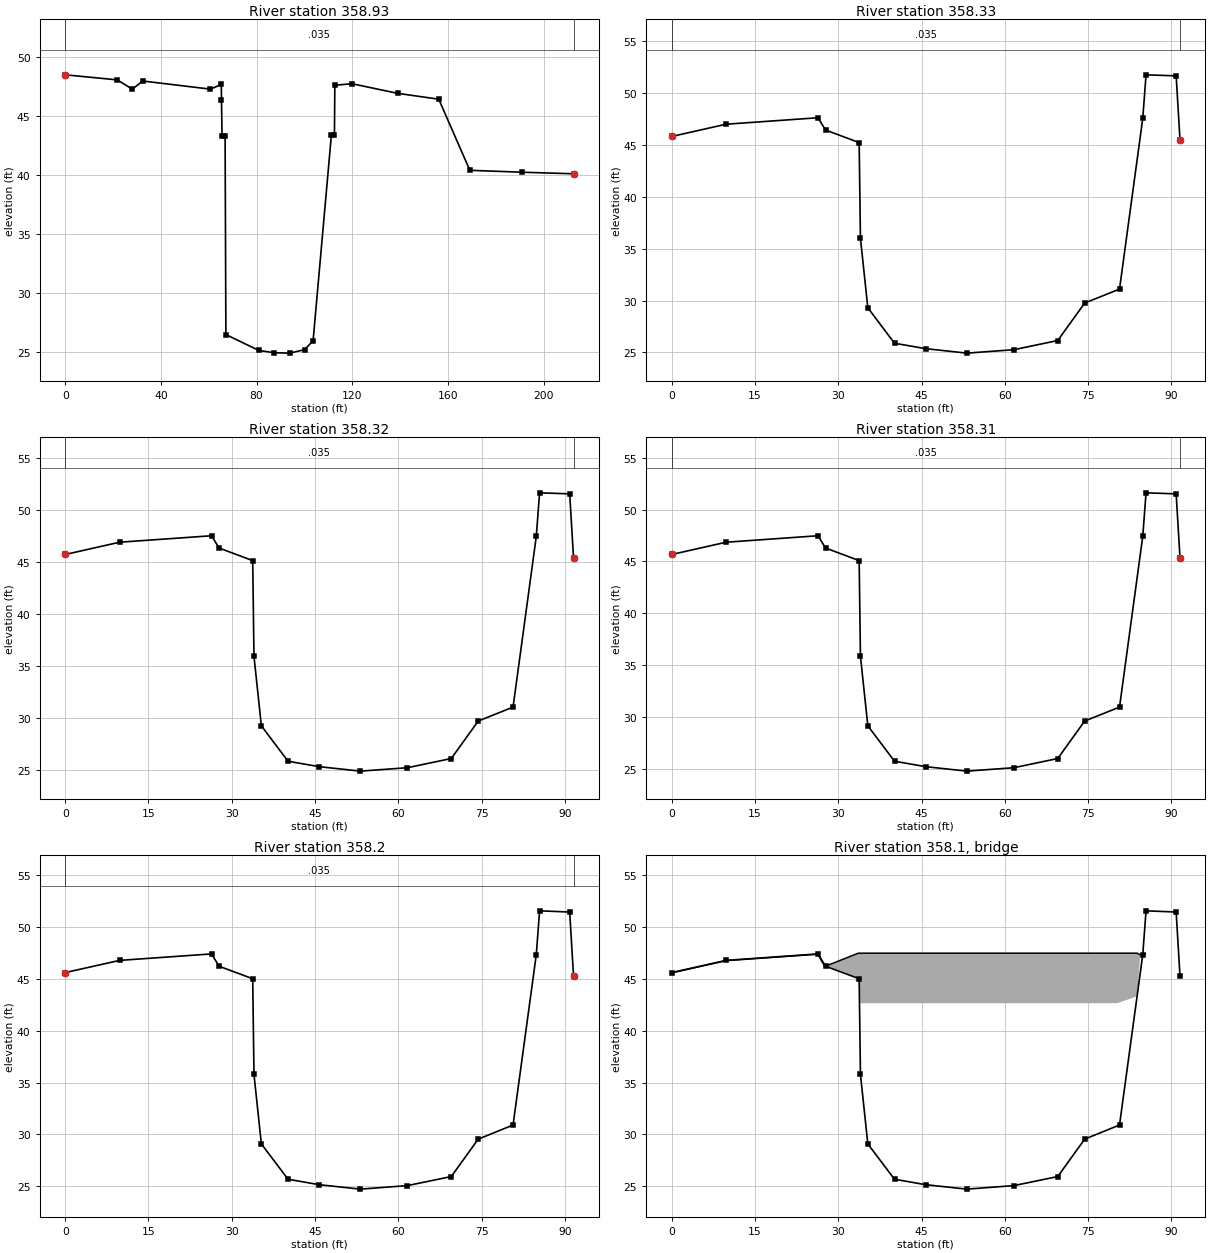
Type RM Length L Ch R = 1 ,358.93  ,370.735,370.735,370.735
BEGIN DESCRIPTION:
come 358.94 con z=z-0.02
END DESCRIPTION:
#Sta/Elev= 24
       0  48.491  21.719  48.064  28.051  47.277  32.415  47.966  60.696  47.277
  65.256  47.671  65.322  46.358  65.551  43.307  66.831  43.307  67.159  26.444
  80.938  25.098  87.369  24.902  93.832  24.869 100.066  25.164 103.609  25.919
 111.253  43.373 112.533  43.373 112.697  47.605 119.849  47.736 139.042  46.916
 156.135  46.424 169.127  40.387 191.109  40.223 212.467  40.092
#Mann= 3 , 0 , 0
       0    .035       0       0    .035       0 212.467    .035       0
Bank Sta=0,212.467
XS Rating Curve= 0
Exp/Cntr=.3,.1

Type RM Length L Ch R = 1 ,358.33  ,370.735,370.735,370.735
#Sta/Elev= 18
       0  45.801   9.803  46.982  26.358  47.605   27.71  46.424   33.77   45.21
  33.999  35.991  35.331  29.298  40.135  25.886  45.791  25.361  53.159  24.934
  61.624  25.262  69.534  26.148  74.386  29.757  80.663  31.102  84.846  47.539
   85.44  51.739  90.863   51.64  91.555  45.472
#Mann= 3 , 0 , 0
       0    .035       0       0    .035       0  91.555    .035       0
Bank Sta=0,91.555
XS Rating Curve= 0
Exp/Cntr=.3,.1

Type RM Length L Ch R = 1 ,358.32  ,370.735,370.735,370.735
#Sta/Elev= 18
       0  45.735   9.803  46.916  26.358  47.539   27.71  46.358   33.77  45.144
  33.999  35.925  35.331  29.232  40.135   25.82  45.791  25.295  53.159  24.869
  61.624  25.197  69.534  26.083  74.386  29.692  80.663  31.037  84.846  47.474
   85.44  51.673  90.863  51.575  91.555  45.407
#Mann= 3 , 0 , 0
       0    .035       0       0    .035       0  91.555    .035       0
Bank Sta=0,91.555
XS Rating Curve= 0
Exp/Cntr=.3,.1

Type RM Length L Ch R = 1 ,358.31  ,370.735,370.735,370.735
#Sta/Elev= 18
       0  45.669   9.803   46.85  26.358  47.474   27.71  46.293   33.77  45.079
  33.999   35.86  35.331  29.167  40.135  25.755  45.791   25.23  53.159  24.803
  61.624  25.131  69.534  26.017  74.386  29.626  80.663  30.971  84.846  47.408
   85.44  51.608  90.863  51.509  91.555  45.341
#Mann= 3 , 0 , 0
       0    .035       0       0    .035       0  91.555    .035       0
Bank Sta=0,91.555
XS Rating Curve= 0
Exp/Cntr=.3,.1

Type RM Length L Ch R = 1 ,358.2   ,26.247,26.247,26.247
XS GIS Cut Line= 2
      5294615.16     15921156.53      5294527.62       15921179.
#Sta/Elev= 18
       0  45.604   9.803  46.778  26.358  47.402   27.71  46.214   33.77   45.01
  33.999  35.784  35.331  29.088  40.135  25.686  45.791  25.157  53.159  24.734
  61.624  25.072  69.534  25.945  74.386  29.551  80.663  30.912  84.846  47.329
   85.44  51.555  90.863   51.44  91.555  45.262
#Mann= 3 , 0 , 0
       0    .035       0       0    .035       0  91.555    .035       0
Bank Sta=0,91.555
XS Rating Curve= 0
Exp/Cntr=.3,.1

Type RM Length L Ch R = 3 ,358.1   ,,,
BEGIN DESCRIPTION:
Ponte di Ripafratta
END DESCRIPTION:
Bridge Culvert--1,0,-1,-1, 0
Deck Dist Width WeirC Skew NumUp NumDn MinLoCord MaxHiCord MaxSubmerge Is_Ogee
1.64,22.966,2.61,0, 17, 17, , , .95, 0, 0,0,,
       0   9.777  26.312  27.592  33.629   33.76  35.007  39.797  45.407  52.789
  61.253   69.16  73.983  80.249  83.825  84.416  85.302
  45.571  46.752  47.375  46.194  47.474  47.474  47.474  47.474  47.474  47.474
  47.474  47.474  47.474  47.474  47.474   47.31  47.408
  45.571  46.752  47.375  46.194  42.651  42.651  42.651  42.651  42.651  42.651
  42.651  42.651  42.651  42.651  43.307   47.31  47.408
       0   9.777  26.312  27.592  33.629   33.76  35.007  39.797  45.407  52.789
  61.253   69.16  73.983  80.249  83.825  84.416  85.302
  45.571  46.752  47.375  46.194  47.474  47.474  47.474  47.474  47.474  47.474
  47.474  47.474  47.474  47.474  47.474   47.31  47.408
  45.571  46.752  47.375  46.194  42.651  42.651  42.651  42.651  42.651  42.651
  42.651  42.651  42.651  42.651  43.307   47.31  47.408
BR Coef=-1 , 0 , 0 ,1.25, 0 ,,,.8,-1,2,0,
WSPro=,,,, 1 ,,,, 0 ,,,, 0 ,,,,-1 ,-1 ,-1 , 0 , 0 , 0 , 0 , 0
BC Design=,, 0 ,, 0 ,,,,,,
BC HTab Sub Flow Pts= 40