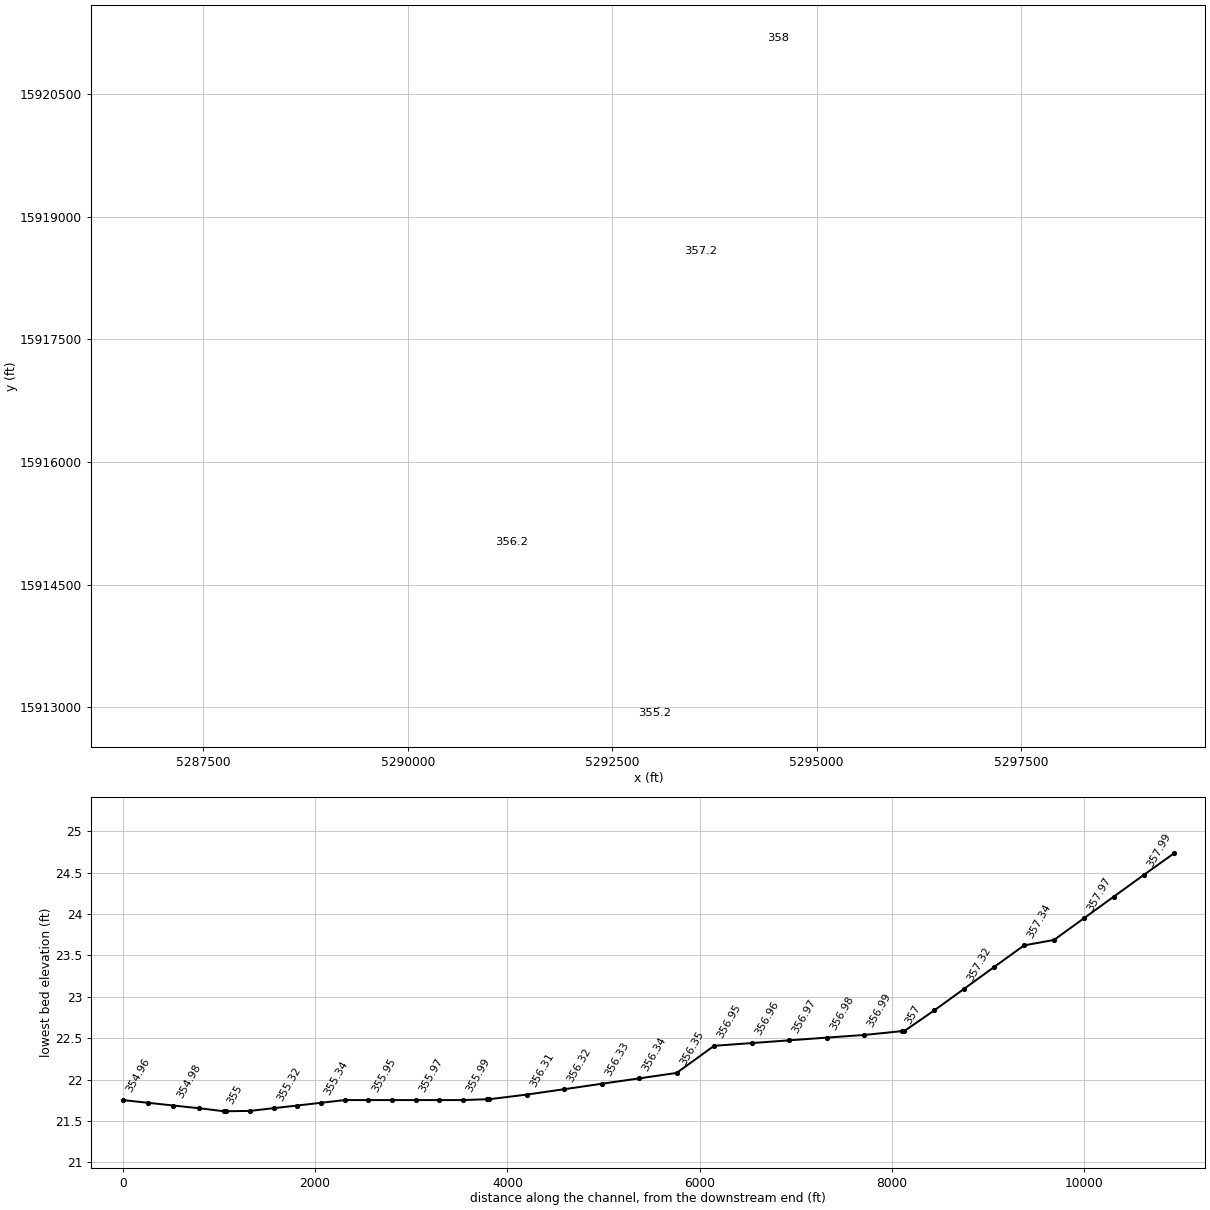
HEC-RAS study ozz_def.prj: ozzeri

--- ozz_def.g04 (geometry) --- (continued)

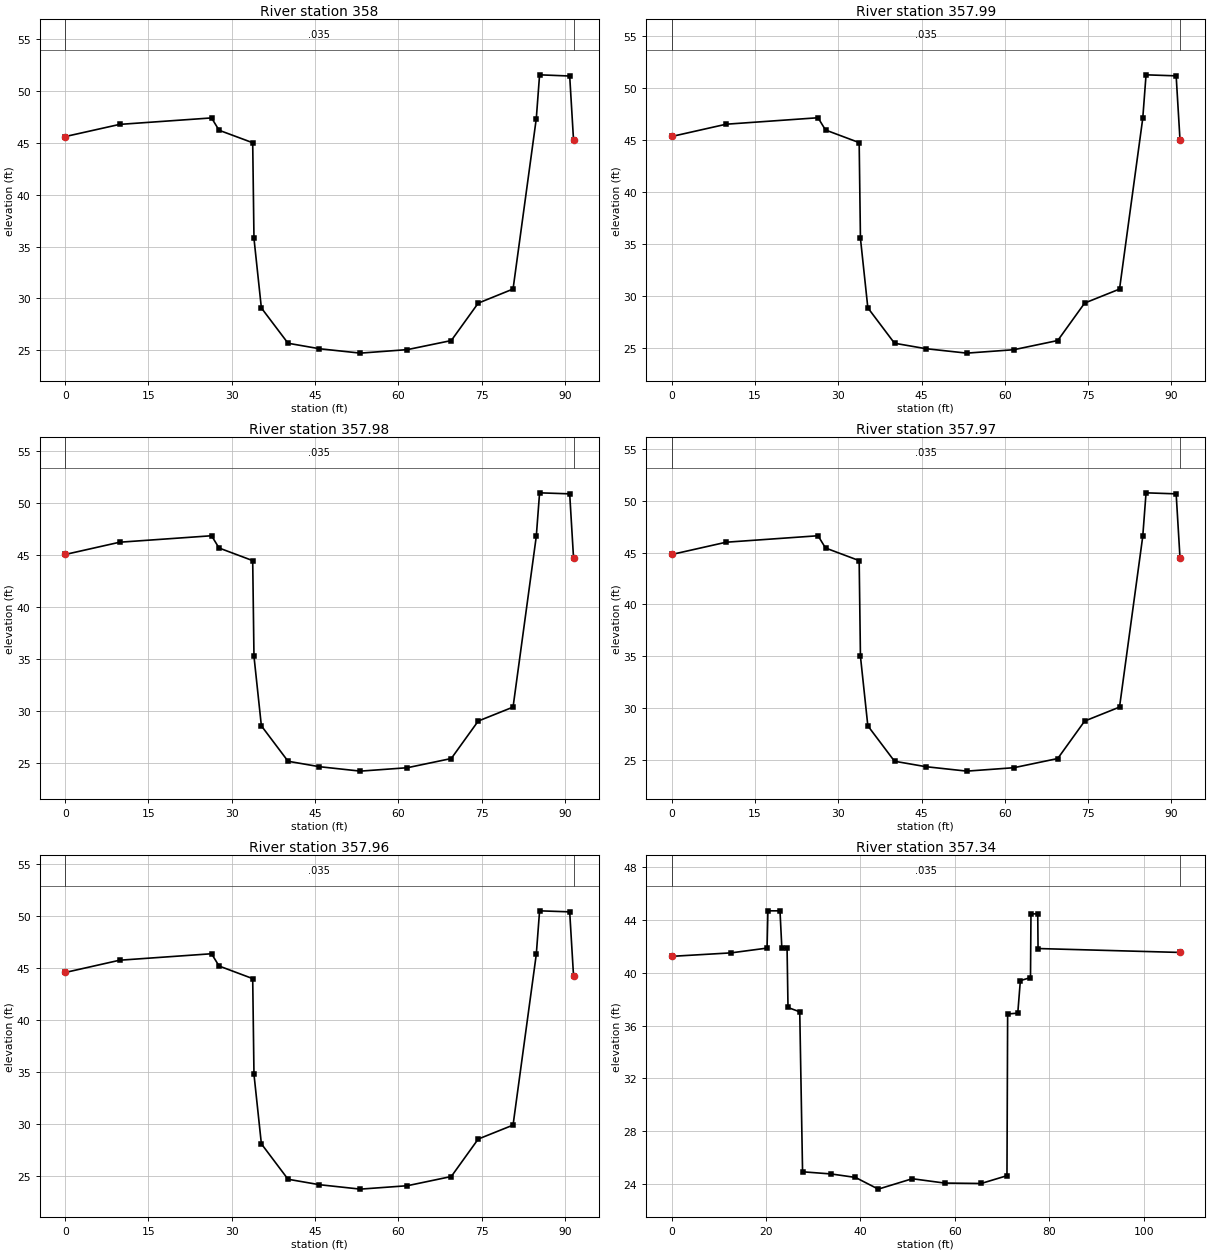
Type RM Length L Ch R = 1 ,358     ,311.68,311.68,311.68
XS GIS Cut Line= 2
      5294615.16     15921156.53      5294527.62       15921179.
#Sta/Elev= 18
       0  45.604   9.803  46.778  26.358  47.402   27.71  46.214   33.77   45.01
  33.999  35.784  35.331  29.088  40.135  25.686  45.791  25.157  53.159  24.734
  61.624  25.072  69.534  25.945  74.386  29.551  80.663  30.912  84.846  47.329
   85.44  51.555  90.863   51.44  91.555  45.262
#Mann= 3 , 0 , 0
       0    .035       0       0    .035       0  91.555    .035       0
Bank Sta=0,91.555
XS Rating Curve= 0
Exp/Cntr=.3,.1

Type RM Length L Ch R = 1 ,357.99  ,311.68,311.68,311.68
#Sta/Elev= 18
       0  45.341   9.803  46.522  26.358  47.146   27.71  45.965   33.77  44.751
  33.999  35.531  35.331  28.839  40.135  25.427  45.791  24.902  53.159  24.475
  61.624  24.803  69.534  25.689  74.386  29.298  80.663  30.643  84.846   47.08
   85.44   51.28  90.863  51.181  91.555  45.013
#Mann= 3 , 0 , 0
       0    .035       0       0    .035       0  91.555    .035       0
Bank Sta=0,91.555
XS Rating Curve= 0
Exp/Cntr=.3,.1

Type RM Length L Ch R = 1 ,357.98  ,311.68,311.68,311.68
#Sta/Elev= 18
       0  45.079   9.803   46.26  26.358  46.883   27.71  45.702   33.77  44.488
  33.999  35.269  35.331  28.576  40.135  25.164  45.791  24.639  53.159  24.213
  61.624  24.541  69.534  25.427  74.386  29.035  80.663  30.381  84.846  46.818
   85.44  51.017  90.863  50.919  91.555  44.751
#Mann= 3 , 0 , 0
       0    .035       0       0    .035       0  91.555    .035       0
Bank Sta=0,91.555
XS Rating Curve= 0
Exp/Cntr=.3,.1

Type RM Length L Ch R = 1 ,357.97  ,311.68,311.68,311.68
#Sta/Elev= 18
       0  44.816   9.803  45.997  26.358  46.621   27.71   45.44   33.77  44.226
  33.999  35.007  35.331  28.314  40.135  24.902  45.791  24.377  53.159   23.95
  61.624  24.278  69.534  25.164  74.386  28.773  80.663  30.118  84.846  46.555
   85.44  50.755  90.863  50.656  91.555  44.488
#Mann= 3 , 0 , 0
       0    .035       0       0    .035       0  91.555    .035       0
Bank Sta=0,91.555
XS Rating Curve= 0
Exp/Cntr=.3,.1

Type RM Length L Ch R = 1 ,357.96  ,311.68,311.68,311.68
#Sta/Elev= 18
       0  44.554   9.803  45.735  26.358  46.358   27.71  45.177   33.77  43.963
  33.999  34.744  35.331  28.051  40.135  24.639  45.791  24.114  53.159  23.688
  61.624  24.016  69.534  24.902  74.386   28.51  80.663  29.856  84.846  46.293
   85.44  50.492  90.863  50.394  91.555  44.226
#Mann= 3 , 0 , 0
       0    .035       0       0    .035       0  91.555    .035       0
Bank Sta=0,91.555
XS Rating Curve= 0
Exp/Cntr=.3,.1

Type RM Length L Ch R = 1 ,357.34  ,311.68,311.68,311.68
#Sta/Elev= 25
       0   41.24  12.579  41.503   20.21  41.864  20.394  44.685  22.953  44.685
  23.346  41.864  24.452  41.864  24.652  37.369  27.139  37.041  27.736  24.934
  33.796   24.77   38.94  24.508   43.78  23.622  50.981  24.409  57.828  24.081
  65.581  24.049   71.05  24.639  71.194  36.877   73.34  36.942  73.888  39.403
  76.037  39.633  76.138  44.455  77.572  44.455  77.638  41.831 107.717  41.535
#Mann= 3 , 0 , 0
       0    .035       0       0    .035       0 107.717    .035       0
Bank Sta=0,107.717
XS Rating Curve= 0
Exp/Cntr=.3,.1

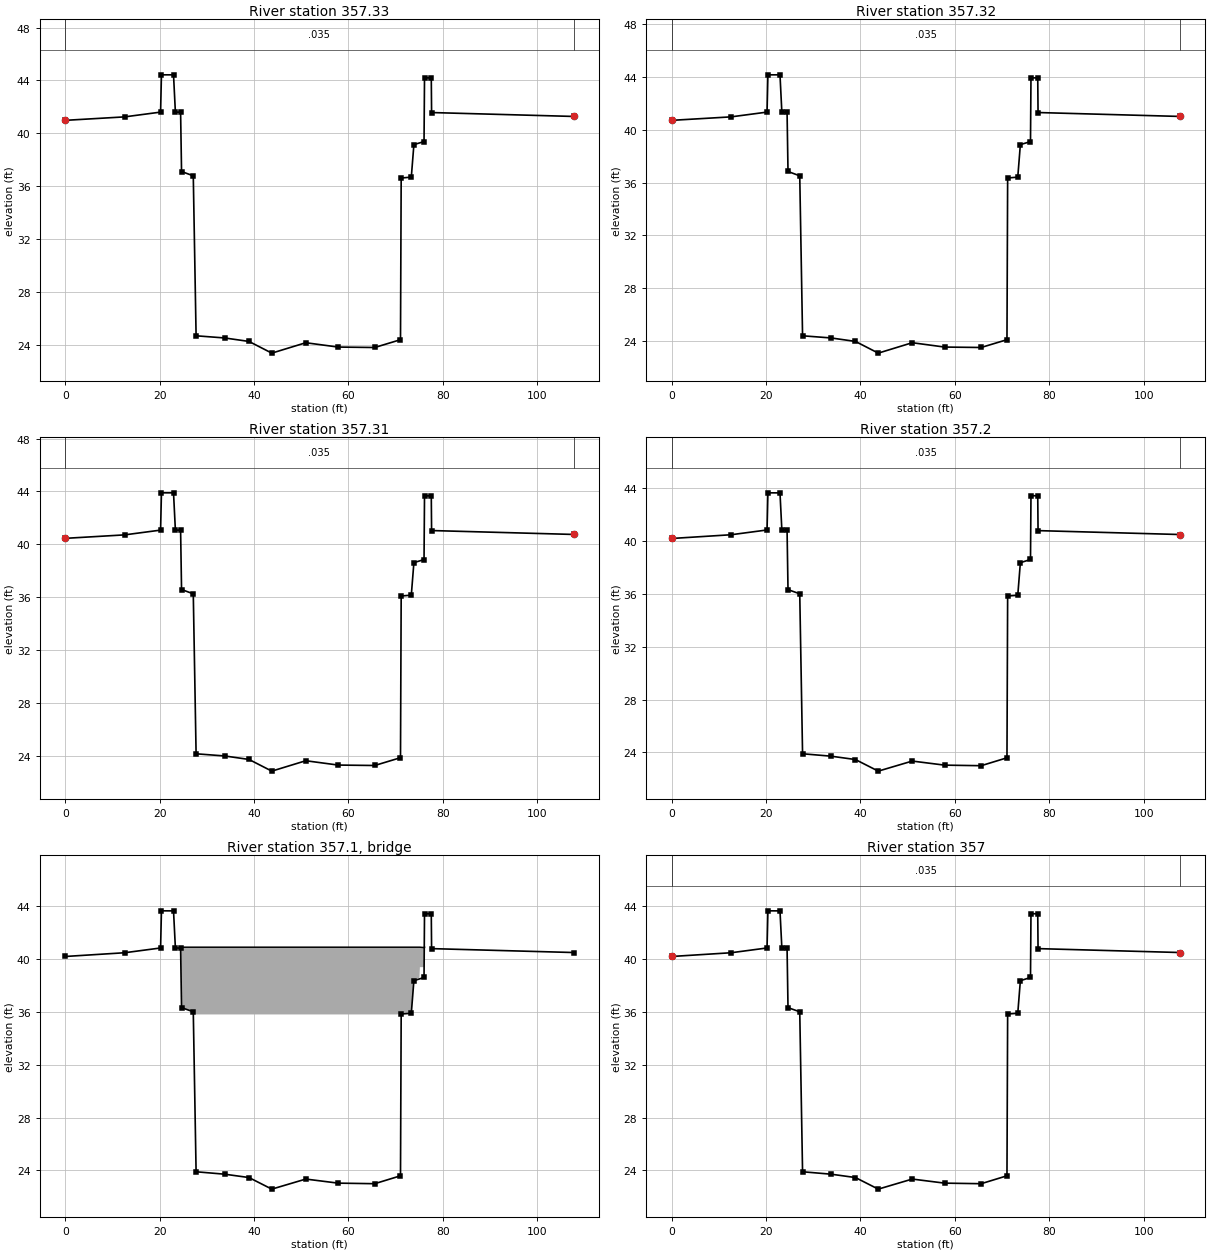
Type RM Length L Ch R = 1 ,357.33  ,311.68,311.68,311.68
#Sta/Elev= 25
       0  40.978  12.579   41.24   20.21  41.601  20.394  44.423  22.953  44.423
  23.346  41.601  24.452  41.601  24.652  37.106  27.139  36.778  27.736  24.672
  33.796  24.508   38.94  24.245   43.78   23.36  50.981  24.147  57.828  23.819
  65.581  23.786   71.05  24.377  71.194  36.614   73.34   36.68  73.888   39.14
  76.037   39.37  76.138  44.193  77.572  44.193  77.638  41.568 107.717  41.273
#Mann= 3 , 0 , 0
       0    .035       0       0    .035       0 107.717    .035       0
Bank Sta=0,107.717
XS Rating Curve= 0
Exp/Cntr=.3,.1

Type RM Length L Ch R = 1 ,357.32  ,311.68,311.68,311.68
#Sta/Elev= 25
       0  40.715  12.579  40.978   20.21  41.339  20.394   44.16  22.953   44.16
  23.346  41.339  24.452  41.339  24.652  36.844  27.139  36.516  27.736  24.409
  33.796  24.245   38.94  23.983   43.78  23.097  50.981  23.885  57.828  23.556
  65.581  23.524   71.05  24.114  71.194  36.352   73.34  36.417  73.888  38.878
  76.037  39.108  76.138   43.93  77.572   43.93  77.638  41.306 107.717   41.01
#Mann= 3 , 0 , 0
       0    .035       0       0    .035       0 107.717    .035       0
Bank Sta=0,107.717
XS Rating Curve= 0
Exp/Cntr=.3,.1

Type RM Length L Ch R = 1 ,357.31  ,311.68,311.68,311.68
#Sta/Elev= 25
       0  40.453  12.579  40.715   20.21  41.076  20.394  43.898  22.953  43.898
  23.346  41.076  24.452  41.076  24.652  36.581  27.139  36.253  27.736  24.147
  33.796  23.983   38.94   23.72   43.78  22.835  50.981  23.622  57.828  23.294
  65.581  23.261   71.05  23.852  71.194  36.089   73.34  36.155  73.888  38.615
  76.037  38.845  76.138  43.668  77.572  43.668  77.638  41.043 107.717  40.748
#Mann= 3 , 0 , 0
       0    .035       0       0    .035       0 107.717    .035       0
Bank Sta=0,107.717
XS Rating Curve= 0
Exp/Cntr=.3,.1

Type RM Length L Ch R = 1 ,357.2   ,26.247,26.247,26.247
XS GIS Cut Line= 3
      5293678.02     15918529.33      5293581.76      15918575.3
      5293581.76      15918575.3
#Sta/Elev= 25
       0  40.177  12.579  40.459   20.21   40.82  20.394  43.629  22.953  43.625
  23.346  40.827  24.452  40.807  24.652  36.309  27.139  35.994  27.736  23.898
  33.796  23.714   38.94  23.461   43.78  22.585  50.981  23.346  57.828  23.038
  65.581  22.995   71.05  23.593  71.194  35.827   73.34  35.883  73.888  38.346
  76.037  38.589  76.138  43.415  77.572  43.402  77.638  40.771 107.717  40.476
#Mann= 3 , 0 , 0
       0    .035       0       0    .035       0 107.717    .035       0
Bank Sta=0,107.717
XS Rating Curve= 0
Exp/Cntr=.3,.1

Type RM Length L Ch R = 3 ,357.1   ,,,
BEGIN DESCRIPTION:
Ponte di Villa Sassine
END DESCRIPTION:
Bridge Culvert--1,0,-1,-1, 0
Deck Dist Width WeirC Skew NumUp NumDn MinLoCord MaxHiCord MaxSubmerge Is_Ogee
1.64,22.966,2.61,0, 18, 18, , , .95, 0, 0,0,,
  24.442  24.442  26.411  26.903  32.972  38.123  42.946  50.131  56.988  64.731
  70.144  70.276  72.408  73.622  75.066  75.164  76.148  76.148
  40.879  40.879  40.879  40.879  40.879  40.879  40.879  40.879  40.879  40.879
  40.879  40.879  40.879  40.879  40.879  40.879  40.846  40.879
  36.286  35.991  35.991  35.794  35.794  35.794  35.794  35.794  35.794  35.794
  35.794  35.794   35.86  35.696  38.583   39.37   39.37  40.879
  24.442  24.442  26.411  26.903  32.972  38.123  42.946  50.131  56.988  64.731
  70.144  70.276  72.408  73.622  75.066  75.164  76.148  76.148
  40.879  40.879  40.879  40.879  40.879  40.879  40.879  40.879  40.879  40.879
  40.879  40.879  40.879  40.879  40.879  40.879  40.846  40.879
  36.286  35.991  35.991  35.794  35.794  35.794  35.794  35.794  35.794  35.794
  35.794  35.794   35.86  35.696  38.583   39.37   39.37  40.879
BR Coef=-1 , 0 , 0 ,1.25, 0 ,,,.8,-1,2,0,
WSPro=,,,, 1 ,,,, 0 ,,,, 0 ,,,,-1 ,-1 ,-1 , 0 , 0 , 0 , 0 , 0
BC Design=,, 0 ,, 0 ,,,,,,
BC HTab Sub Flow Pts= 40

Type RM Length L Ch R = 1 ,357     ,390.092,390.092,390.092
XS GIS Cut Line= 3
      5293678.02     15918529.33      5293581.76      15918575.3
      5293581.76      15918575.3
#Sta/Elev= 25
       0  40.177  12.579  40.459   20.21   40.82  20.394  43.629  22.953  43.625
  23.346  40.827  24.452  40.807  24.652  36.309  27.139  35.994  27.736  23.898
  33.796  23.714   38.94  23.461   43.78  22.585  50.981  23.346  57.828  23.038
  65.581  22.995   71.05  23.593  71.194  35.827   73.34  35.883  73.888  38.346
  76.037  38.589  76.138  43.415  77.572  43.402  77.638  40.771 107.717  40.476
#Mann= 3 , 0 , 0
       0    .035       0       0    .035       0 107.717    .035       0
Bank Sta=0,107.717
XS Rating Curve= 0
Exp/Cntr=.3,.1

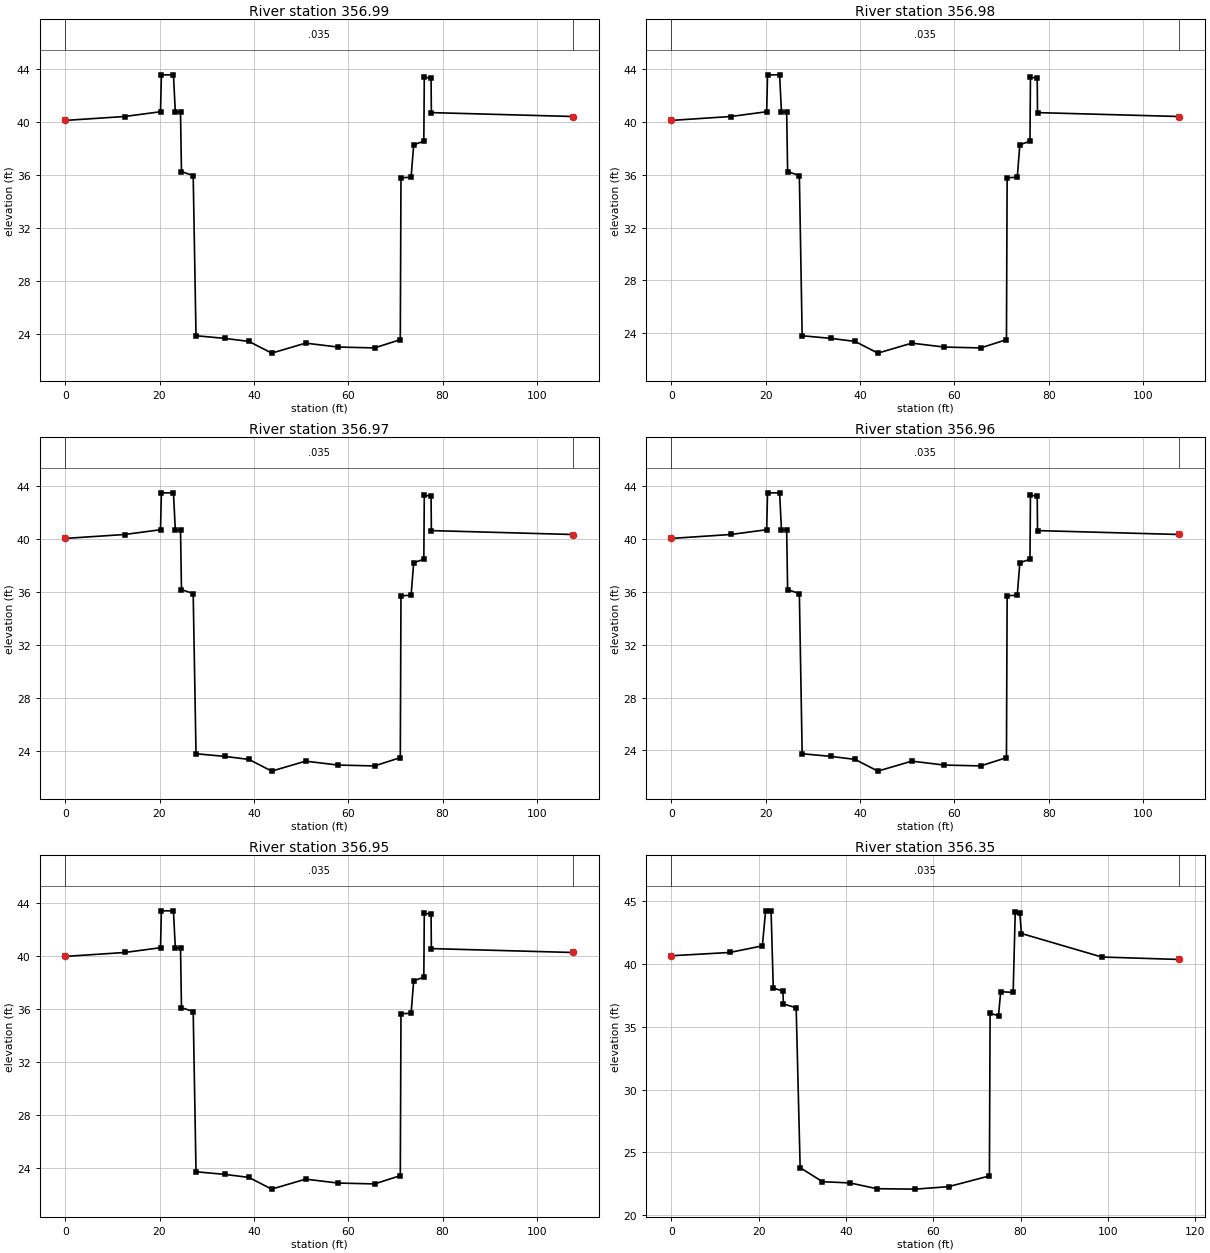
Type RM Length L Ch R = 1 ,356.99  ,390.092,390.092,390.092
#Sta/Elev= 25
       0  40.125  12.579   40.42   20.21  40.781  20.394   43.57  22.953   43.57
  23.346  40.781  24.452  40.748  24.652  36.253  27.139  35.958  27.736  23.852
  33.796  23.655   38.94  23.425   43.78  22.539  50.981  23.294  57.828  22.999
  65.581  22.933   71.05  23.556  71.194  35.794   73.34  35.827  73.888  38.287
  76.037   38.55  76.138  43.373  77.572   43.34  77.638  40.715 107.717   40.42
#Mann= 3 , 0 , 0
       0    .035       0       0    .035       0 107.717    .035       0
Bank Sta=0,107.717
XS Rating Curve= 0
Exp/Cntr=.3,.1

Type RM Length L Ch R = 1 ,356.98  ,390.092,390.092,390.092
#Sta/Elev= 25
       0  40.092  12.579  40.387   20.21  40.748  20.394  43.537  22.953  43.537
  23.346  40.748  24.452  40.715  24.652   36.22  27.139  35.925  27.736  23.819
  33.796  23.622   38.94  23.392   43.78  22.507  50.981  23.261  57.828  22.966
  65.581    22.9   71.05  23.524  71.194  35.761   73.34  35.794  73.888  38.255
  76.037  38.517  76.138   43.34  77.572  43.307  77.638  40.682 107.717  40.387
#Mann= 3 , 0 , 0
       0    .035       0       0    .035       0 107.717    .035       0
Bank Sta=0,107.717
XS Rating Curve= 0
Exp/Cntr=.3,.1

Type RM Length L Ch R = 1 ,356.97  ,390.092,390.092,390.092
#Sta/Elev= 25
       0  40.059  12.579  40.354   20.21  40.715  20.394  43.504  22.953  43.504
  23.346  40.715  24.452  40.682  24.652  36.188  27.139  35.892  27.736  23.786
  33.796  23.589   38.94   23.36   43.78  22.474  50.981  23.228  57.828  22.933
  65.581  22.867   71.05  23.491  71.194  35.728   73.34  35.761  73.888  38.222
  76.037  38.484  76.138  43.307  77.572  43.274  77.638   40.65 107.717  40.354
#Mann= 3 , 0 , 0
       0    .035       0       0    .035       0 107.717    .035       0
Bank Sta=0,107.717
XS Rating Curve= 0
Exp/Cntr=.3,.1

Type RM Length L Ch R = 1 ,356.96  ,390.092,390.092,390.092
#Sta/Elev= 25
       0  40.026  12.579  40.322   20.21  40.682  20.394  43.471  22.953  43.471
  23.346  40.682  24.452   40.65  24.652  36.155  27.139   35.86  27.736  23.753
  33.796  23.556   38.94  23.327   43.78  22.441  50.981  23.196  57.828    22.9
  65.581  22.835   71.05  23.458  71.194  35.696   73.34  35.728  73.888  38.189
  76.037  38.451  76.138  43.274  77.572  43.241  77.638  40.617 107.717  40.322
#Mann= 3 , 0 , 0
       0    .035       0       0    .035       0 107.717    .035       0
Bank Sta=0,107.717
XS Rating Curve= 0
Exp/Cntr=.3,.1

Type RM Length L Ch R = 1 ,356.95  ,390.092,390.092,390.092
#Sta/Elev= 25
       0  39.993  12.579  40.289   20.21   40.65  20.394  43.438  22.953  43.438
  23.346   40.65  24.452  40.617  24.652  36.122  27.139  35.827  27.736   23.72
  33.796  23.524   38.94  23.294   43.78  22.408  50.981  23.163  57.828  22.867
  65.581  22.802   71.05  23.425  71.194  35.663   73.34  35.696  73.888  38.156
  76.037  38.419  76.138  43.241  77.572  43.209  77.638  40.584 107.717  40.289
#Mann= 3 , 0 , 0
       0    .035       0       0    .035       0 107.717    .035       0
Bank Sta=0,107.717
XS Rating Curve= 0
Exp/Cntr=.3,.1

Type RM Length L Ch R = 1 ,356.35  ,390.092,390.092,390.092
#Sta/Elev= 25
       0   40.65  13.366  40.912  20.856  41.437  21.591  44.226  22.848  44.226
   23.35  38.091  25.558  37.828  25.666  36.811  28.596  36.516  29.508  23.786
  34.623  22.671  40.945  22.572  47.083  22.113  55.909   22.08  63.504  22.277
  72.867   23.13  73.022  36.056  74.951  35.892  75.453  37.795  78.307   37.73
  78.783  44.094  79.839  44.029  80.197  42.421  98.606  40.551 116.391  40.354
#Mann= 3 , 0 , 0
       0    .035       0       0    .035       0 116.391    .035       0
Bank Sta=0,116.391
XS Rating Curve= 0
Exp/Cntr=.3,.1

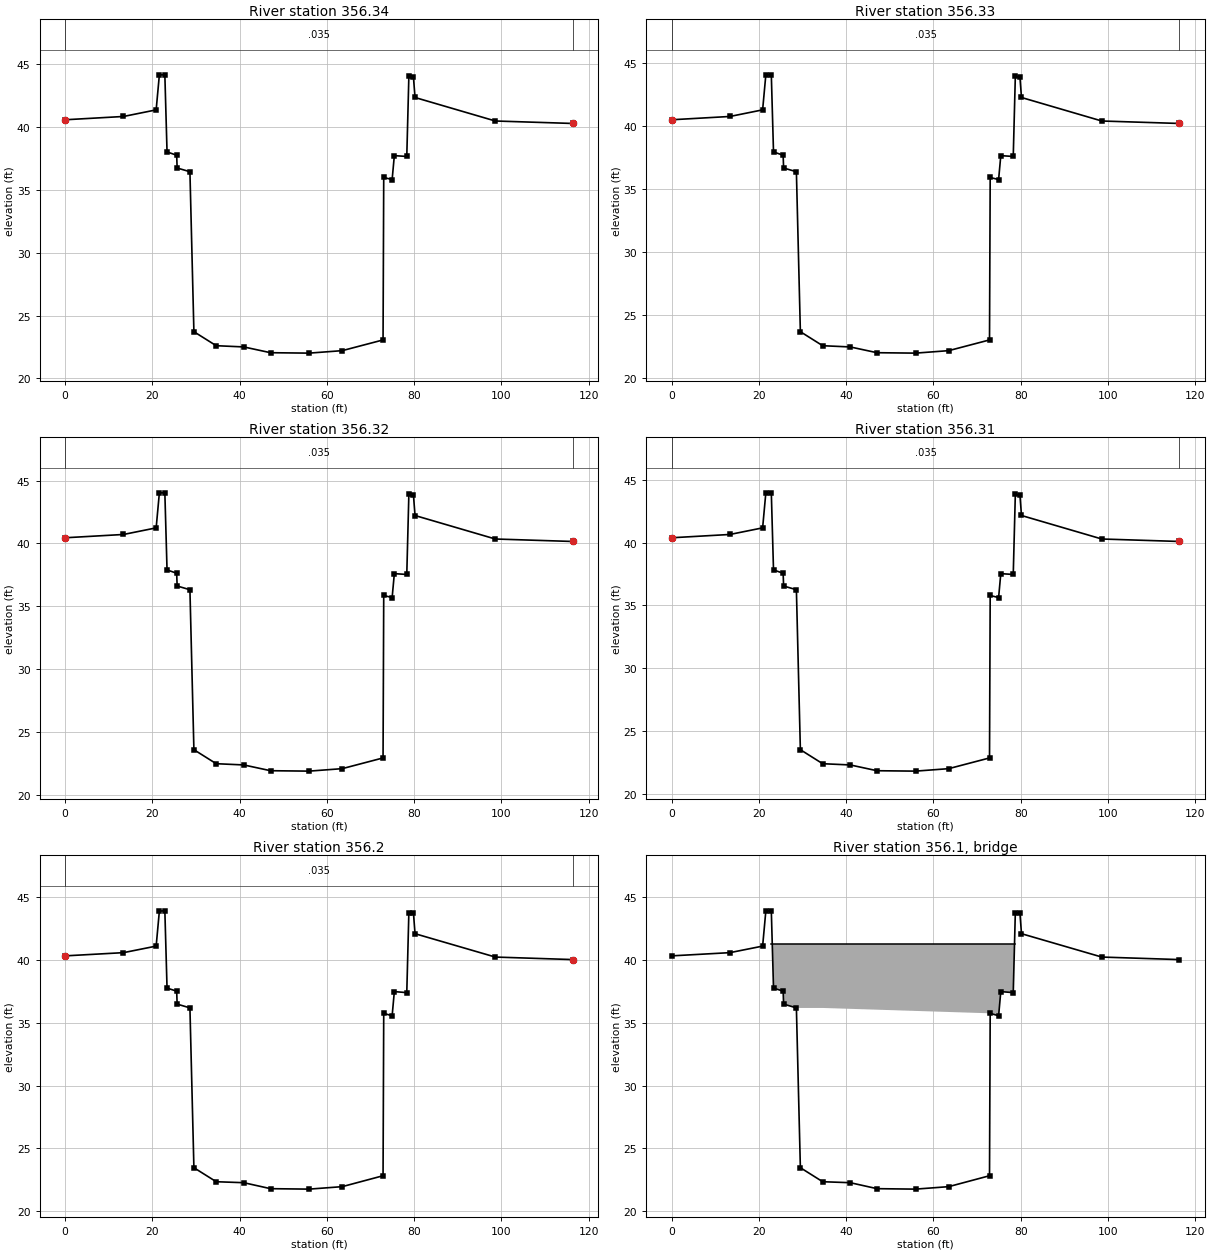
Type RM Length L Ch R = 1 ,356.34  ,390.092,390.092,390.092
#Sta/Elev= 25
       0  40.584  13.366  40.846  20.856  41.371  21.591   44.16  22.848   44.16
   23.35  38.025  25.558  37.762  25.666  36.745  28.596   36.45  29.508   23.72
  34.623  22.605  40.945  22.507  47.083  22.047  55.909  22.014  63.504  22.211
  72.867  23.064  73.022  35.991  74.951  35.827  75.453   37.73  78.307  37.664
  78.783  44.029  79.839  43.963  80.197  42.356  98.606  40.486 116.391  40.289
#Mann= 3 , 0 , 0
       0    .035       0       0    .035       0 116.391    .035       0
Bank Sta=0,116.391
XS Rating Curve= 0
Exp/Cntr=.3,.1

Type RM Length L Ch R = 1 ,356.33  ,390.092,390.092,390.092
#Sta/Elev= 25
       0  40.518  13.366  40.781  20.856  41.306  21.591  44.094  22.848  44.094
   23.35  37.959  25.558  37.697  25.666   36.68  28.596  36.385  29.508  23.655
  34.623  22.539  40.945  22.441  47.083  21.982  55.909  21.949  63.504  22.146
  72.867  22.999  73.022  35.925  74.951  35.761  75.453  37.664  78.307  37.598
  78.783  43.963  79.839  43.898  80.197   42.29  98.606   40.42 116.391  40.223
#Mann= 3 , 0 , 0
       0    .035       0       0    .035       0 116.391    .035       0
Bank Sta=0,116.391
XS Rating Curve= 0
Exp/Cntr=.3,.1

Type RM Length L Ch R = 1 ,356.32  ,390.092,390.092,390.092
#Sta/Elev= 25
       0  40.453  13.366  40.715  20.856   41.24  21.591  44.029  22.848  44.029
   23.35  37.894  25.558  37.631  25.666  36.614  28.596  36.319  29.508  23.589
  34.623  22.474  40.945  22.375  47.083  21.916  55.909  21.883  63.504   22.08
  72.867  22.933  73.022   35.86  74.951  35.696  75.453  37.598  78.307  37.533
  78.783  43.898  79.839  43.832  80.197  42.224  98.606  40.354 116.391  40.157
#Mann= 3 , 0 , 0
       0    .035       0       0    .035       0 116.391    .035       0
Bank Sta=0,116.391
XS Rating Curve= 0
Exp/Cntr=.3,.1

Type RM Length L Ch R = 1 ,356.31  ,390.092,390.092,390.092
#Sta/Elev= 25
       0  40.387  13.366   40.65  20.856  41.175  21.591  43.963  22.848  43.963
   23.35  37.828  25.558  37.566  25.666  36.549  28.596  36.253  29.508  23.524
  34.623  22.408  40.945   22.31  47.083   21.85  55.909  21.818  63.504  22.014
  72.867  22.867  73.022  35.794  74.951   35.63  75.453  37.533  78.307  37.467
  78.783  43.832  79.839  43.766  80.197  42.159  98.606  40.289 116.391  40.092
#Mann= 3 , 0 , 0
       0    .035       0       0    .035       0 116.391    .035       0
Bank Sta=0,116.391
XS Rating Curve= 0
Exp/Cntr=.3,.1

Type RM Length L Ch R = 1 ,356.2   ,26.247,26.247,26.247
XS GIS Cut Line= 2
      5291364.37     15915034.22      5291268.08     15915016.54
#Sta/Elev= 25
       0  40.335  13.366  40.591  20.856  41.112  21.591  43.904  22.848  43.921
   23.35  37.769  25.558  37.526  25.666  36.493  28.596  36.194  29.508  23.468
  34.623  22.352  40.945  22.274  47.083  21.798  55.909  21.762  63.504  21.959
  72.867  22.828  73.022  35.758  74.951  35.564  75.453   37.49  78.307  37.408
  78.783  43.776  79.839  43.727  80.197    42.1  98.606   40.24 116.391  40.039
#Mann= 3 , 0 , 0
       0    .035       0       0    .035       0 116.391    .035       0
Bank Sta=0,116.391
XS Rating Curve= 0
Exp/Cntr=.3,.1

Type RM Length L Ch R = 3 ,356.1   ,,,
BEGIN DESCRIPTION:
Ponte di Colognore
END DESCRIPTION:
Bridge Culvert--1,0,-1,-1, 0
Deck Dist Width WeirC Skew NumUp NumDn MinLoCord MaxHiCord MaxSubmerge Is_Ogee
1.64,22.966,2.61,0, 11, 11, , , .95, 0, 0,0,,
  22.835   23.36  25.558  25.656  28.609  34.613  73.031  74.967  75.459  78.314
  78.773
  41.273  41.273  41.273  41.273  41.273  41.273  41.273  41.273  41.273  41.273
  41.273
  41.273  37.762  37.533  36.483  36.188  36.188  35.761  35.564    37.5  37.402
  41.273
  22.835   23.36  25.558  25.656  28.609  34.613  73.031  74.967  75.459  78.314
  78.773
  41.273  41.273  41.273  41.273  41.273  41.273  41.273  41.273  41.273  41.273
  41.273
  41.273  37.762  37.533  36.483  36.188  36.188  35.761  35.564    37.5  37.402
  41.273
BR Coef=-1 , 0 , 0 ,1.25, 0 ,,,.8,-1,2,0,
WSPro=,,,, 1 ,,,, 0 ,,,, 0 ,,,,-1 ,-1 ,-1 , 0 , 0 , 0 , 0 , 0
BC Design=,, 0 ,, 0 ,,,,,,
BC HTab Sub Flow Pts= 40

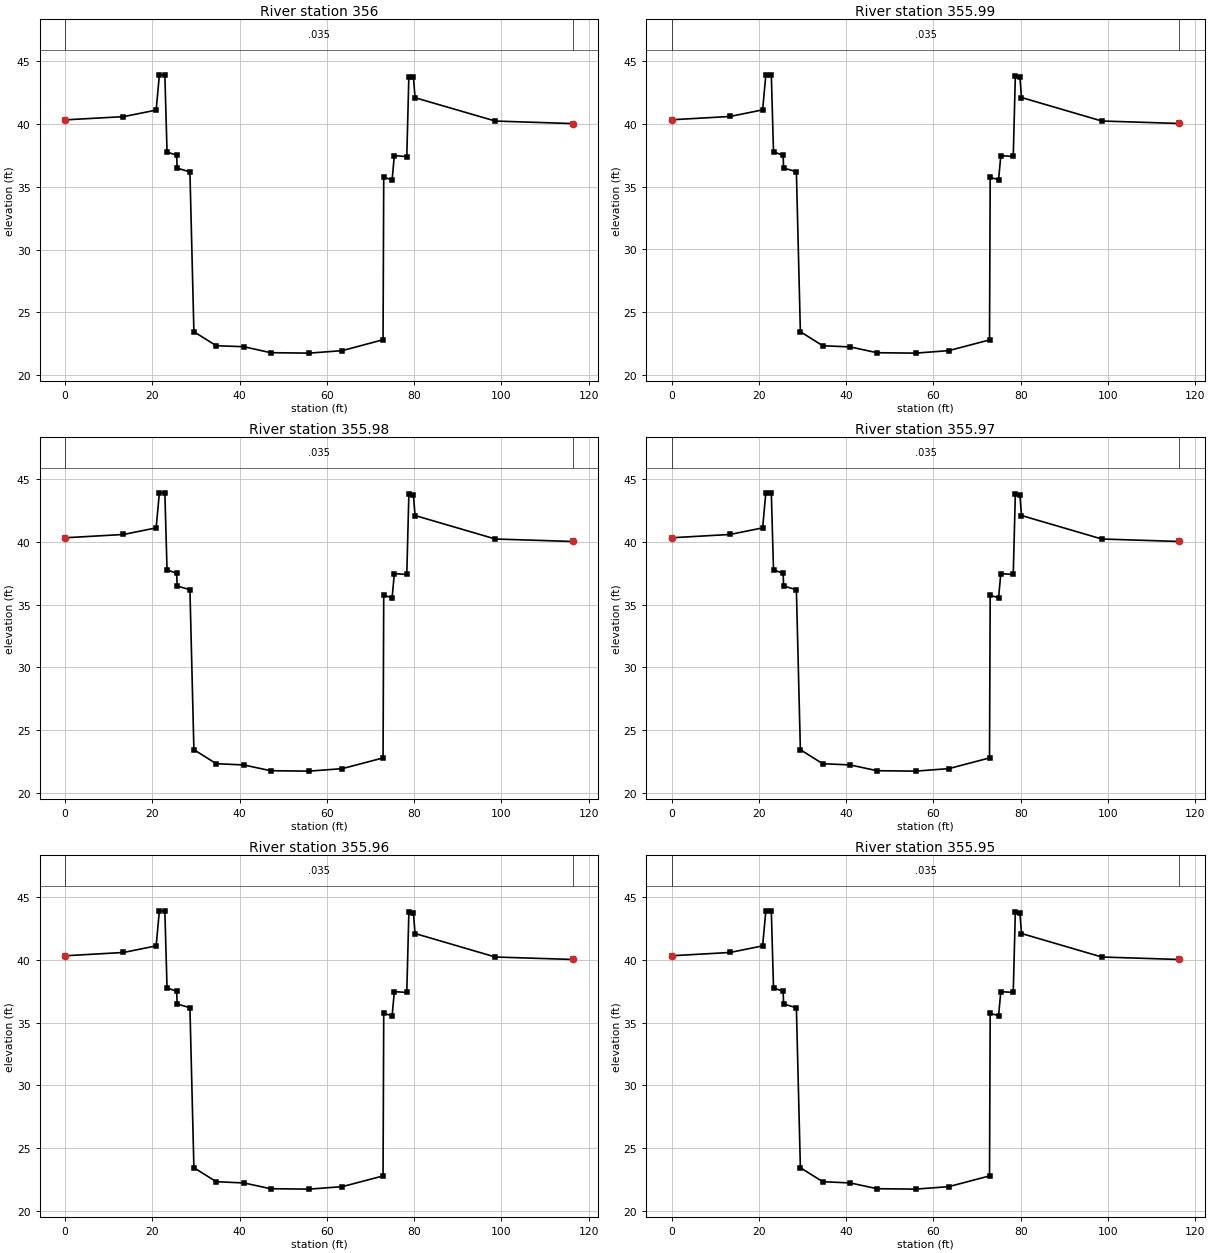
Type RM Length L Ch R = 1 ,356     ,246.063,246.063,246.063
XS GIS Cut Line= 2
      5291364.37     15915034.22      5291373.03     15915035.83
#Sta/Elev= 25
       0  40.335  13.366  40.591  20.856  41.112  21.591  43.904  22.848  43.921
   23.35  37.769  25.558  37.526  25.666  36.493  28.596  36.194  29.508  23.468
  34.623  22.352  40.945  22.274  47.083  21.798  55.909  21.762  63.504  21.959
  72.867  22.828  73.022  35.758  74.951  35.564  75.453   37.49  78.307  37.408
  78.783  43.776  79.839  43.727  80.197    42.1  98.606   40.24 116.391  40.039
#Mann= 3 , 0 , 0
       0    .035       0       0    .035       0 116.391    .035       0
Bank Sta=0,116.391
XS Rating Curve= 0
Exp/Cntr=.3,.1

Type RM Length L Ch R = 1 ,355.99  ,246.063,246.063,246.063
#Sta/Elev= 25
       0  40.322  13.366  40.584  20.856  41.109  21.591  43.898  22.848  43.898
   23.35  37.762  25.558    37.5  25.666  36.483  28.596  36.188  29.508  23.458
  34.623  22.343  40.945  22.244  47.083  21.785  55.909  21.752  63.504  21.949
  72.867  22.802  73.022  35.728  74.951  35.564  75.453  37.467  78.307  37.402
  78.783  43.766  79.839  43.701  80.197  42.093  98.606  40.223 116.391  40.026
#Mann= 3 , 0 , 0
       0    .035       0       0    .035       0 116.391    .035       0
Bank Sta=0,116.391
XS Rating Curve= 0
Exp/Cntr=.3,.1

Type RM Length L Ch R = 1 ,355.98  ,246.063,246.063,246.063
#Sta/Elev= 25
       0  40.322  13.366  40.584  20.856  41.109  21.591  43.898  22.848  43.898
   23.35  37.762  25.558    37.5  25.666  36.483  28.596  36.188  29.508  23.458
  34.623  22.343  40.945  22.244  47.083  21.785  55.909  21.752  63.504  21.949
  72.867  22.802  73.022  35.728  74.951  35.564  75.453  37.467  78.307  37.402
  78.783  43.766  79.839  43.701  80.197  42.093  98.606  40.223 116.391  40.026
#Mann= 3 , 0 , 0
       0    .035       0       0    .035       0 116.391    .035       0
Bank Sta=0,116.391
XS Rating Curve= 0
Exp/Cntr=.3,.1

Type RM Length L Ch R = 1 ,355.97  ,246.063,246.063,246.063
#Sta/Elev= 25
       0  40.322  13.366  40.584  20.856  41.109  21.591  43.898  22.848  43.898
   23.35  37.762  25.558    37.5  25.666  36.483  28.596  36.188  29.508  23.458
  34.623  22.343  40.945  22.244  47.083  21.785  55.909  21.752  63.504  21.949
  72.867  22.802  73.022  35.728  74.951  35.564  75.453  37.467  78.307  37.402
  78.783  43.766  79.839  43.701  80.197  42.093  98.606  40.223 116.391  40.026
#Mann= 3 , 0 , 0
       0    .035       0       0    .035       0 116.391    .035       0
Bank Sta=0,116.391
XS Rating Curve= 0
Exp/Cntr=.3,.1

Type RM Length L Ch R = 1 ,355.96  ,246.063,246.063,246.063
#Sta/Elev= 25
       0  40.322  13.366  40.584  20.856  41.109  21.591  43.898  22.848  43.898
   23.35  37.762  25.558    37.5  25.666  36.483  28.596  36.188  29.508  23.458
  34.623  22.343  40.945  22.244  47.083  21.785  55.909  21.752  63.504  21.949
  72.867  22.802  73.022  35.728  74.951  35.564  75.453  37.467  78.307  37.402
  78.783  43.766  79.839  43.701  80.197  42.093  98.606  40.223 116.391  40.026
#Mann= 3 , 0 , 0
       0    .035       0       0    .035       0 116.391    .035       0
Bank Sta=0,116.391
XS Rating Curve= 0
Exp/Cntr=.3,.1

Type RM Length L Ch R = 1 ,355.95  ,246.063,246.063,246.063
#Sta/Elev= 25
       0  40.322  13.366  40.584  20.856  41.109  21.591  43.898  22.848  43.898
   23.35  37.762  25.558    37.5  25.666  36.483  28.596  36.188  29.508  23.458
  34.623  22.343  40.945  22.244  47.083  21.785  55.909  21.752  63.504  21.949
  72.867  22.802  73.022  35.728  74.951  35.564  75.453  37.467  78.307  37.402
  78.783  43.766  79.839  43.701  80.197  42.093  98.606  40.223 116.391  40.026
#Mann= 3 , 0 , 0
       0    .035       0       0    .035       0 116.391    .035       0
Bank Sta=0,116.391
XS Rating Curve= 0
Exp/Cntr=.3,.1

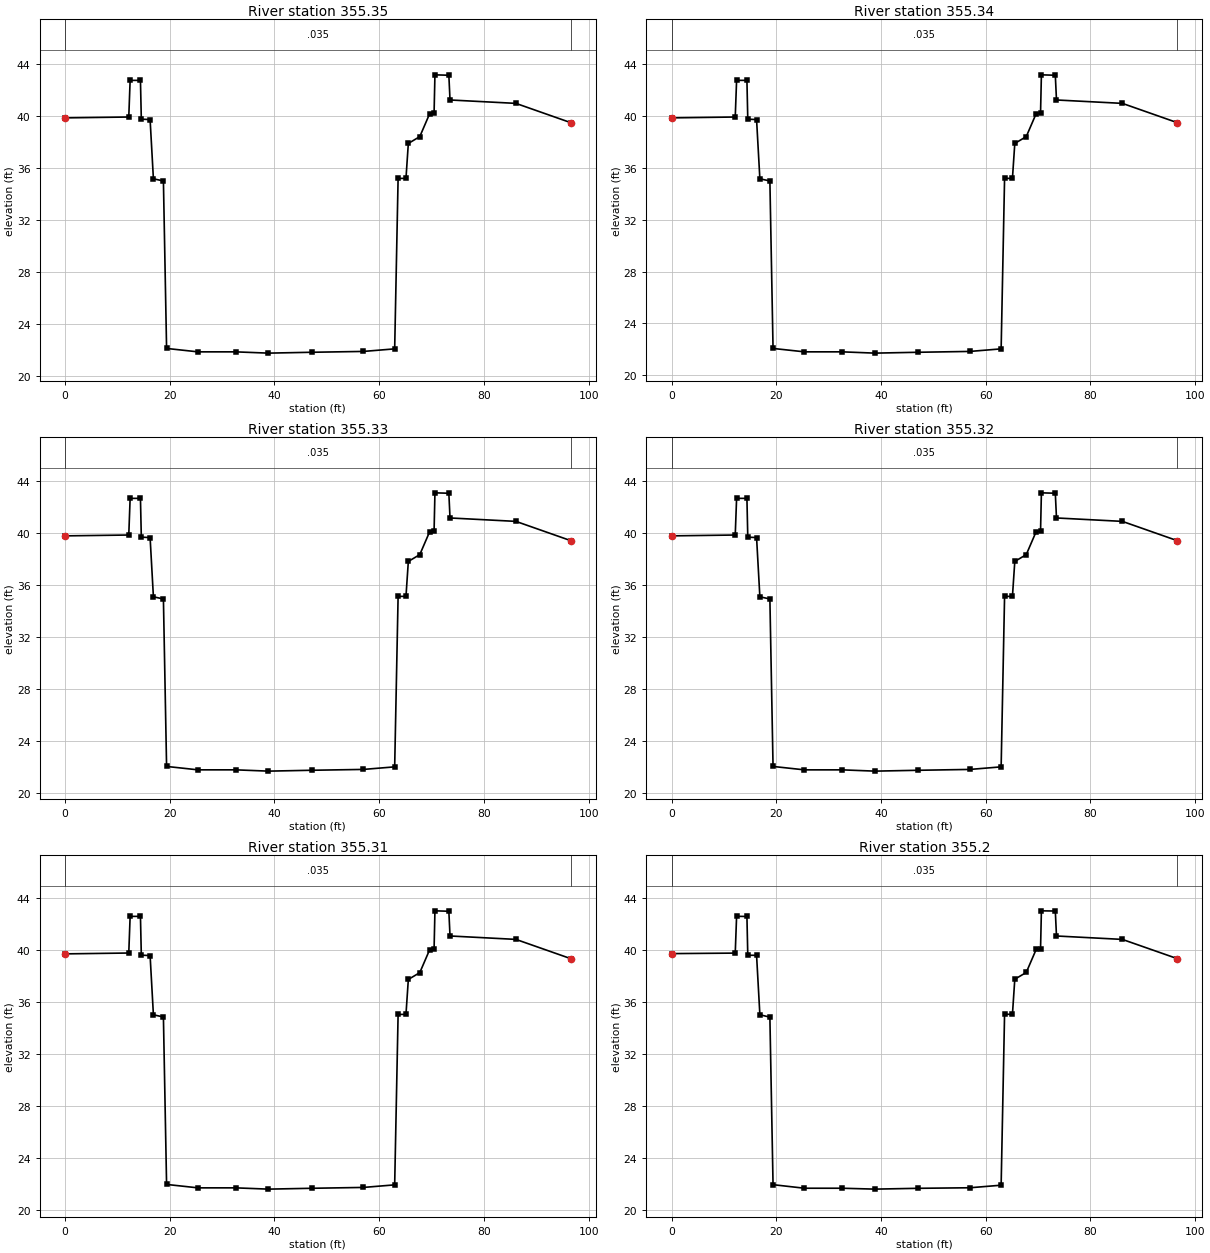
Type RM Length L Ch R = 1 ,355.35  ,246.063,246.063,246.063
#Sta/Elev= 26
       0  39.862  12.169  39.928  12.428  42.749    14.4  42.749  14.564  39.764
  16.243  39.731  16.873  35.171  18.786  35.007   19.39  22.113   25.39   21.85
  32.585   21.85  38.832  21.752  47.113  21.818  56.998  21.883  62.956   22.08
  63.612  35.203  65.115  35.203  65.564  37.894  67.753  38.419  69.646   40.19
  70.482  40.223  70.646  43.176  73.304  43.143  73.527   41.24  86.112  40.978
  96.542  39.501
#Mann= 3 , 0 , 0
       0    .035       0       0    .035       0  96.542    .035       0
Bank Sta=0,96.542
XS Rating Curve= 0
Exp/Cntr=.3,.1

Type RM Length L Ch R = 1 ,355.34  ,246.063,246.063,246.063
#Sta/Elev= 26
       0  39.829  12.169  39.895  12.428  42.717    14.4  42.717  14.564  39.731
  16.243  39.698  16.873  35.138  18.786  34.974   19.39   22.08   25.39  21.818
  32.585  21.818  38.832  21.719  47.113  21.785  56.998   21.85  62.956  22.047
  63.612  35.171  65.115  35.171  65.564  37.861  67.753  38.386  69.646  40.157
  70.482   40.19  70.646  43.143  73.304   43.11  73.527  41.207  86.112  40.945
  96.542  39.469
#Mann= 3 , 0 , 0
       0    .035       0       0    .035       0  96.542    .035       0
Bank Sta=0,96.542
XS Rating Curve= 0
Exp/Cntr=.3,.1

Type RM Length L Ch R = 1 ,355.33  ,246.063,246.063,246.063
#Sta/Elev= 26
       0  39.797  12.169  39.862  12.428  42.684    14.4  42.684  14.564  39.698
  16.243  39.665  16.873  35.105  18.786  34.941   19.39  22.047   25.39  21.785
  32.585  21.785  38.832  21.686  47.113  21.752  56.998  21.818  62.956  22.014
  63.612  35.138  65.115  35.138  65.564  37.828  67.753  38.353  69.646  40.125
  70.482  40.157  70.646   43.11  73.304  43.077  73.527  41.175  86.112  40.912
  96.542  39.436
#Mann= 3 , 0 , 0
       0    .035       0       0    .035       0  96.542    .035       0
Bank Sta=0,96.542
XS Rating Curve= 0
Exp/Cntr=.3,.1

Type RM Length L Ch R = 1 ,355.32  ,246.063,246.063,246.063
#Sta/Elev= 26
       0  39.764  12.169  39.829  12.428  42.651    14.4  42.651  14.564  39.665
  16.243  39.633  16.873  35.072  18.786  34.908   19.39  22.014   25.39  21.752
  32.585  21.752  38.832  21.654  47.113  21.719  56.998  21.785  62.956  21.982
  63.612  35.105  65.115  35.105  65.564  37.795  67.753   38.32  69.646  40.092
  70.482  40.125  70.646  43.077  73.304  43.045  73.527  41.142  86.112  40.879
  96.542  39.403
#Mann= 3 , 0 , 0
       0    .035       0       0    .035       0  96.542    .035       0
Bank Sta=0,96.542
XS Rating Curve= 0
Exp/Cntr=.3,.1

Type RM Length L Ch R = 1 ,355.31  ,246.063,246.063,246.063
#Sta/Elev= 26
       0  39.731  12.169  39.797  12.428  42.618    14.4  42.618  14.564  39.633
  16.243    39.6  16.873  35.039  18.786  34.875   19.39  21.982   25.39  21.719
  32.585  21.719  38.832  21.621  47.113  21.686  56.998  21.752  62.956  21.949
  63.612  35.072  65.115  35.072  65.564  37.762  67.753  38.287  69.646  40.059
  70.482  40.092  70.646  43.045  73.304  43.012  73.527  41.109  86.112  40.846
  96.542   39.37
#Mann= 3 , 0 , 0
       0    .035       0       0    .035       0  96.542    .035       0
Bank Sta=0,96.542
XS Rating Curve= 0
Exp/Cntr=.3,.1

Type RM Length L Ch R = 1 ,355.2   ,26.247,26.247,26.247
XS GIS Cut Line= 3
      5293072.11     15912997.64      5293012.27      15912927.3
      5293012.27     15912927.26
#Sta/Elev= 26
       0  39.728  12.169  39.767  12.428  42.595    14.4  42.585  14.564  39.603
  16.243  39.596  16.873  35.026  18.786  34.843   19.39  21.959   25.39  21.686
  32.585  21.686  38.832  21.617  47.113   21.68  56.998  21.722  62.956  21.919
  63.612  35.069  65.115  35.056  65.564  37.759  67.753  38.278  69.646  40.049
  70.482  40.075  70.646  43.018  73.304  43.002  73.527  41.083  86.112   40.82
  96.542   39.35
#Mann= 3 , 0 , 0
       0    .035       0       0    .035       0  96.542    .035       0
Bank Sta=0,96.542
XS Rating Curve= 0
Exp/Cntr=.3,.1

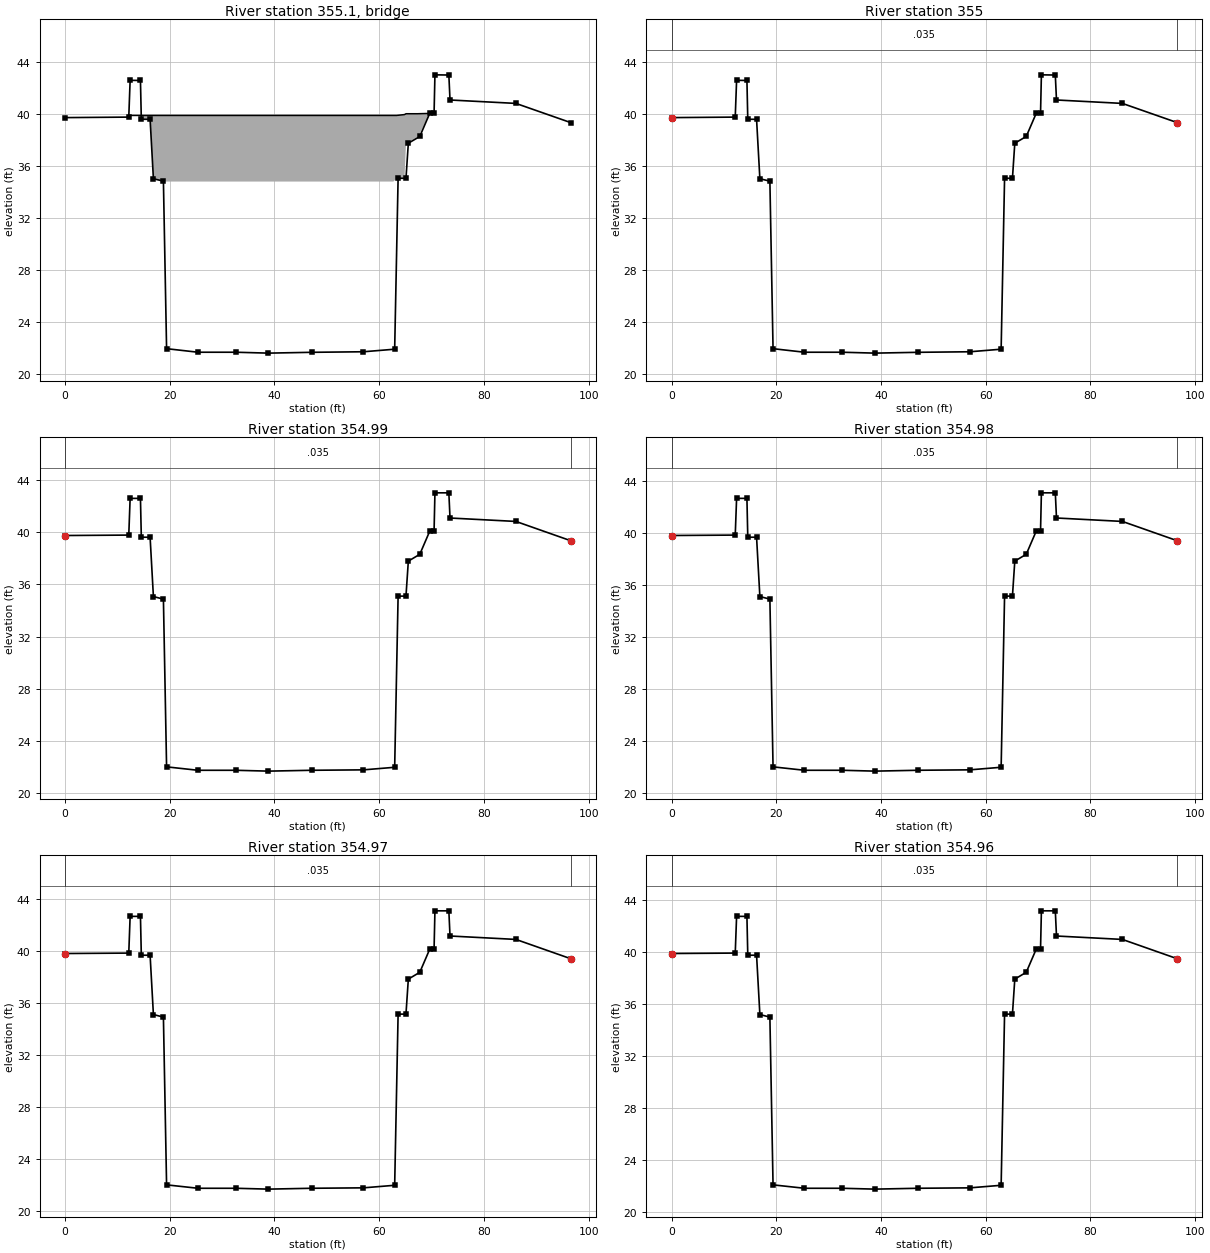
Type RM Length L Ch R = 3 ,355.1   ,,,
BEGIN DESCRIPTION:
Ponte di Patrignone
END DESCRIPTION:
Bridge Culvert--1,0,-1,-1, 0
Deck Dist Width WeirC Skew NumUp NumDn MinLoCord MaxHiCord MaxSubmerge Is_Ogee
1.64,22.966,2.61,0, 19, 19, , , .95, 0, 0,0,,
  12.139  12.336  14.304  14.469  16.142  16.765  18.668  19.193  25.164  32.349
  38.583  46.883  56.759  62.697   63.32  64.829  65.125  67.323  70.472
  39.895  39.895  39.895  39.895  39.895  39.895  39.895  39.895  39.895  39.895
  39.895  39.895  39.895  39.895  39.895  39.961  40.026  40.026  40.059
   34.81   34.81   34.81   34.81   34.81   34.81   34.81   34.81   34.81   34.81
   34.81   34.81   34.81   34.81  35.039  35.039   37.73  38.255  40.059
  12.139  12.336  14.304  14.469  16.142  16.765  18.668  19.193  25.164  32.349
  38.583  46.883  56.759  62.697   63.32  64.829  65.125  67.323  70.472
  39.895  39.895  39.895  39.895  39.895  39.895  39.895  39.895  39.895  39.895
  39.895  39.895  39.895  39.895  39.895  39.961  40.026  40.026  40.059
   34.81   34.81   34.81   34.81   34.81   34.81   34.81   34.81   34.81   34.81
   34.81   34.81   34.81   34.81  35.039  35.039   37.73  38.255  40.059
BR Coef=-1 , 0 , 0 ,1.25, 0 ,,,.8,-1,2,0,
WSPro=,,,, 1 ,,,, 0 ,,,, 0 ,,,,-1 ,-1 ,-1 , 0 , 0 , 0 , 0 , 0
BC Design=,, 0 ,, 0 ,,,,,,
BC HTab Sub Flow Pts= 40

Type RM Length L Ch R = 1 ,355     ,262.467,262.467,262.467
XS GIS Cut Line= 3
      5293072.11     15912997.64      5293012.27      15912927.3
      5293012.27     15912927.26
#Sta/Elev= 26
       0  39.728  12.169  39.767  12.428  42.595    14.4  42.585  14.564  39.603
  16.243  39.596  16.873  35.026  18.786  34.843   19.39  21.959   25.39  21.686
  32.585  21.686  38.832  21.617  47.113   21.68  56.998  21.722  62.956  21.919
  63.612  35.069  65.115  35.056  65.564  37.759  67.753  38.278  69.646  40.049
  70.482  40.075  70.646  43.018  73.304  43.002  73.527  41.083  86.112   40.82
  96.542   39.35
#Mann= 3 , 0 , 0
       0    .035       0       0    .035       0  96.542    .035       0
Bank Sta=0,96.542
XS Rating Curve= 0
Exp/Cntr=.3,.1

Type RM Length L Ch R = 1 ,354.99  ,262.467,262.467,262.467
#Sta/Elev= 26
       0  39.764  12.169  39.797  12.428  42.618    14.4  42.618  14.564  39.633
  16.243  39.633  16.873  35.072  18.786  34.875   19.39  21.982   25.39  21.719
  32.585  21.719  38.832  21.654  47.113  21.719  56.998  21.752  62.956  21.949
  63.612  35.105  65.115  35.105  65.564  37.795  67.753   38.32  69.646  40.092
  70.482  40.125  70.646  43.045  73.304  43.045  73.527  41.109  86.112  40.846
  96.542   39.37
#Mann= 3 , 0 , 0
       0    .035       0       0    .035       0  96.542    .035       0
Bank Sta=0,96.542
XS Rating Curve= 0
Exp/Cntr=.3,.1

Type RM Length L Ch R = 1 ,354.98  ,262.467,262.467,262.467
#Sta/Elev= 26
       0  39.797  12.169  39.829  12.428  42.651    14.4  42.651  14.564  39.665
  16.243  39.665  16.873  35.105  18.786  34.908   19.39  22.014   25.39  21.752
  32.585  21.752  38.832  21.686  47.113  21.752  56.998  21.785  62.956  21.982
  63.612  35.138  65.115  35.138  65.564  37.828  67.753  38.353  69.646  40.125
  70.482  40.157  70.646  43.077  73.304  43.077  73.527  41.142  86.112  40.879
  96.542  39.403
#Mann= 3 , 0 , 0
       0    .035       0       0    .035       0  96.542    .035       0
Bank Sta=0,96.542
XS Rating Curve= 0
Exp/Cntr=.3,.1

Type RM Length L Ch R = 1 ,354.97  ,262.467,262.467,262.467
#Sta/Elev= 26
       0  39.829  12.169  39.862  12.428  42.684    14.4  42.684  14.564  39.698
  16.243  39.698  16.873  35.138  18.786  34.941   19.39  22.047   25.39  21.785
  32.585  21.785  38.832  21.719  47.113  21.785  56.998  21.818  62.956  22.014
  63.612  35.171  65.115  35.171  65.564  37.861  67.753  38.386  69.646  40.157
  70.482   40.19  70.646   43.11  73.304   43.11  73.527  41.175  86.112  40.912
  96.542  39.436
#Mann= 3 , 0 , 0
       0    .035       0       0    .035       0  96.542    .035       0
Bank Sta=0,96.542
XS Rating Curve= 0
Exp/Cntr=.3,.1

Type RM Length L Ch R = 1 ,354.96  ,262.467,262.467,262.467
#Sta/Elev= 26
       0  39.862  12.169  39.895  12.428  42.717    14.4  42.717  14.564  39.731
  16.243  39.731  16.873  35.171  18.786  34.974   19.39   22.08   25.39  21.818
  32.585  21.818  38.832  21.752  47.113  21.818  56.998   21.85  62.956  22.047
  63.612  35.203  65.115  35.203  65.564  37.894  67.753  38.419  69.646   40.19
  70.482  40.223  70.646  43.143  73.304  43.143  73.527  41.207  86.112  40.945
  96.542  39.469
#Mann= 3 , 0 , 0
       0    .035       0       0    .035       0  96.542    .035       0
Bank Sta=0,96.542
XS Rating Curve= 0
Exp/Cntr=.3,.1