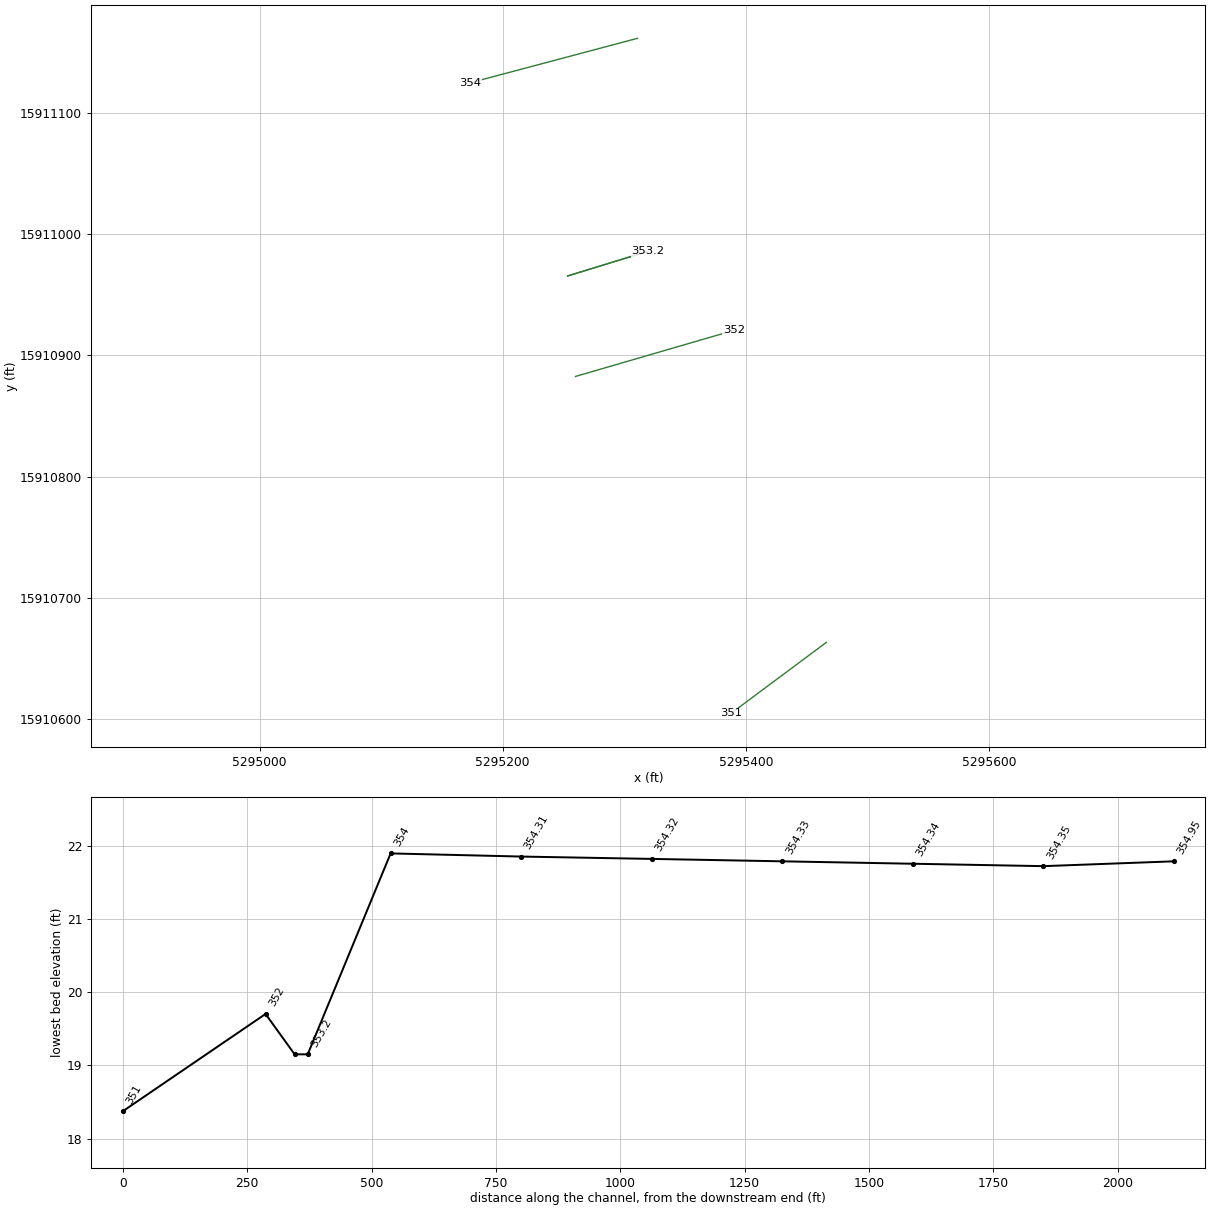
HEC-RAS study ozz_def.prj: ozzeri

--- ozz_def.g04 (geometry) --- (continued)

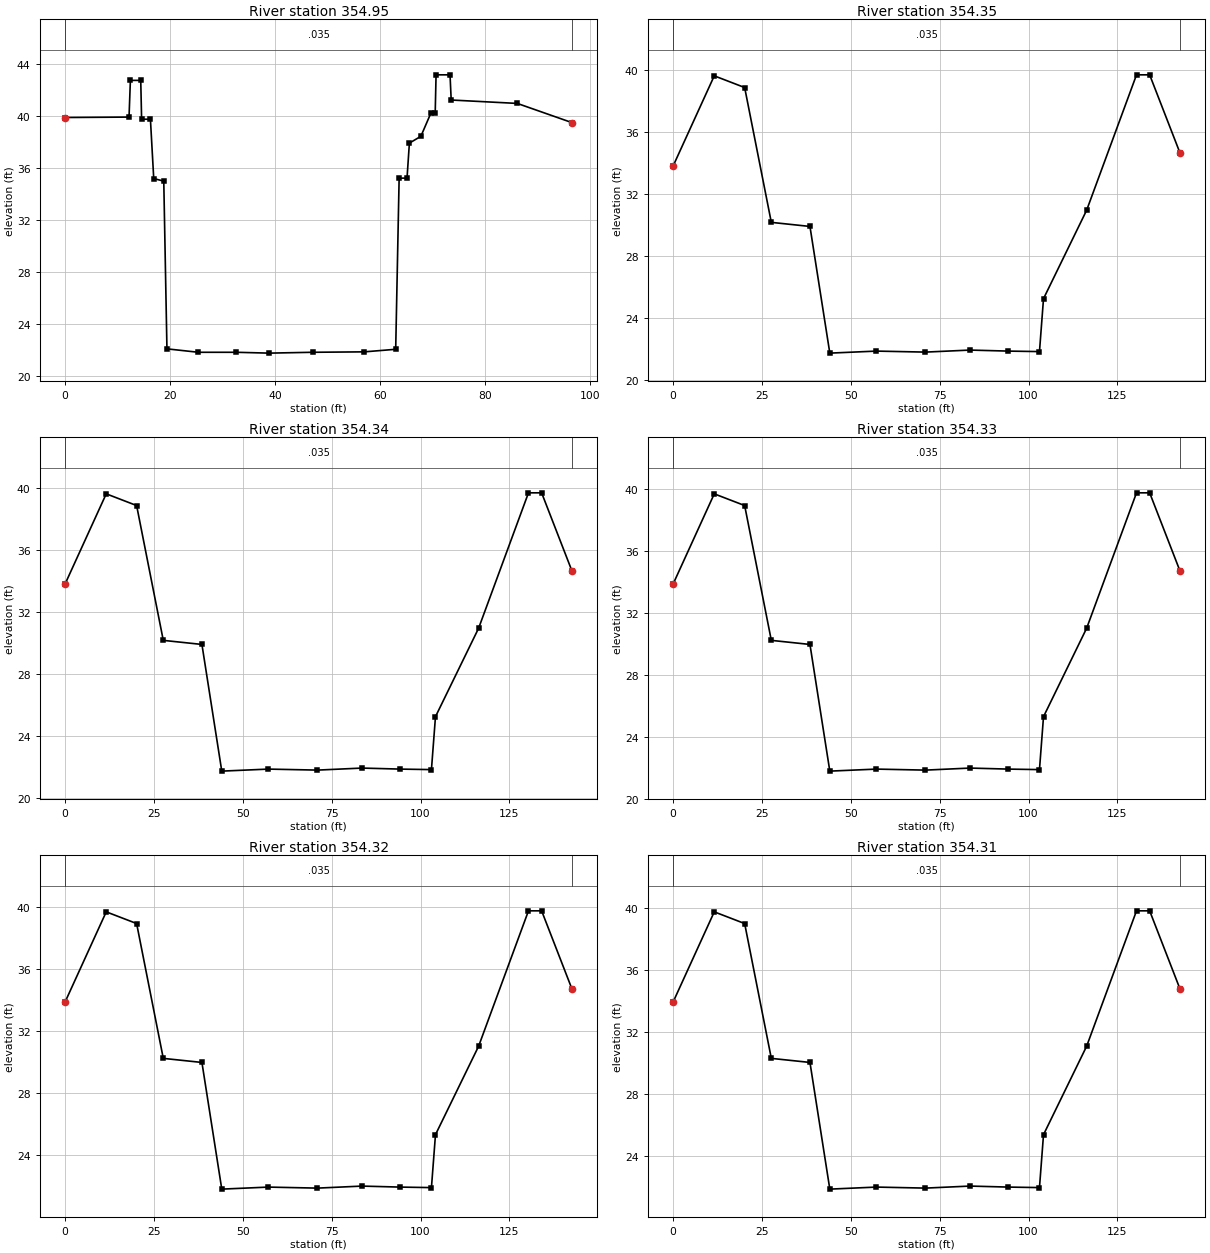
Type RM Length L Ch R = 1 ,354.95  ,262.467,262.467,262.467
#Sta/Elev= 26
       0  39.895  12.169  39.928  12.428  42.749    14.4  42.749  14.564  39.764
  16.243  39.764  16.873  35.203  18.786  35.007   19.39  22.113   25.39   21.85
  32.585   21.85  38.832  21.785  47.113   21.85  56.998  21.883  62.956   22.08
  63.612  35.236  65.115  35.236  65.564  37.927  67.753  38.451  69.646  40.223
  70.482  40.256  70.646  43.176  73.304  43.176  73.527   41.24  86.112  40.978
  96.542  39.501
#Mann= 3 , 0 , 0
       0    .035       0       0    .035       0  96.542    .035       0
Bank Sta=0,96.542
XS Rating Curve= 0
Exp/Cntr=.3,.1

Type RM Length L Ch R = 1 ,354.35  ,262.467,262.467,262.467
#Sta/Elev= 16
       0  33.793  11.562    39.6  20.115  38.845  27.615  30.151  38.488  29.888
  44.075  21.719  57.185   21.85  70.991  21.785   83.53  21.916  94.295   21.85
 103.068  21.818 104.203   25.23 116.348  30.938 130.371  39.665 134.072  39.665
 142.628  34.613
#Mann= 3 , 0 , 0
       0    .035       0       0    .035       0 142.628    .035       0
Bank Sta=0,142.628
XS Rating Curve= 0
Exp/Cntr=.3,.1

Type RM Length L Ch R = 1 ,354.34  ,262.467,262.467,262.467
#Sta/Elev= 16
       0  33.825  11.562  39.633  20.115  38.878  27.615  30.184  38.488  29.921
  44.075  21.752  57.185  21.883  70.991  21.818   83.53  21.949  94.295  21.883
 103.068   21.85 104.203  25.262 116.348  30.971 130.371  39.698 134.072  39.698
 142.628  34.646
#Mann= 3 , 0 , 0
       0    .035       0       0    .035       0 142.628    .035       0
Bank Sta=0,142.628
XS Rating Curve= 0
Exp/Cntr=.3,.1

Type RM Length L Ch R = 1 ,354.33  ,262.467,262.467,262.467
#Sta/Elev= 16
       0  33.858  11.562  39.665  20.115  38.911  27.615  30.217  38.488  29.954
  44.075  21.785  57.185  21.916  70.991   21.85   83.53  21.982  94.295  21.916
 103.068  21.883 104.203  25.295 116.348  31.004 130.371  39.731 134.072  39.731
 142.628  34.678
#Mann= 3 , 0 , 0
       0    .035       0       0    .035       0 142.628    .035       0
Bank Sta=0,142.628
XS Rating Curve= 0
Exp/Cntr=.3,.1

Type RM Length L Ch R = 1 ,354.32  ,262.467,262.467,262.467
#Sta/Elev= 16
       0  33.891  11.562  39.698  20.115  38.944  27.615  30.249  38.488  29.987
  44.075  21.818  57.185  21.949  70.991  21.883   83.53  22.014  94.295  21.949
 103.068  21.916 104.203  25.328 116.348  31.037 130.371  39.764 134.072  39.764
 142.628  34.711
#Mann= 3 , 0 , 0
       0    .035       0       0    .035       0 142.628    .035       0
Bank Sta=0,142.628
XS Rating Curve= 0
Exp/Cntr=.3,.1

Type RM Length L Ch R = 1 ,354.31  ,262.467,262.467,262.467
#Sta/Elev= 16
       0  33.924  11.562  39.731  20.115  38.976  27.615  30.282  38.488   30.02
  44.075   21.85  57.185  21.982  70.991  21.916   83.53  22.047  94.295  21.982
 103.068  21.949 104.203  25.361 116.348   31.07 130.371  39.797 134.072  39.797
 142.628  34.744
#Mann= 3 , 0 , 0
       0    .035       0       0    .035       0 142.628    .035       0
Bank Sta=0,142.628
XS Rating Curve= 0
Exp/Cntr=.3,.1

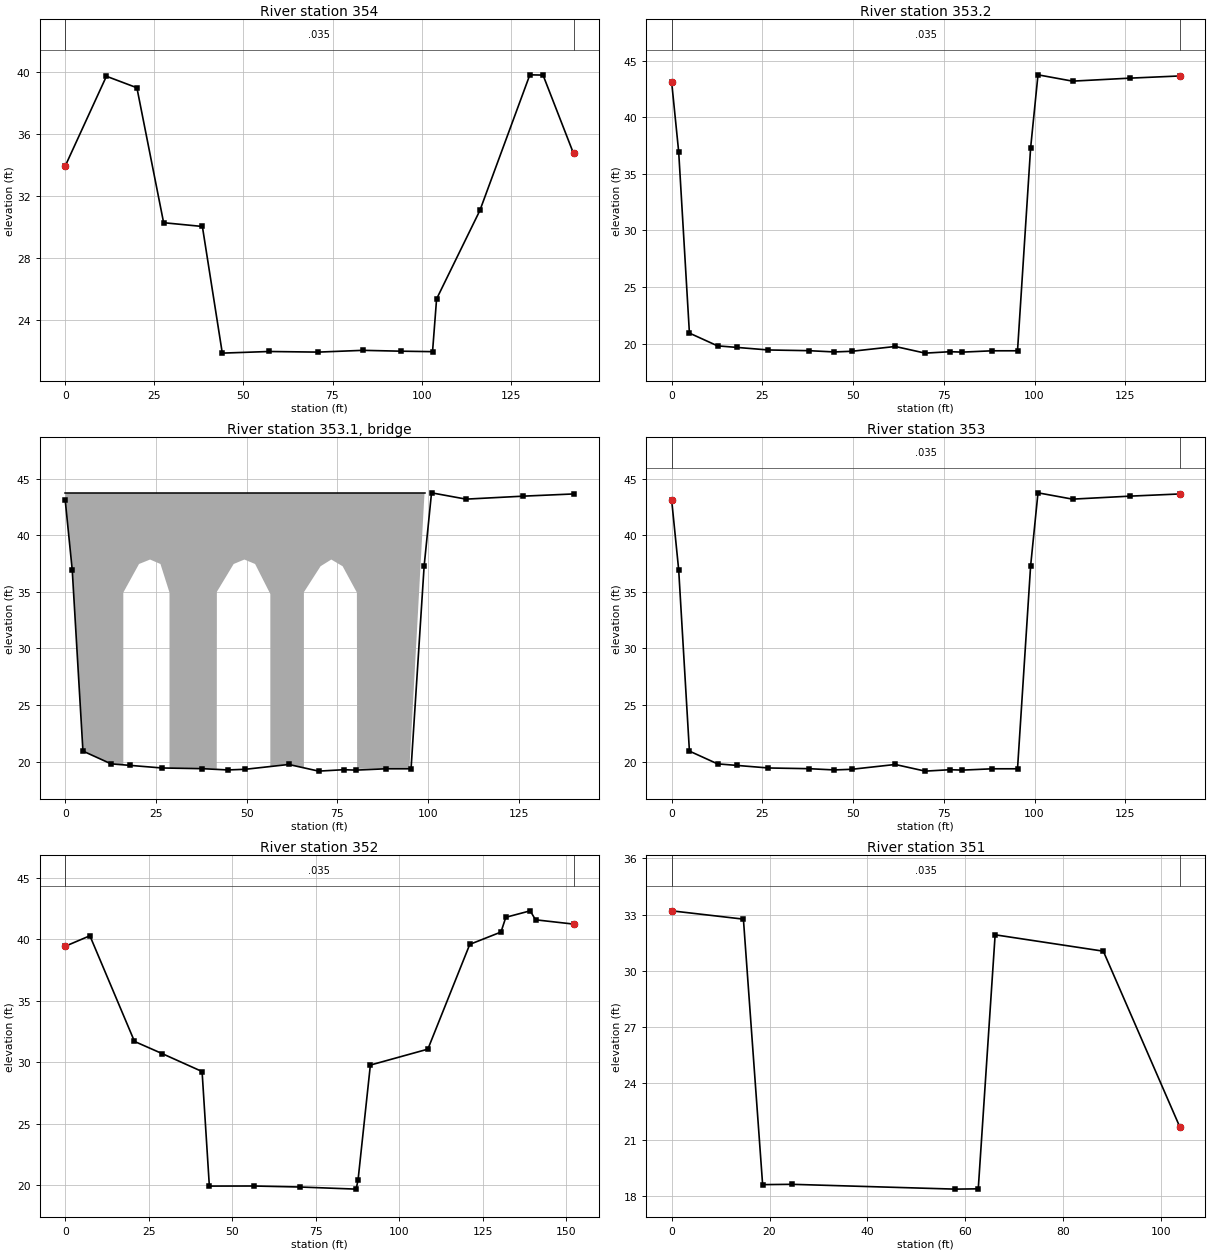
Type RM Length L Ch R = 1 ,354     ,166.732,166.732,166.732
XS GIS Cut Line= 3
      5295310.79     15911161.29      5295173.46      15911124.7
      5295173.46      15911124.7
#Sta/Elev= 16
       0  33.957  11.562  39.751  20.115  39.009  27.615  30.305  38.488  30.062
  44.075  21.893  57.185  21.998  70.991  21.959   83.53  22.073  94.295  22.018
 103.068  21.988 104.203  25.387 116.348  31.093 130.371  39.843 134.072  39.826
 142.628   34.77
#Mann= 3 , 0 , 0
       0    .035       0       0    .035       0 142.628    .035       0
Bank Sta=0,142.628
XS Rating Curve= 0
Exp/Cntr=.3,.1

Type RM Length L Ch R = 1 ,353.2   ,26.247,26.247,26.247
XS GIS Cut Line= 3
      5295253.38     15910965.42      5295317.45      15910985.1
      5295319.29     15910985.66
#Sta/Elev= 20
       0  43.104   1.936  36.936   4.888  20.922  12.631  19.793  17.946  19.656
   26.64  19.429  37.762  19.367  44.816  19.255  49.672  19.314  61.614  19.738
  69.849   19.15  76.739  19.275  80.118  19.239  88.386  19.357  95.308  19.357
  98.917  37.297 100.951   43.76 110.466  43.202 126.181  43.465 140.085  43.661
#Mann= 3 , 0 , 0
       0    .035       0       0    .035       0 140.085    .035       0
Bank Sta=0,140.085
XS Rating Curve= 0
Exp/Cntr=.3,.1

Type RM Length L Ch R = 3 ,353.1   ,,,
BEGIN DESCRIPTION:
Ponte di Rigoli
END DESCRIPTION:
Bridge Culvert--1,0,-1,-1, 0
Deck Dist Width WeirC Skew NumUp NumDn MinLoCord MaxHiCord MaxSubmerge Is_Ogee
1.64,22.966,2.61,0, 26, 26, , , .95, 0, 0,0,,
       0    2.92  10.663   16.01   16.01  20.341  23.392  26.247   28.74   28.74
  41.765  41.798  46.424  49.377  52.329  56.529  56.529  65.781  65.781  70.374
  73.327  76.444  80.381  80.446  94.849  99.016
  43.734  43.734  43.734  43.734  43.734  43.734  43.734  43.734  43.734  43.734
  43.734  43.734  43.734  43.734  43.734  43.734  43.734  43.734  43.734  43.734
  43.734  43.734  43.734  43.734  43.734  43.734
  36.909  20.899  19.783  19.521  34.941  37.467  37.861  37.467  34.941  19.357
  19.357  35.007  37.467  37.861  37.467   34.81   19.39  19.357  34.974   37.27
  37.861   37.27  34.941  19.357  19.357  43.734
       0    2.92  10.663   16.01   16.01  20.341  23.392  26.247   28.74   28.74
  41.765  41.798  46.424  49.377  52.329  56.529  56.529  65.781  65.781  70.374
  73.327  76.444  80.381  80.446  94.849  99.016
  43.734  43.734  43.734  43.734  43.734  43.734  43.734  43.734  43.734  43.734
  43.734  43.734  43.734  43.734  43.734  43.734  43.734  43.734  43.734  43.734
  43.734  43.734  43.734  43.734  43.734  43.734
  36.909  20.899  19.783  19.521  34.941  37.467  37.861  37.467  34.941  19.357
  19.357  35.007  37.467  37.861  37.467   34.81   19.39  19.357  34.974   37.27
  37.861   37.27  34.941  19.357  19.357  43.734
BR Coef=-1 , 0 , 0 ,1.25, 0 ,,,.8,-1,2,0,
WSPro=,,,, 1 ,,,, 0 ,,,, 0 ,,,,-1 ,-1 ,-1 , 0 , 0 , 0 , 0 , 0
BC Design=,, 0 ,, 0 ,,,,,,
BC HTab Sub Flow Pts= 40

Type RM Length L Ch R = 1 ,353     ,58.53,58.53,58.53
XS GIS Cut Line= 3
      5295253.38     15910965.42      5295317.45      15910985.1
      5295319.29     15910985.66
#Sta/Elev= 20
       0  43.104   1.936  36.936   4.888  20.922  12.631  19.793  17.946  19.656
   26.64  19.429  37.762  19.367  44.816  19.255  49.672  19.314  61.614  19.738
  69.849   19.15  76.739  19.275  80.118  19.239  88.386  19.357  95.308  19.357
  98.917  37.297 100.951   43.76 110.466  43.202 126.181  43.465 140.085  43.661
#Mann= 3 , 0 , 0
       0    .035       0       0    .035       0 140.085    .035       0
Bank Sta=0,140.085
XS Rating Curve= 0
Exp/Cntr=.3,.1

Type RM Length L Ch R = 1 ,352     ,286.942,286.942,286.942
XS GIS Cut Line= 2
      5295259.84     15910882.58      5295390.19      15910920.6
#Sta/Elev= 18
       0  39.419   7.392  40.272  20.745  31.693  29.078  30.699  40.988  29.249
  43.166  19.948  56.509  19.954  70.443  19.872  87.123  19.701  87.694  20.446
  91.381  29.774 108.599  31.066 121.148  39.573 130.495  40.574 131.942  41.772
 139.242  42.297  140.84  41.568 152.221   41.22
#Mann= 3 , 0 , 0
       0    .035       0       0    .035       0 152.221    .035       0
Bank Sta=0,152.221
XS Rating Curve= 0
Exp/Cntr=.3,.1

Type RM Length L Ch R = 1 ,351     ,0,0,0
XS GIS Cut Line= 2
      5295466.11     15910663.32      5295387.73     15910604.86
#Sta/Elev= 9
       0  33.196  14.662  32.753  18.589  18.612   24.59  18.629   57.93  18.373
  62.661  18.389  66.109  31.919  88.219  31.047 103.894  21.663
#Mann= 3 , 0 , 0
       0    .035       0       0    .035       0 103.894    .035       0
Bank Sta=0,103.894
XS Rating Curve= 0
Exp/Cntr=.3,.1

Storage Area=c01             ,5304201.08,15927614.9
Storage Area Surface Line= 8
        5302821.      15927749.9               .
      5303584.22     15928118.57               .
      5304897.21     15927950.39               .
 5305613.434792315926730.5582588               .
      5305634.55      15926456.3               .
      5304263.35     15926967.29               .
      5303331.96     15927413.58               .
        5302821.     15927769.32               .
Storage Area Type= 1
Storage Area Vol Elev= 8
   26.25       0   29.53      .1   32.81     1.5   36.09     8.5   39.37    39.1
   42.65   129.1   45.93 237.701   49.21   357.7

Storage Area=c02             ,5303328.48,15926897.6
Storage Area Surface Line= 13
       5302575.2     15927523.52               .
      5302348.82     15927484.71               .
      5302187.11     15927290.68               .
       5302497.6     15927044.91               .
      5303396.65     15926624.48               .
       5304049.9     15925757.78               .
      5305511.65     15926042.36               .
      5305589.27     15926249.34               .
      5304282.74      15926579.2               .
      5303571.26     15926934.94               .
       5303060.3     15927271.26               .
      5302866.27     15927426.51               .
      5302523.46     15927523.52               .
Storage Area Type= 1
Storage Area Vol Elev= 7
   29.53       0   32.81    .501   36.09     5.4   39.37  29.399   42.65      94
   45.93   188.4   49.21     298

Storage Area=c04             ,5306835.7277512,15925985.4796845
Storage Area Surface Line= 18
 5305915.946383415926025.7888281               .
 5305948.926591815926197.2859118               .
 5306443.629717915926250.0542453               .
 5306786.623885315926414.9552873               .
 5306991.101177415926428.1473707               .
 5307188.982427915926375.3790372               .
 5307347.2874282 15926256.650287               .
 5307459.420136815926058.7690365               .
 5307650.705345615925709.1788274               .
  5307809.01034615925603.6421605               .
 5307716.665762415925517.8936186               .
 5307386.863678315925709.1788274               .
 5307314.3072198 15925801.523411               .
 5306944.928885715925715.7748691               .
 5306324.900967615925814.7154943               .
 5305988.502841815925794.9273693               .
 5305909.350341715926032.3848698               .
 5305915.946383415926032.3848698               .
Storage Area Type= 1
Storage Area Vol Elev= 7
   29.51       0   32.79     .02   36.07    1.79   39.34   24.91   42.62   91.88
    45.9  171.72   49.18  254.33

Storage Area=c03             ,5306089.323255,15927300.7214444
Storage Area Surface Line= 6
 5305052.469140615927910.7965566               .
  5305774.710529 15926712.532435               .
 5305971.685453115926646.8741269               .
 5306726.755995615927336.2863613               .
 5307941.434694215927287.0426303               .
 5305068.883717615927910.7965566               .
Storage Area Type= 1
Storage Area Vol Elev= 7
   29.51       0   32.79     .06   36.07    2.31   39.34   35.93   42.62  119.25
    45.9  205.83   49.18  293.39

Storage Area=c05             ,5307855.8443998,15926338.5145731
Storage Area Surface Line= 14
 5306020.929184215926597.6303959               .
 5306004.514607215926466.3137798               .
 5306940.1454967  15926794.60532               .
 5307448.997383915926630.4595499               .
 5307859.361809215926285.7534327               .
 5308056.336733315925858.9744305               .
 5308417.457427515925629.1703524               .
 5309238.186277915925382.9516972               .
  5309320.25916315925661.9995064               .
 5309615.721549115925629.1703524               .
 5310140.988013415926696.1178579               .
 5308121.995041315927237.7988992               .
 5306808.828880615927270.6280533               .
 5305988.100030115926597.6303959               .
Storage Area Type= 1
Storage Area Vol Elev= 8
   26.23       0   29.51     .01   32.79     .65   36.07    9.08   39.34   79.84
   42.62  273.08    45.9  483.89   49.18  695.92

Storage Area=c07             ,5310996.7346282,15925111.564024
Storage Area Surface Line= 15
 5310239.475475515926646.8741269               .
 5313276.172222215925826.1452765               .
 5312865.8077969 15925005.416426               .
 5312488.2725257 15925071.074734               .
 5312258.468447615923905.6397664               .
 5312028.664369515923823.5668814               .
 5311585.470790215924135.4438445               .
 5311027.375171915924233.9313066               .
 5310748.327362815924496.5645387               .
 5310075.329705415925120.3184651               .
 5309697.794434215925317.2933892               .
   5309336.6737415925350.1225432               .
  5309402.33204815925579.9266213               .
 5309697.794434215925530.6828903               .
 5310223.060898515926630.4595499               .
Storage Area Type= 1
Storage Area Vol Elev= 8
   26.23       0   29.51     .16   32.79    1.75   36.07   12.66   39.34  149.45
   42.62   536.3    45.9  982.51   49.18 1433.37

Storage Area=c06             ,5308365.4779336,15925210.5986386
Storage Area Surface Line= 6
 5307990.678425215925465.0245823               .
 5309106.869661915925087.4893111               .
 5308959.138468815924660.7103088               .
 5308105.580464315925136.7330421               .
 5308007.093002315925481.4391593               .
 5308023.507579315925432.1954282               .
Storage Area Type= 1
Storage Area Vol Elev= 6
   32.79       0   36.07     .03   39.34    1.94   42.62   13.13    45.9   32.33
   49.18   54.57

Storage Area=c08             ,5310112.2625037,15924421.3310608
Storage Area Surface Line= 12
 5309254.6008549 15925021.831003               .
 5309106.869661915924611.4665778               .
 5309763.452742215924496.5645387               .
 5310009.671397415924398.0770767               .
 5310699.083631715923938.4689204               .
 5311404.910443115923708.6648423               .
 5311404.910443115923839.9814584               .
 5310813.985670815923954.8834974               .
 5310223.060898515924398.0770767               .
 5309812.696473315924742.7831939               .
 5309632.1361262 15924939.758118               .
 5309221.7717009 15925005.416426               .
Storage Area Type= 1
Storage Area Vol Elev= 6
   32.79       0   36.07      .3   39.34    8.76   42.62   38.33    45.9   79.44
   49.18  123.34

Storage Area=c10             ,5312442.0132632,15923355.0053195
Storage Area Surface Line= 11
 5311470.568751215923790.7377273               .
 5311372.081289115923462.4461872               .
 5311864.518599415923413.2024561               .
 5313998.413610615922395.4986816               .
 5313899.926148515922723.7902218               .
 5313423.9034152 15923134.154647               .
 5313095.611875115923528.1044952               .
 5312537.516256815923577.3482262               .
 5312045.078946515923495.2753412               .
 5311716.787406315923593.7628032               .
 5311437.739597115923790.7377273               .
Storage Area Type= 1
Storage Area Vol Elev= 6
   32.79       0   36.07     .78   39.34   19.64   42.62  113.99    45.9  244.47
   49.18  386.78

Storage Area=c09             ,5313260.3485267,15924621.4795247
Storage Area Surface Line= 12
 5313408.079722415925749.9817141               .
 5312964.886135315924929.2528491               .
 5312570.9362801 15924978.496581               .
 5312341.132197815923960.7927883               .
 5312570.936280115924026.4510975               .
 5312817.154939615923911.5490564               .
 5313243.933949415923878.7199018               .
 5313900.517041515923254.9659643               .
 5313670.712959215923993.6219429               .
 5314113.9065464   15925470.9339               .
 5314130.321123715925536.5922092               .
 5313391.665145115925766.3962914               .
Storage Area Type= 1
Storage Area Vol Elev= 6
   32.79       0   36.07    1.41   39.34   34.59   42.62   131.2    45.9  242.58
   49.18   357.4

Storage Area=c11             ,5314710.3027932,15924256.2551858
Storage Area Surface Line= 6
  5314245.22310315925487.3484834               .
 5313785.614938615923977.2073717               .
 5314064.662752715923107.2347747               .
 5315509.145555215922598.3828784               .
 5316428.3618841 15924863.594546               .
 5314228.808525715925503.7630607               .
Storage Area Type= 1
Storage Area Vol Elev= 6
   32.79       0   36.07     .77   39.34   90.53   42.62  437.85    45.9  841.43
   49.18 1253.23

Storage Area=c13             ,5317192.8120543,15922662.8687321
Storage Area Surface Line= 14
 5316576.092935715924830.7654057               .
 5315574.803720315922549.1391608               .
  5315886.68068915922401.4079651               .
 5316444.776317315922434.2371197               .
 5317019.286522815922319.3350786               .
 5317216.261450515922007.4581098               .
 5317314.7489143 15921744.824873               .
 5317741.527924115921662.7519865               .
 5318201.136088515921843.3123368               .
 5318365.281861515921941.7998006               .
 5318069.819470115922188.0184601               .
  5317790.77165615922188.0184601               .
 5317971.332006315924354.7426639               .
 5316526.849203815924814.3508284               .
Storage Area Type= 1
Storage Area Vol Elev= 6
   32.79       0   36.07    4.47   39.34  138.62   42.62  524.26    45.9  981.89
   49.18 1445.79

Storage Area=c15             ,5319263.606797,15922955.0269016
Storage Area Surface Line= 11
 5318069.819356915924338.3280979               .
 5317905.673583915922302.9205125               .
 5318168.306820715922302.9205125               .
 5318496.598366715921991.0435438               .
 5319990.3249011 15922220.847626               .
 5320449.933065615922138.7747395               .
 5320696.151725115922319.3350898               .
 5320712.566302415923271.3805733               .
 5319776.935396215923386.2826144               .
 5319579.9604686 15923911.549088               .
 5318053.404779615924321.9135205               .
Storage Area Type= 1
Storage Area Vol Elev= 7
   29.51       0   32.79     .19   36.07   11.47   39.34  125.65   42.62  578.51
    45.9 1141.25   49.18 1713.09

Storage Area=c12             ,5314219.4284379,15922073.1164374
Storage Area Surface Line= 7
 5314064.662423315922680.4557976               .
 5314163.149887115922204.4330558               .
 5314081.077000615921252.3875723               .
  5314212.39361915920924.0960263               .
  5314540.68516515922122.3601693               .
 5314409.3685466 15922647.626643               .
 5314064.662423315922680.4557976               .
Storage Area Type= 1
Storage Area Vol Elev= 6
   32.79       0   36.07     .12   39.34    2.47   42.62   11.57    45.9   30.71
   49.18   60.16

Storage Area=c14             ,5314728.2802622,15921901.9358527
Storage Area Surface Line= 7
 5314589.928824915922581.9683409               .
 5314967.464102815922483.4808771               .
 5315377.828535415922302.9205268               .
 5314557.099670315920530.1461782               .
 5314343.710165415920825.6085697               .
 5314688.4162887  15922040.28729               .
 5314573.514247615922549.1391863               .
Storage Area Type= 1
Storage Area Vol Elev= 6
   32.79       0   36.07     .94   39.34    8.39   42.62    24.4    45.9   58.94
   49.18   114.1

Storage Area=c20             ,5317052.9359225,15921422.278477
Storage Area Surface Line= 20
 5315459.901195415922204.4330854               .
 5315377.828308915922023.8727351               .
 5316050.8259782 15921580.679148               .
 5316346.288369715921515.0208388               .
 5316264.215483215920497.3170461               .
 5316477.6049881 15920218.269232               .
 5317757.942017615920185.4400774               .
 5318365.281377715920595.8045099               .
  5319087.52277915920366.0004277               .
 5319186.010242815921400.1187977               .
 5318906.962428715921728.4103437               .
 5318627.914614615921711.9957664               .
 5318102.648140915921400.1187977               .
 5317478.894203515921334.4604885               .
 5317035.700616315921465.7771069               .
 5316773.067379515921892.5561167               .
 5316576.092451915922089.5310443               .
 5316017.996823615921974.6290032               .
 5315706.1198549 15922073.116467               .
 5315459.901195415922188.0185081               .
Storage Area Type= 1
Storage Area Vol Elev= 7
   29.51       0   32.79     .07   36.07    3.85   39.34   35.96   42.62  169.64
    45.9   392.3   49.18  639.18

Storage Area=c18             ,5315753.5396523,15921046.2934739
Storage Area Surface Line= 9
 5315328.584484315921892.5561259               .
 5314967.463783715921203.1438792               .
 5315591.217721215920612.2190964               .
 5315952.338421815920333.1712823               .
 5316313.459122415920234.6838185               .
 5316132.8987721 15920480.902478               .
 5316231.386235915921350.8750749               .
 5315968.752999115921416.5333841               .
 5315295.755329715921892.5561259               .
Storage Area Type= 1
Storage Area Vol Elev= 6
   32.79       0   36.07     .86   39.34   21.98   42.62  103.71    45.9  211.34
   49.18  319.97

Storage Area=c16             ,5315642.2852023,15920189.0877796
Storage Area Surface Line= 9
 5314934.634536515920989.7543835               .
  5314639.172145 15920415.244178               .
 5315689.705092315920333.1712914               .
 5315919.509174515918921.5176435               .
 5316494.019380115919512.4424264               .
 5316444.775648215920021.2943227               .
 5315952.338329115920152.6109411               .
 5315755.363401515920349.5858687               .
 5314951.049113815921006.1689608               .
Storage Area Type= 1
Storage Area Vol Elev= 6
   32.79       0   36.07     .39   39.34    8.82   42.62    87.1    45.9  217.78
   49.18  357.74