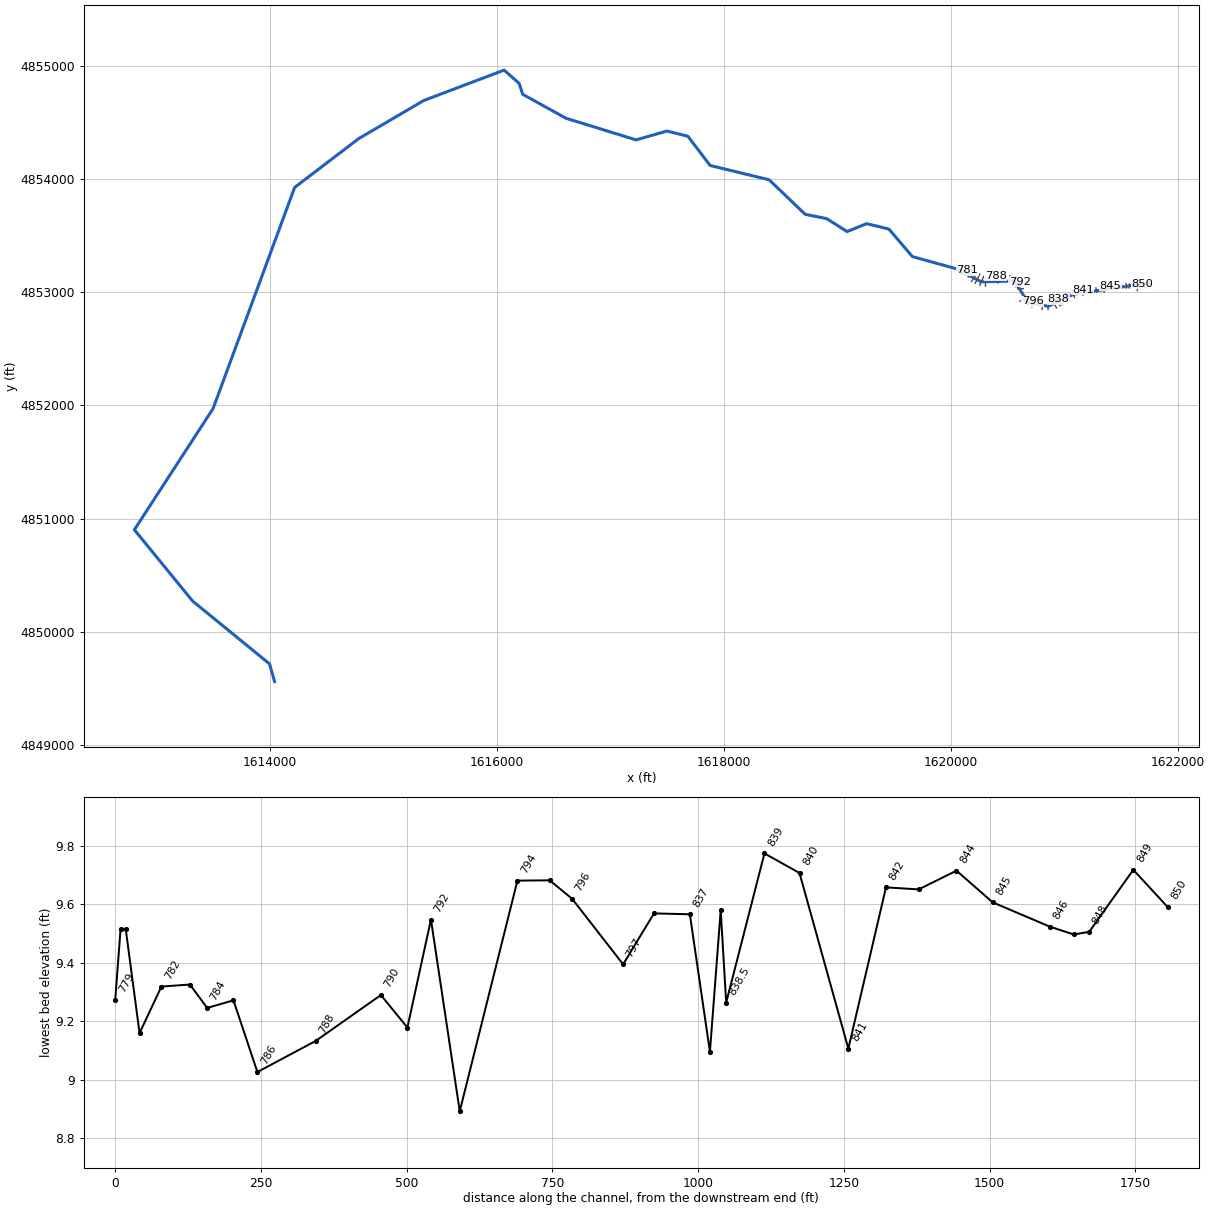
HEC-RAS study ozz_def.prj: ozzeri

--- ozz_def.g04 (geometry) --- (continued)

Storage Area=c22             ,5319689.3914447,15921717.7674938
Storage Area Surface Line= 6
 5319136.767342315921695.8813908               .
 5319366.571424515921449.6627312               .
 5320138.056557615921613.8085042               .
 5320302.202330715921909.2708957               .
 5320088.812825715921942.1000503               .
 5319103.938187715921695.8813908               .
Storage Area Type= 1
Storage Area Vol Elev= 6
   32.79       0   36.07     .55   39.34   16.33   42.62   54.15    45.9    93.2
   49.18  132.35

Connection=hc_02_04        ,5305765.6462295,15926031.5608869
Connection Line= 4
 5305924.876327915925950.6197587 5305726.805428815926044.8947128
 5305509.816039415926085.9467595 5305525.754123815926079.9697853
Connection Up SA=c04
Connection Dn SA=c02
Conn Weir Coef=3
Conn Weir Is Ogee= 0
Conn Weir SE= 6
       0   49.18      10   49.18      10   43.93     239   43.93     239   49.18
     249   49.18
Connection Culv=1,.1,,10,.035,1,1,1,1,40,40, 1 ,Culvert #1  , 0 ,
     100     100
Conn Culv Bottom n=.035
Conn HTab HWMax=50

Connection=hc_01_03        ,5305617.0666995,15926851.5770318
Connection Line= 4
 5305677.633682815926873.5912814 5305676.473376815926872.8918591
 5305558.552983115926830.7774328 5305555.606755515926829.0475538
Connection Up SA=c03
Connection Dn SA=c01
Conn Weir WD=10
Conn Weir Coef=3
Conn Weir Is Ogee= 0
Conn Weir SE= 6
       0   49.18      10   49.18      10   40.66   501.8   40.66   501.8   49.18
   511.8   49.18
Conn HTab HWMax=50

Connection=hc_03_05        ,5306205.094611,15926812.1797886
Connection Line= 4
 5306232.870135915926798.3418187   5306240.8066915926788.6630064
 5306173.423607815926830.7774328 5306173.278010415926830.9368966
Connection Up SA=c05
Connection Dn SA=c03
Conn Weir WD=10
Conn Weir Coef=3
Conn Weir Is Ogee= 0
Conn Weir SE= 6
       0   49.18      10   49.18      10   39.67  993.61   39.67  993.61   49.18
 1003.61   49.18
Conn HTab HWMax=50

Connection=hc_01_05        ,5305818.9335043,15926549.0864291
Connection Line= 4
   5306011.2810115926520.4470106  5306021.81167315926519.1306777
   5305617.5131815926578.0908746 5305625.128154315926578.6771533
Connection Up SA=c05
Connection Dn SA=c01
Conn Weir WD=10
Conn Weir Coef=3
Conn Weir Is Ogee= 0
Conn Weir SE= 6
       0   49.18      10   49.18      10   43.28   75.57   43.28   75.57   49.18
   85.57   49.18
Conn HTab HWMax=50

Connection=hc_05_07        ,5309325.2871833,15925478.866708
Connection Line= 4
 5309369.182064715925463.9020157 5309380.706467815925460.6092557
 5309279.631844515925494.3007968 5309271.628356415925496.6547639
Connection Up SA=c07
Connection Dn SA=c05
Conn Weir WD=10
Conn Weir Coef=3
Conn Weir Is Ogee= 0
Conn Weir SE= 6
       0   49.18      10   49.18      10   39.67     829   39.67     829   49.18
     839   49.18
Conn HTab HWMax=50

Connection=hc_07_09        ,5313058.990266,15925235.5722775
Connection Line= 4
 5313121.942458315925220.0976842 5313128.890413315925216.3455828
 5312994.124248915925250.0371239 5312991.003943615925255.8087193
Connection Up SA=c09
Connection Dn SA=c07
Conn Weir WD=10
Conn Weir Coef=3
Conn Weir Is Ogee= 0
Conn Weir SE= 6
       0   49.18      10   49.18      10   35.08     665   35.08     665   49.18
     675   49.18
Conn HTab HWMax=50

Connection=hc_09_11        ,5313774.2597862,15924142.1406337
Connection Line= 4
 5313831.077825715924126.5856521 5313836.112329815924125.0534005
 5313709.769050815924158.7449416 5313720.079938615924158.1785408
Connection Up SA=c11
Connection Dn SA=c09
Conn Weir WD=10
Conn Weir Coef=3
Conn Weir Is Ogee= 0
Conn Weir SE= 6
       0   49.18      10   49.18      10   39.34      92   39.34      92   49.18
     102   49.18
Conn HTab HWMax=50

Connection=hc_11_13        ,5315803.2363738,15923205.073318
Connection Line= 4
 5315851.878836815923180.5068101 5315849.181909615923181.6902502
 5315748.107286315923232.2275618 5315763.777462515923225.8686497
Connection Up SA=c13
Connection Dn SA=c11
Conn Weir WD=10
Conn Weir Coef=3
Conn Weir Is Ogee= 0
Conn Weir SE= 6
       0   49.18      10   49.18      10   41.31     993   41.31     993   49.18
    1003   49.18
Conn HTab HWMax=50

Connection=hc_13_15        ,5318221.6707179,15922147.0921544
Connection Line= 4
 5318269.969868515922206.3409408 5318281.6402737 15922218.625686
 5318155.296994615922067.0137512 5318179.775734915922096.3882395
Connection Up SA=c15
Connection Dn SA=c13
Conn Weir WD=10
Conn Weir Coef=3
Conn Weir Is Ogee= 0
Conn Weir SE= 6
       0   49.18      10   49.18      10   34.43     993   34.43     993   49.18
    1003   49.18
Conn HTab HWMax=50

Connection=hc_06_08        ,5309106.0375957,15924848.7771149
Connection Line= 4
 5309183.043855515924823.0614604 5309180.0122542 15924824.152878
 5309028.400319415924874.6901896 5309032.693953615924873.2039316
Connection Up SA=c08
Connection Dn SA=c06
Conn Weir WD=10
Conn Weir Coef=3
Conn Weir Is Ogee= 0
Conn Weir SE= 6
       0   49.18      10   49.18      10   42.62      43   42.62      43   49.18
      53   49.18
Conn HTab HWMax=50

Connection=hc_08_10        ,5311428.1777111,15923737.918387
Connection Line= 4
 5311449.955158315923722.0257432 5311454.191277415923720.7549075
 5311403.653965715923754.4464486 5311404.910443115923754.4464486
Connection Up SA=c10
Connection Dn SA=c08
Conn Weir WD=10
Conn Weir Coef=3
Conn Weir Is Ogee= 0
Conn Weir SE= 6
       0   49.18      10   49.18      10   42.62      43   42.62      43   49.18
      53   49.18
Conn HTab HWMax=50

Connection=hc_10_12        ,5314026.5188721,15922525.8401623
Connection Line= 4
 5314099.483778615922512.1519791 5314105.644658515922513.4266705
 5313945.609838415922538.6953263 5313955.337213115922539.0866732
Connection Up SA=c12
Connection Dn SA=c10
Conn Weir WD=10
Conn Weir Coef=3
Conn Weir Is Ogee= 0
Conn Weir SE= 6
       0   49.18      10   49.18      10   40.98      43   40.98      43   49.18
      53   49.18
Conn HTab HWMax=50

Connection=hc_16_18        ,5315427.1479883,15920683.9294089
Connection Line= 4
 5315406.521840515920634.3544983  5315402.52837315920629.4626547
 5315444.6427993 15920730.537278 5315454.898940315920741.3632046
Connection Up SA=c16
Connection Dn SA=c18
Conn Weir WD=10
Conn Weir Coef=3
Conn Weir Is Ogee= 0
Conn Weir SE= 6
       0   49.18      10   49.18      10   41.97     666   41.97     666   49.18
     676   49.18
Conn HTab HWMax=50

Connection=hc_18_20        ,5315801.6977717,15921643.0274943
Connection Line= 4
 5315747.840450415921572.7885334 5315747.866669115921572.8258051
 5315857.364177615921716.0148547 5315853.719789815921710.4807843
Connection Up SA=c18
Connection Dn SA=c20
Conn Weir WD=10
Conn Weir Coef=3
Conn Weir Is Ogee= 0
Conn Weir SE= 6
       0   49.18      10   49.18      10   41.31     273   41.31     273   49.18
     283   49.18
Conn HTab HWMax=50

Connection=hc_14_20        ,5315342.9698449,15922083.6579809
Connection Line= 4
 5315287.910655315922108.6979363 5315275.246726715922114.5608581
 5315414.365758115922051.1389467 5315394.356239515922060.2341825
Connection Up SA=c14
Connection Dn SA=c20
Conn Weir WD=10
Conn Weir Coef=3
Conn Weir Is Ogee= 0
Conn Weir SE= 6
       0   49.18      10   49.18      10   33.77      76   33.77      76   49.18
      86   49.18
Conn HTab HWMax=50

Connection=hc_14_18        ,5315169.1134249,15921698.5175615
Connection Line= 4
 5315113.396569715921731.7474552 5315095.210333115921740.1669942
 5315254.788045615921650.1487974 5315213.058751315921672.0069992
Connection Up SA=c14
Connection Dn SA=c18
Conn Weir WD=10
Conn Weir Coef=3
Conn Weir Is Ogee= 0
Conn Weir SE= 6
       0   49.18      10   49.18      10   36.07     174   36.07     174   49.18
     184   49.18
Conn HTab HWMax=50

Connection=hc_14_16        ,5314805.435288,15920887.3562974
Connection Line= 4
 5314743.216720815920932.1589966 5314724.9082054 15920940.635164
 5314892.669390315920830.1582861 5314860.946835615920846.4727429
Connection Up SA=c14
Connection Dn SA=c16
Conn Weir WD=10
Conn Weir Coef=3
Conn Weir Is Ogee= 0
Conn Weir SE= 6
       0   49.18      10   49.18      10   36.07     174   36.07     174   49.18
     184   49.18
Conn HTab HWMax=50

Chan Stop Cuts=-1

--- ozz_def.g01 (geometry) ---

Geom Title=studio_ozz
Version=Version 3.0.1  Mar 2001

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
River Reach=OZZERI          ,tronco_1

--- ozz_def.g02 (geometry) ---

Geom Title=studio_ozz_mod
Version=Version 3.0.1  Mar 2001

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
River Reach=OZZERI          ,tronco_1
Reach XY= 30
      1621737.73      4853081.72      1621077.53      4852982.57
      1620854.84      4852876.29      1620679.28      4852906.77
      1620557.84      4853099.24      1620266.19      4853092.11
      1620045.62       4853207.6       1619658.9      4853315.14
      1619452.34      4853558.01      1619256.33        4853606.
      1619083.93      4853536.01       1618903.9      4853650.49
      1618714.74       4853688.6      1618397.51      4853993.23
      1617877.88      4854119.85      1617682.12      4854377.78
      1617497.89      4854423.77      1617225.88      4854345.75
      1616607.94      4854537.07      1616227.23      4854748.73
      1616196.06      4854844.88      1616064.04      4854962.02
      1615357.05      4854693.79      1614782.97      4854356.77
      1614219.36      4853925.94       1613501.3       4851973.5
      1612807.86      4850902.43      1613320.95      4850272.55
      1613997.96      4849717.94      1614042.97      4849561.47

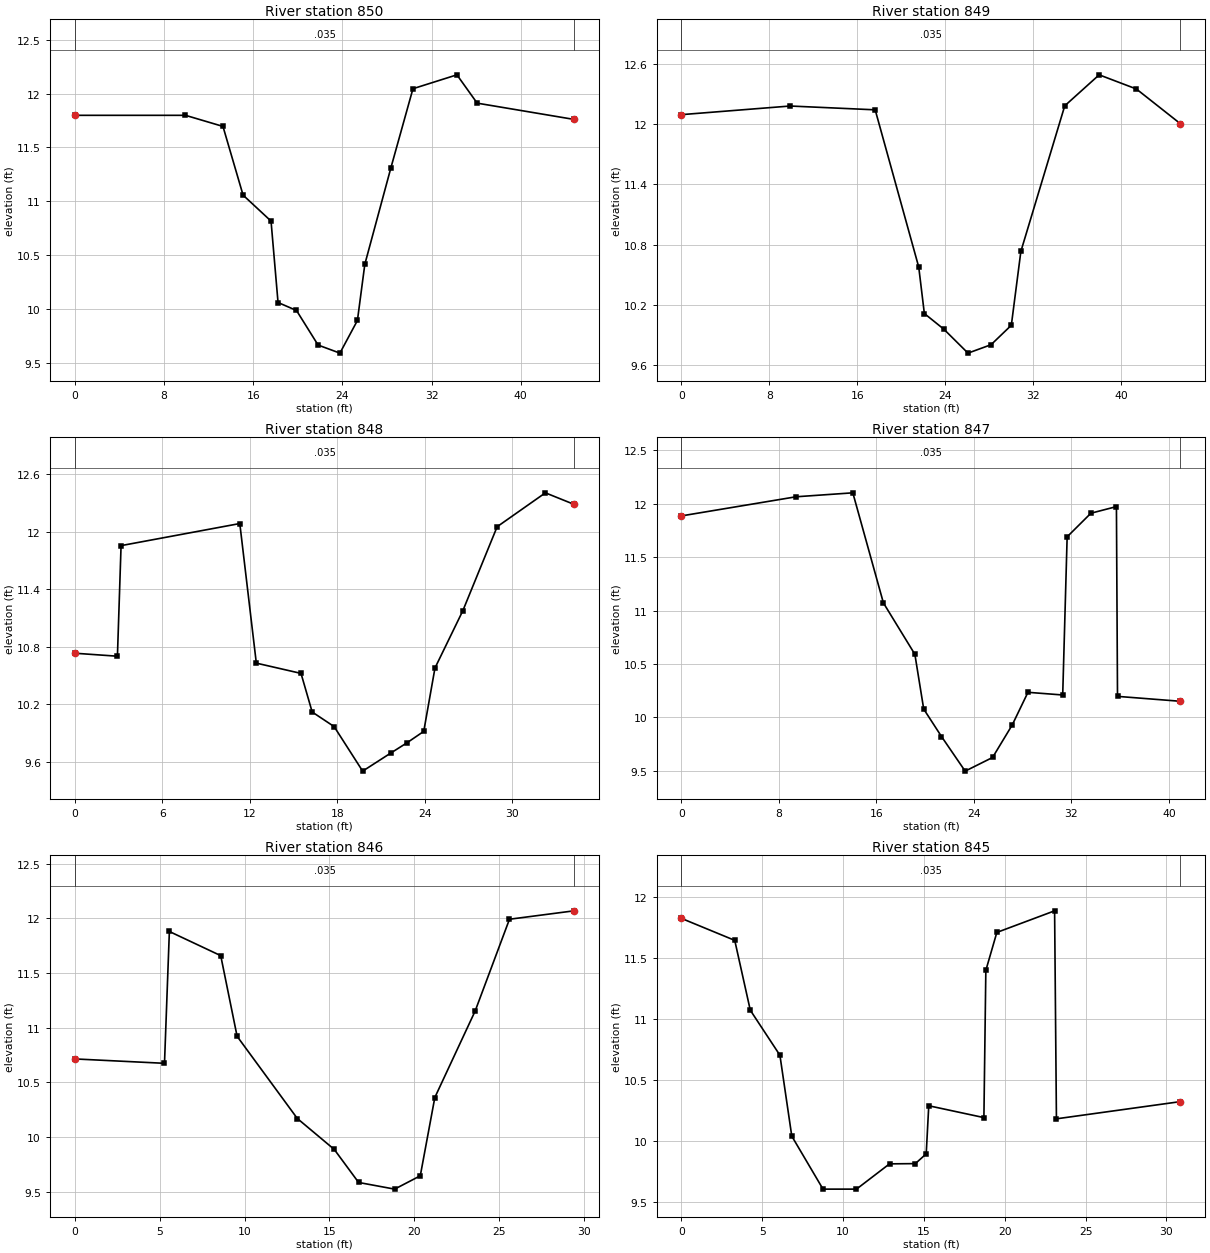
Type RM Length L Ch R = 1 ,850     ,58.8,58.8,58.8
XS GIS Cut Line= 4
      1621711.17      4853038.08        1621685.      4853074.38
  1621684.999942 4853074.3800805 1621684.9981893 4853074.3825132
#Sta/Elev= 16
       0  11.798   9.915  11.798  13.277  11.695  15.081  11.057   17.59  10.816
  18.218   10.06  19.874   9.986  21.811   9.665   23.77    9.59   25.34   9.893
  26.005  10.415  28.342   11.31  30.323  12.045  34.268  12.174  36.085  11.911
  44.773   11.76
#Mann= 3 , 0 , 0
       0    .035       0       0    .035       0  44.773    .035       0
Bank Sta=0,44.773
XS Rating Curve= 0
Exp/Cntr=.3,.1

Type RM Length L Ch R = 1 ,849     ,75.65,75.65,75.65
XS GIS Cut Line= 2
       1621639.9      4853014.01  1621642.329941  4853059.188903
#Sta/Elev= 14
       0  12.095   9.884  12.181  17.617  12.143  21.578  10.575  22.088  10.112
  23.868   9.955  26.057   9.717  28.155   9.801  29.998   9.995  30.865  10.731
  34.856  12.183  37.986  12.492  41.366  12.351  45.379  12.004
#Mann= 3 , 0 , 0
       0    .035       0       0    .035       0  45.379    .035       0
Bank Sta=0,45.379
XS Rating Curve= 0
Exp/Cntr=.3,.1

Type RM Length L Ch R = 1 ,848     ,26.45,26.45,26.45
XS GIS Cut Line= 2
      1621567.25      4853037.89 1621570.4896093 4853071.7359179
#Sta/Elev= 17
       0  10.733   2.913  10.702   3.163  11.854  11.314  12.084  12.448   10.63
  15.516  10.523  16.282  10.121  17.789   9.969  19.748   9.505  21.675   9.693
    22.8   9.801  23.941   9.919  24.712  10.579  26.628  11.177   28.98  12.051
  32.292  12.404  34.256  12.284
#Mann= 3 , 0 , 0
       0    .035       0       0    .035       0  34.256    .035       0
Bank Sta=0,34.256
XS Rating Curve= 0
Exp/Cntr=.3,.1

Type RM Length L Ch R = 1 ,847     ,41.47,41.47,41.47
XS GIS Cut Line= 3
      1621541.88       4853037.1      1621541.11      4853077.97
 1621541.1099454 4853077.9728987
#Sta/Elev= 17
       0  11.886   9.401  12.065   14.06  12.102   16.57  11.071  19.151   10.59
  19.877  10.077  21.336    9.82  23.278   9.496  25.528   9.624  27.142   9.929
   28.43  10.234  31.281  10.209  31.645   11.69  33.594  11.911  35.689  11.973
  35.777  10.196  40.943   10.15
#Mann= 3 , 0 , 0
       0    .035       0       0    .035       0  40.943    .035       0
Bank Sta=0,40.943
XS Rating Curve= 0
Exp/Cntr=.3,.1

Type RM Length L Ch R = 1 ,846     ,97.85,97.85,97.85
XS GIS Cut Line= 2
      1621502.64      4853038.49 1621499.2905587  4853067.675132
#Sta/Elev= 14
       0  10.714   5.276  10.674   5.563   11.88   8.591  11.659   9.556  10.921
  13.107  10.169  15.284   9.886  16.718   9.584  18.842   9.523  20.354   9.645
  21.211  10.361   23.59  11.153  25.611  11.992  29.415  12.069
#Mann= 3 , 0 , 0
       0    .035       0       0    .035       0  29.415    .035       0
Bank Sta=0,29.415
XS Rating Curve= 0
Exp/Cntr=.3,.1

Type RM Length L Ch R = 1 ,845     ,61.95,61.95,61.95
XS GIS Cut Line= 2
      1621404.92      4853027.46 1621403.6702072  4853058.194904
#Sta/Elev= 17
       0  11.824   3.296  11.644   4.257  11.072    6.09  10.703   6.824   10.04
   8.756   9.606  10.826   9.606  12.869   9.813  14.466   9.815  15.139   9.895
  15.296  10.289  18.707  10.192  18.827  11.398  19.507  11.709   23.08  11.886
  23.193  10.182  30.865  10.323
#Mann= 3 , 0 , 0
       0    .035       0       0    .035       0  30.865    .035       0
Bank Sta=0,30.865
XS Rating Curve= 0
Exp/Cntr=.3,.1

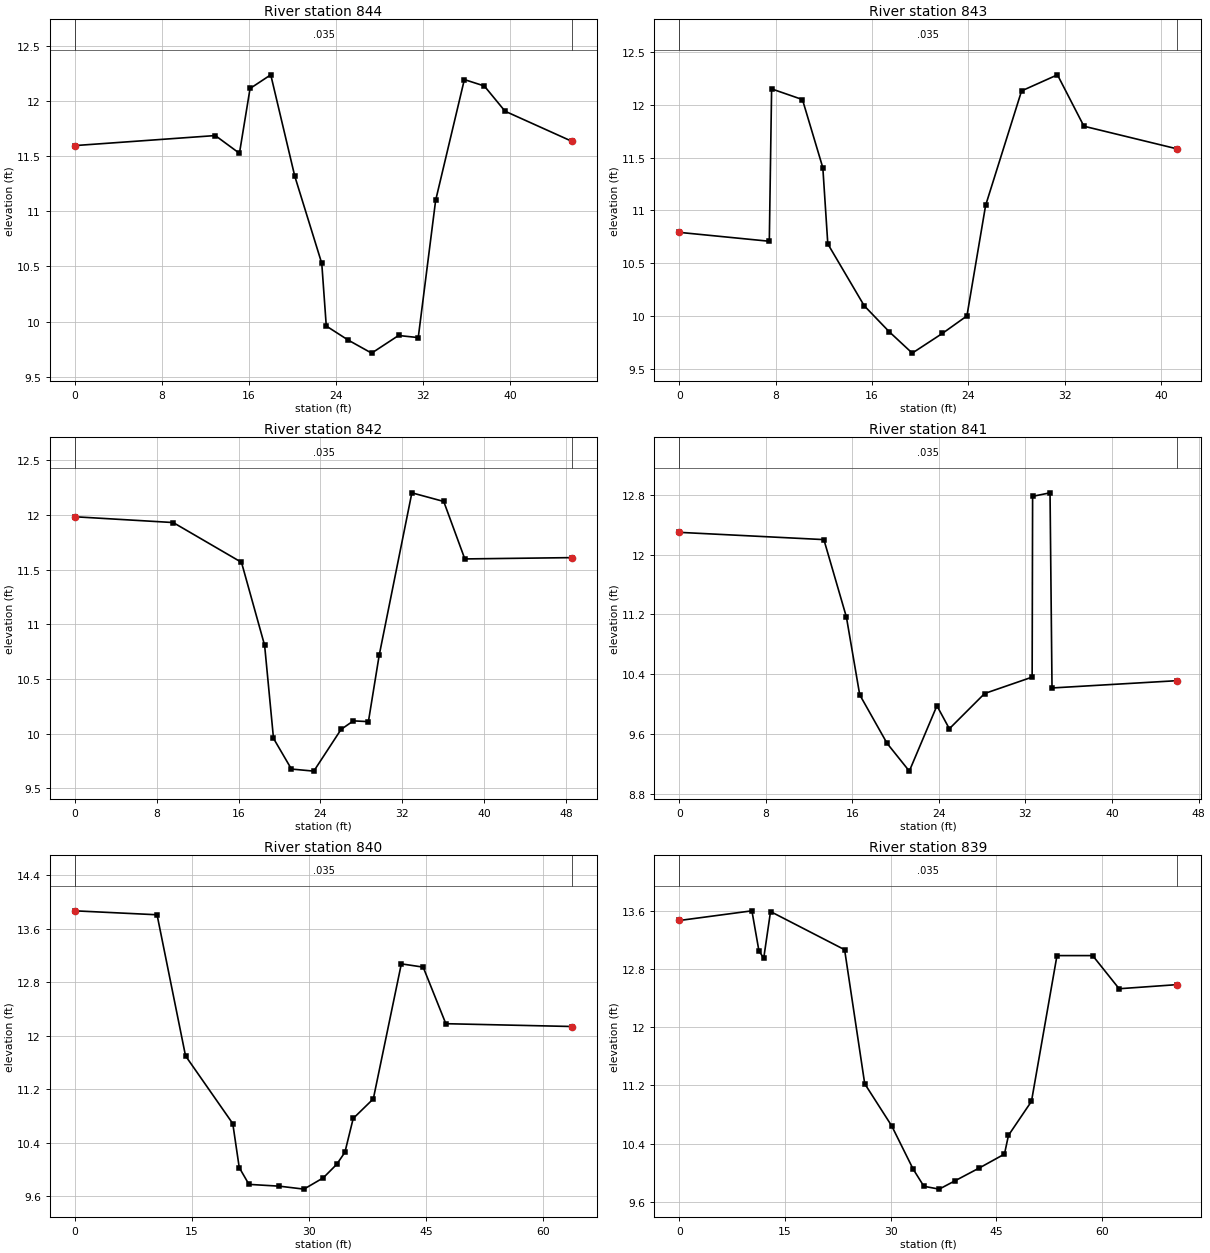
Type RM Length L Ch R = 1 ,844     ,64.8,64.8,64.8
XS GIS Cut Line= 2
      1621348.22      4853001.51 1621339.9703435 4853046.3881316
#Sta/Elev= 17
       0  11.597  12.908  11.688  15.127  11.527  16.103  12.115  18.006  12.239
  20.212   11.32  22.696  10.528   23.11    9.96  25.131   9.832  27.281   9.714
  29.755   9.874  31.566   9.855  33.165    11.1  35.805  12.196  37.637  12.138
  39.545  11.909  45.708  11.635
#Mann= 3 , 0 , 0
       0    .035       0       0    .035       0  45.708    .035       0
Bank Sta=0,45.708
XS Rating Curve= 0
Exp/Cntr=.3,.1

Type RM Length L Ch R = 1 ,843     ,56.1,56.1,56.1
XS GIS Cut Line= 2
      1621284.39      4852998.35 1621275.1904244 4853038.4881483
#Sta/Elev= 16
       0  10.792   7.467  10.708   7.658  12.149  10.218  12.048   11.91  11.403
  12.322  10.683  15.345  10.098  17.414   9.853   19.33    9.65   21.84   9.837
   23.87  10.002  25.421  11.047  28.406   12.13  31.384  12.282  33.581  11.796
  41.268  11.583
#Mann= 3 , 0 , 0
       0    .035       0       0    .035       0  41.268    .035       0
Bank Sta=0,41.268
XS Rating Curve= 0
Exp/Cntr=.3,.1

Type RM Length L Ch R = 1 ,842     ,64.59,64.59,64.59
XS GIS Cut Line= 2
      1621227.82      4852983.93      1621220.32      4853031.92
#Sta/Elev= 15
       0  11.985   9.606  11.932  16.281  11.568  18.542  10.808  19.409   9.957
   21.16   9.676  23.349   9.657  26.015  10.039  27.215  10.117  28.685   10.11
  29.736  10.716  32.932  12.204  36.046  12.125  38.107  11.599   48.59  11.611
#Mann= 3 , 0 , 0
       0    .035       0       0    .035       0   48.59    .035       0
Bank Sta=0,48.59
XS Rating Curve= 0
Exp/Cntr=.3,.1

Type RM Length L Ch R = 1 ,841     ,83.78,83.78,83.78
XS GIS Cut Line= 2
      1621160.89      4852974.87 1621160.7600139  4853020.705102
#Sta/Elev= 14
       0  12.296  13.362  12.199  15.445  11.164  16.675  10.126  19.206   9.477
  21.261   9.106  23.813   9.979  24.962   9.672  28.225  10.143  32.616  10.362
  32.659  12.777   34.27  12.824  34.454  10.217  45.965  10.314
#Mann= 3 , 0 , 0
       0    .035       0       0    .035       0  45.965    .035       0
Bank Sta=0,45.965
XS Rating Curve= 0
Exp/Cntr=.3,.1

Type RM Length L Ch R = 1 ,840     ,60.15,60.15,60.15
XS GIS Cut Line= 2
      1621086.76      4852954.73 1621065.3800346  4853014.659903
#Sta/Elev= 17
       0  13.868  10.525  13.809  14.172  11.699  20.225  10.686  21.053  10.028
  22.298   9.777  26.205    9.75  29.343   9.706  31.819   9.875  33.532  10.076
  34.585  10.256  35.652  10.763  38.229  11.056  41.817  13.075  44.615  13.026
  47.518   12.18   63.69  12.138
#Mann= 3 , 0 , 0
       0    .035       0       0    .035       0   63.69    .035       0
Bank Sta=0,63.69
XS Rating Curve= 0
Exp/Cntr=.3,.1

Type RM Length L Ch R = 1 ,839     ,65.63,65.63,65.63
XS GIS Cut Line= 3
       1621042.3      4852920.91      1621009.79      4852983.32
 1621009.7886113  4852983.322666
#Sta/Elev= 20
       0  13.469  10.298  13.602  11.295  13.051  11.976  12.951  12.941  13.592
  23.454  13.067  26.308  11.223  30.145  10.642  33.173   10.05  34.705   9.812
  36.881   9.773  39.113   9.887  42.591  10.065   46.14  10.255  46.711  10.513
  49.976  10.981  53.596  12.986  58.662  12.986  62.418   12.53  70.563  12.586
#Mann= 3 , 0 , 0
       0    .035       0       0    .035       0  70.563    .035       0
Bank Sta=0,70.563
XS Rating Curve= 0
Exp/Cntr=.3,.1

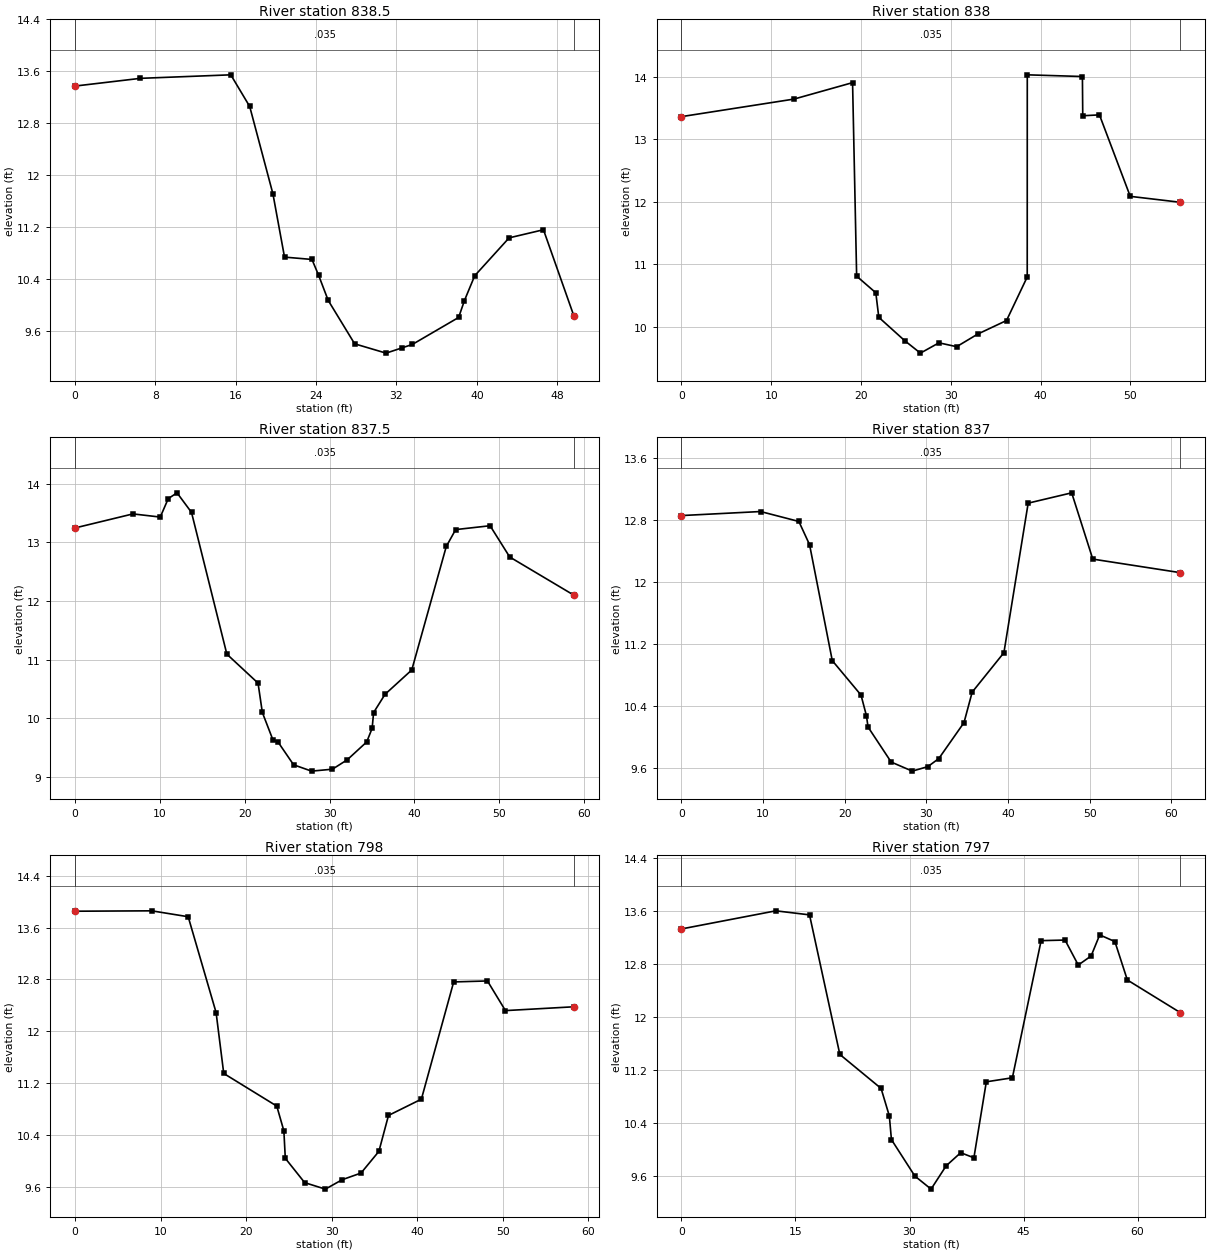
Type RM Length L Ch R = 1 ,838.5   ,9.4,9.4,9.4
XS GIS Cut Line= 3
      1620983.82      4852891.82      1620961.33      4852935.82
 1620961.3294982 4852935.8209817
#Sta/Elev= 19
       0  13.371   6.516   13.49  15.508  13.544  17.391  13.057  19.705  11.711
  20.856   10.74  23.588  10.704  24.247  10.462  25.204  10.074  27.838   9.406
  30.964   9.263  32.517   9.342  33.584   9.397  38.188   9.812  38.766  10.072
  39.787  10.453  43.211  11.036  46.631  11.161  49.671    9.83
#Mann= 3 , 0 , 0
       0    .035       0       0    .035       0  49.671    .035       0
Bank Sta=0,49.671
XS Rating Curve= 0
Exp/Cntr=.3,.1

Type RM Length L Ch R = 1 ,838     ,18.51,18.51,18.51
XS GIS Cut Line= 2
      1620975.23      4852890.33 1620946.3383299 4852936.7050883
#Sta/Elev= 19
       0  13.364  12.542  13.645  19.061  13.908  19.515  10.811   21.65  10.545
  21.983  10.152  24.848   9.781  26.617   9.579  28.686   9.744  30.654   9.682
  33.005   9.884  36.211  10.101  38.517  10.798  38.523  14.033  44.664  14.006
  44.702  13.378  46.563  13.392  49.993  12.088  55.587  11.993
#Mann= 3 , 0 , 0
       0    .035       0       0    .035       0  55.587    .035       0
Bank Sta=0,55.587
XS Rating Curve= 0
Exp/Cntr=.3,.1

Type RM Length L Ch R = 1 ,837.5   ,34.4,34.4,34.4
XS GIS Cut Line= 3
      1620959.81       4852879.7      1620928.26      4852929.13
 1620928.2599466 4852929.1300836
#Sta/Elev= 25
       0  13.248    6.83  13.488  10.048  13.434  10.989  13.749  12.023  13.848
  13.729  13.514  17.894  11.093   21.57  10.598  22.076  10.097  23.319    9.63
  23.912   9.595   25.76   9.203  27.877   9.095  30.335   9.128  32.086   9.289
  34.371   9.593  35.014   9.826  35.186  10.095  36.535  10.407  39.685  10.823
  43.751  12.932  44.855   13.22  48.912  13.286  51.226  12.752    58.8  12.099
#Mann= 3 , 0 , 0
       0    .035       0       0    .035       0    58.8    .035       0
Bank Sta=0,58.8
XS Rating Curve= 0
Exp/Cntr=.3,.1

Type RM Length L Ch R = 1 ,837     ,61.54,61.54,61.54
XS GIS Cut Line= 3
      1620927.75       4852861.5      1620900.54       4852916.2
 1620900.5395549 4852916.2008949
#Sta/Elev= 19
       0  12.858   9.689   12.91  14.378  12.782  15.688  12.483   18.47  10.989
   21.99  10.545  22.651   10.28  22.852  10.133  25.683   9.682  28.265   9.565
  30.174   9.623  31.516   9.727    34.6   10.19  35.603  10.583  39.488  11.091
   42.46  13.018   47.79  13.151  50.373  12.297  61.111  12.122
#Mann= 3 , 0 , 0
       0    .035       0       0    .035       0  61.111    .035       0
Bank Sta=0,61.111
XS Rating Curve= 0
Exp/Cntr=.3,.1

Type RM Length L Ch R = 1 ,798     ,52.98,52.98,52.98
XS GIS Cut Line= 3
      1620853.37      4852847.09       1620856.3       4852905.3
 1620856.3001962 4852905.3038975
#Sta/Elev= 19
       0  13.852    8.97  13.858   13.23  13.767  16.492   12.29  17.386  11.351
  23.585  10.848  24.414  10.466  24.581  10.043  26.846   9.668  29.263   9.568
  31.228   9.713  33.433   9.816  35.519   10.15  36.641  10.704  40.488  10.955
  44.261  12.762  48.207  12.777  50.311   12.32  58.324  12.379
#Mann= 3 , 0 , 0
       0    .035       0       0    .035       0  58.324    .035       0
Bank Sta=0,58.324
XS Rating Curve= 0
Exp/Cntr=.3,.1

Type RM Length L Ch R = 1 ,797     ,87.49,87.49,87.49
XS GIS Cut Line= 3
      1620801.07      4852848.01      1620803.37      4852913.55
 1620803.3701086 4852913.5530956
#Sta/Elev= 22
       0  13.329  12.412  13.603  16.847  13.542  20.836  11.431   26.26  10.917
  27.345  10.501  27.622  10.143  30.702   9.592  32.834   9.394  34.818   9.746
  36.734   9.945  38.469   9.868  40.104  11.017  43.531  11.078  47.312  13.152
  50.461  13.161  52.198  12.783  53.887   12.92  55.019  13.239  57.016  13.138
  58.656  12.557  65.643  12.062
#Mann= 3 , 0 , 0
       0    .035       0       0    .035       0  65.643    .035       0
Bank Sta=0,65.643
XS Rating Curve= 0
Exp/Cntr=.3,.1

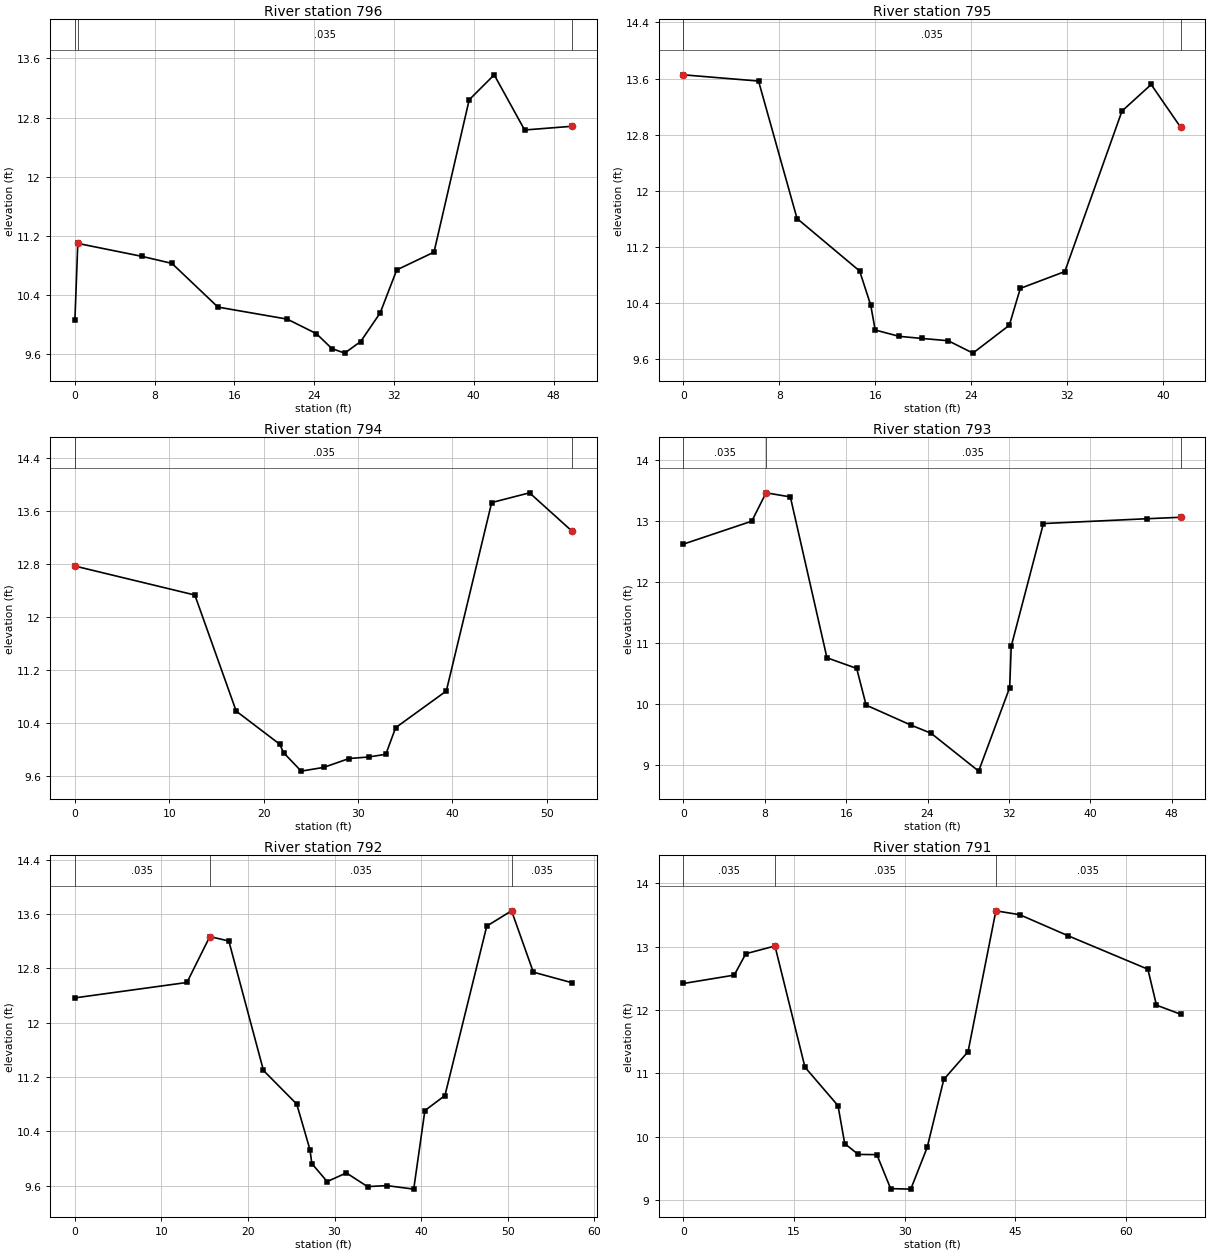
Type RM Length L Ch R = 1 ,796     ,38.51,38.51,38.51
XS GIS Cut Line= 2
      1620711.67      4852871.07 1620719.5993446 4852920.0459519
#Sta/Elev= 17
       0  10.064     .29    11.1   6.721  10.925   9.733   10.83  14.342   10.24
  21.301  10.077  24.219   9.881  25.776   9.679  27.059   9.618  28.663   9.775
  30.617  10.161  32.277  10.742  36.014  10.982  39.545   13.04  42.051  13.377
  45.103  12.632  49.856  12.682
#Mann= 3 , 0 , 0
       0    .035       0     .29    .035       0  49.856    .035       0
Bank Sta=.29,49.856
XS Rating Curve= 0
Exp/Cntr=.3,.1

Type RM Length L Ch R = 1 ,795     ,55.31,55.31,55.31
XS GIS Cut Line= 2
      1620673.78       4852883.3 1620683.2499773 4852923.5999035
#Sta/Elev= 16
       0  13.653   6.262  13.564   9.472  11.602  14.692  10.853  15.616  10.365
  15.989  10.011  17.972   9.921  19.855   9.891  22.075   9.858  24.137   9.681
  27.171  10.079  28.089  10.605  31.799  10.845  36.566  13.136  38.999  13.515
   41.45  12.906
#Mann= 3 , 0 , 0
       0    .035       0       0    .035       0   41.45    .035       0
Bank Sta=0,41.45
XS Rating Curve= 0
Exp/Cntr=.3,.1

Type RM Length L Ch R = 1 ,794     ,98.95,98.95,98.95
XS GIS Cut Line= 2
      1620606.27      4852920.35 1620653.3347179 4852943.7973685
#Sta/Elev= 15
       0  12.772  12.714  12.335  17.097  10.585  21.711  10.086  22.119   9.958
  23.986    9.68  26.368   9.736  29.063    9.87  31.145   9.893  32.959   9.934
  33.998  10.335   39.37  10.888  44.177  13.729   48.19  13.876  52.694  13.298
#Mann= 3 , 0 , 0
       0    .035       0       0    .035       0  52.694    .035       0
Bank Sta=0,52.694
XS Rating Curve= 0
Exp/Cntr=.3,.1

Type RM Length L Ch R = 1 ,793     ,49.41,49.41,49.41
XS GIS Cut Line= 3
       1620587.7       4853028.6      1620635.68      4853032.41
 1620635.6830878 4853032.4102452
#Sta/Elev= 15
       0  12.616   6.719  12.992   8.123  13.457  10.513   13.39  14.112  10.751
  17.036  10.577  17.962   9.975  22.341   9.649  24.345   9.514  29.029   8.892
  32.079  10.262  32.233  10.941  35.396  12.953  45.552  13.032  48.883  13.056
#Mann= 3 , 0 , 0
       0    .035       0   8.123    .035       0  48.883    .035       0
Bank Sta=8.123,48.883
XS Rating Curve= 0
Exp/Cntr=.3,.1

Type RM Length L Ch R = 1 ,792     ,40.36,40.36,40.36
XS GIS Cut Line= 3
      1620567.35      4853049.18      1620606.05      4853091.55
 1620606.0514175  4853091.551552
#Sta/Elev= 19
       0  12.366  12.949  12.593  15.591   13.27  17.787  13.204  21.789  11.296
  25.636    10.8  27.162  10.128  27.378   9.924   29.15   9.658  31.367   9.786
  33.813   9.584  36.046   9.599  39.151   9.547  40.441  10.705  42.756  10.926
  47.592  13.424  50.457  13.649  52.972  12.745  57.442  12.589
#Mann= 3 , 0 , 0
       0    .035       0  15.591    .035       0  50.457    .035       0
Bank Sta=15.591,50.457
XS Rating Curve= 0
Exp/Cntr=.3,.1

Type RM Length L Ch R = 1 ,791     ,45.53,45.53,45.53
XS GIS Cut Line= 2
      1620546.74      4853070.52 1620570.9199644 4853133.2999075
#Sta/Elev= 20
       0  12.418   6.884   12.55   8.455  12.887  12.407  13.009  16.475  11.099
  20.953  10.493   21.86   9.896  23.693   9.725  26.221   9.721  28.086   9.186
   30.82   9.178  33.044   9.836  35.295  10.907  38.584  11.344  42.355  13.563
  45.586  13.502  52.105  13.172   62.96  12.643  64.124  12.077   67.39  11.934
#Mann= 3 , 0 , 0
       0    .035       0  12.407    .035       0  42.355    .035       0
Bank Sta=12.407,42.355
XS Rating Curve= 0
Exp/Cntr=.3,.1

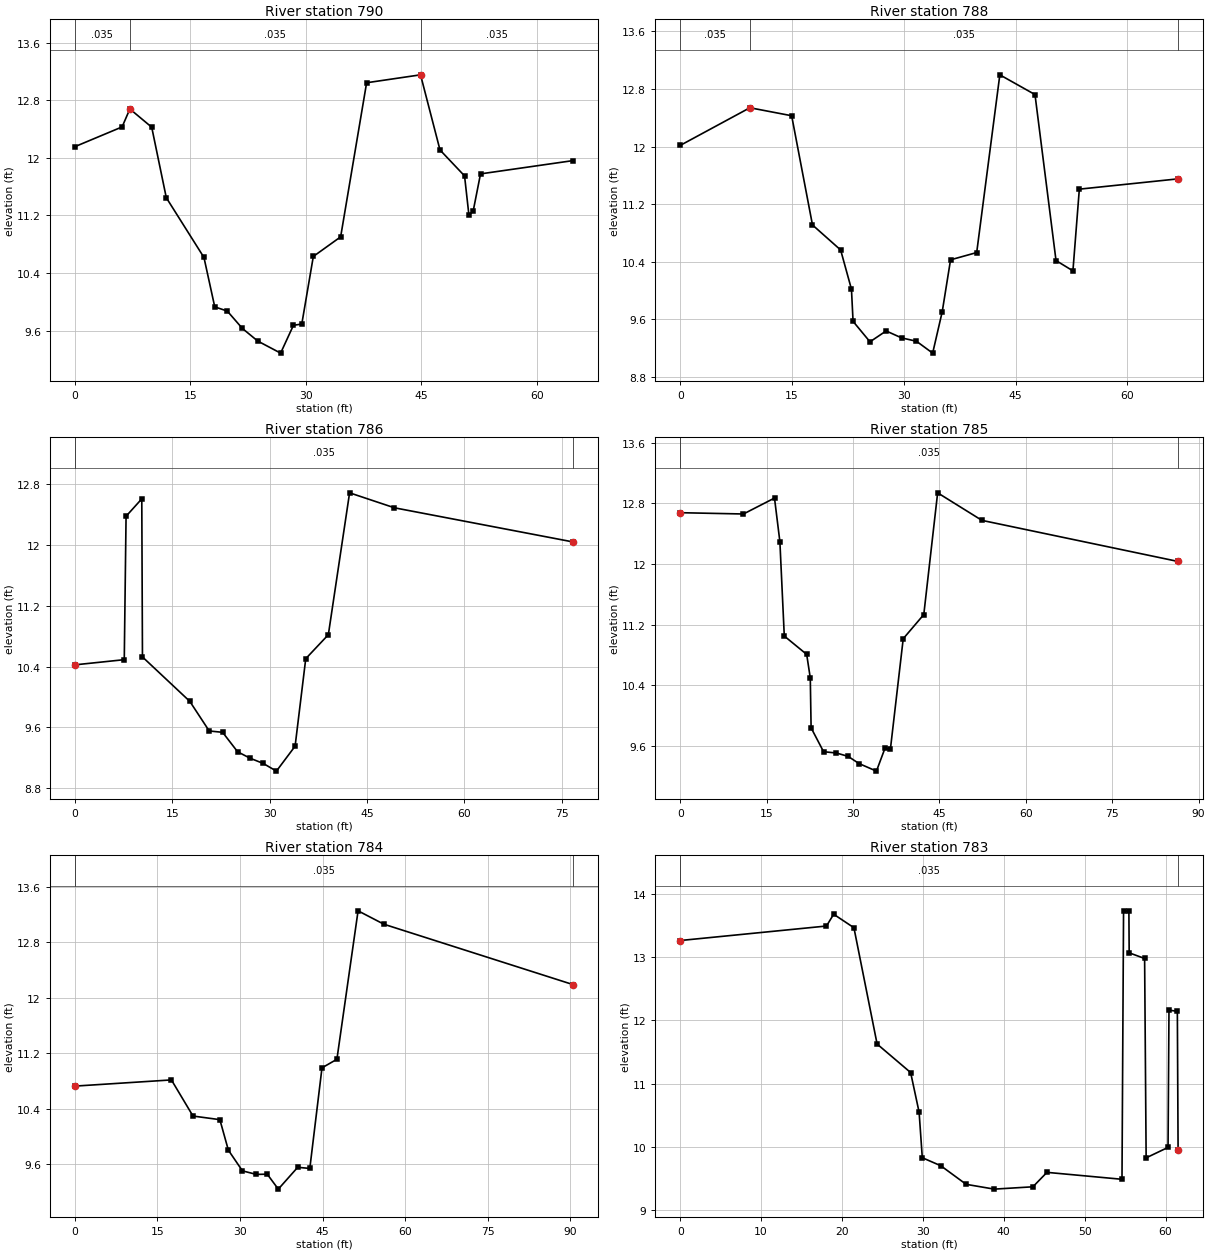
Type RM Length L Ch R = 1 ,790     ,112.03,112.03,112.03
XS GIS Cut Line= 3
      1620509.06      4853082.96      1620518.61      4853146.84
 1620518.6102956 4853146.8419769
#Sta/Elev= 23
       0  12.155   6.127  12.429   7.134  12.678   9.973  12.425  11.868  11.446
  16.758  10.617   18.16   9.931  19.787   9.873  21.747   9.632  23.737   9.457
  26.716   9.289  28.378   9.675  29.466   9.693  30.963  10.631  34.512  10.903
  37.886  13.042  44.889  13.152  47.417  12.109  50.607  11.749  51.171  11.207
   51.72  11.257   52.68  11.777  64.672  11.961
#Mann= 3 , 0 , 0
       0    .035       0   7.134    .035       0  44.889    .035       0
Bank Sta=7.134,44.889
XS Rating Curve= 0
Exp/Cntr=.3,.1

Type RM Length L Ch R = 1 ,788     ,99.84,99.84,99.84
XS GIS Cut Line= 2
      1620410.07      4853081.95 1620393.5507692 4853146.3869995
#Sta/Elev= 21
       0  12.015   9.355  12.538  14.959  12.427  17.753  10.911  21.531  10.564
  22.984  10.019  23.199   9.573   25.47   9.289  27.636    9.44    29.7   9.344
  31.704   9.297  33.881   9.132  35.165   9.707  36.281  10.427   39.79  10.528
  42.894  12.995  47.613  12.721  50.435  10.417  52.704  10.274  53.564  11.408
  66.817  11.551
#Mann= 3 , 0 , 0
       0    .035       0   9.355    .035       0  66.817    .035       0
Bank Sta=9.355,66.817
XS Rating Curve= 0
Exp/Cntr=.3,.1

Type RM Length L Ch R = 1 ,786     ,41.02,41.02,41.02
XS GIS Cut Line= 3
       1620302.9      4853054.54      1620301.53       4853130.7
 1620301.5299838 4853130.7009001
#Sta/Elev= 18
       0  10.423   7.603  10.491   7.881  12.376  10.303  12.605  10.407  10.527
  17.705   9.943  20.695   9.554  22.763   9.536  25.076    9.28  27.016   9.195
  29.024   9.127  31.054   9.026  33.933   9.354  35.575  10.504  39.057  10.819
  42.331  12.684  49.253  12.487  76.741  12.039
#Mann= 3 , 0 , 0
       0    .035       0       0    .035       0  76.741    .035       0
Bank Sta=0,76.741
XS Rating Curve= 0
Exp/Cntr=.3,.1

Type RM Length L Ch R = 1 ,785     ,45.12,45.12,45.12
XS GIS Cut Line= 2
      1620252.58      4853060.95 1620286.8459907 4853140.1907284
#Sta/Elev= 20
       0  12.678  10.981  12.661  16.373  12.871  17.308  12.296  18.072  11.052
  21.961   10.81  22.586  10.499  22.727   9.842   24.89   9.527  27.112    9.51
  29.142   9.466  31.043   9.371   34.07   9.271  35.544   9.571  36.492   9.559
  38.721  11.017   42.29  11.335  44.695   12.94   52.38  12.577   86.44  12.035
#Mann= 3 , 0 , 0
       0    .035       0       0    .035       0   86.44    .035       0
Bank Sta=0,86.44
XS Rating Curve= 0
Exp/Cntr=.3,.1

Type RM Length L Ch R = 1 ,784     ,29.61,29.61,29.61
XS GIS Cut Line= 3
      1620211.99      4853079.74      1620253.08      4853159.96
 1620253.0800487 4853159.9600951
#Sta/Elev= 16
       0  10.728  17.533  10.817  21.454  10.297  26.337  10.245   27.88   9.806
  30.437   9.508  32.967   9.457  34.947    9.46  36.956   9.245  40.482   9.559
  42.682   9.543  44.895  10.991  47.605  11.114  51.452  13.251  56.151  13.058
   90.48   12.19
#Mann= 3 , 0 , 0
       0    .035       0       0    .035       0   90.48    .035       0
Bank Sta=0,90.48
XS Rating Curve= 0
Exp/Cntr=.3,.1

Type RM Length L Ch R = 1 ,783     ,48.88,48.88,48.88
XS GIS Cut Line= 3
      1620180.51      4853096.17      1620214.37      4853147.23
 1620214.3716571 4853147.2324988
#Sta/Elev= 23
       0  13.268  18.082  13.498   18.97  13.685  21.474  13.471  24.341  11.626
  28.484  11.174  29.531  10.545  29.925   9.823   32.21   9.696  35.347   9.401
  38.822   9.325  43.599   9.362  45.334   9.591  54.608   9.481  54.802  13.739
  55.462  13.729  55.496  13.073  57.405  12.983  57.593   9.821  60.301   9.987
  60.416  12.164  61.451  12.145  61.543    9.95
#Mann= 3 , 0 , 0
       0    .035       0       0    .035       0  61.543    .035       0
Bank Sta=0,61.543
XS Rating Curve= 0
Exp/Cntr=.3,.1

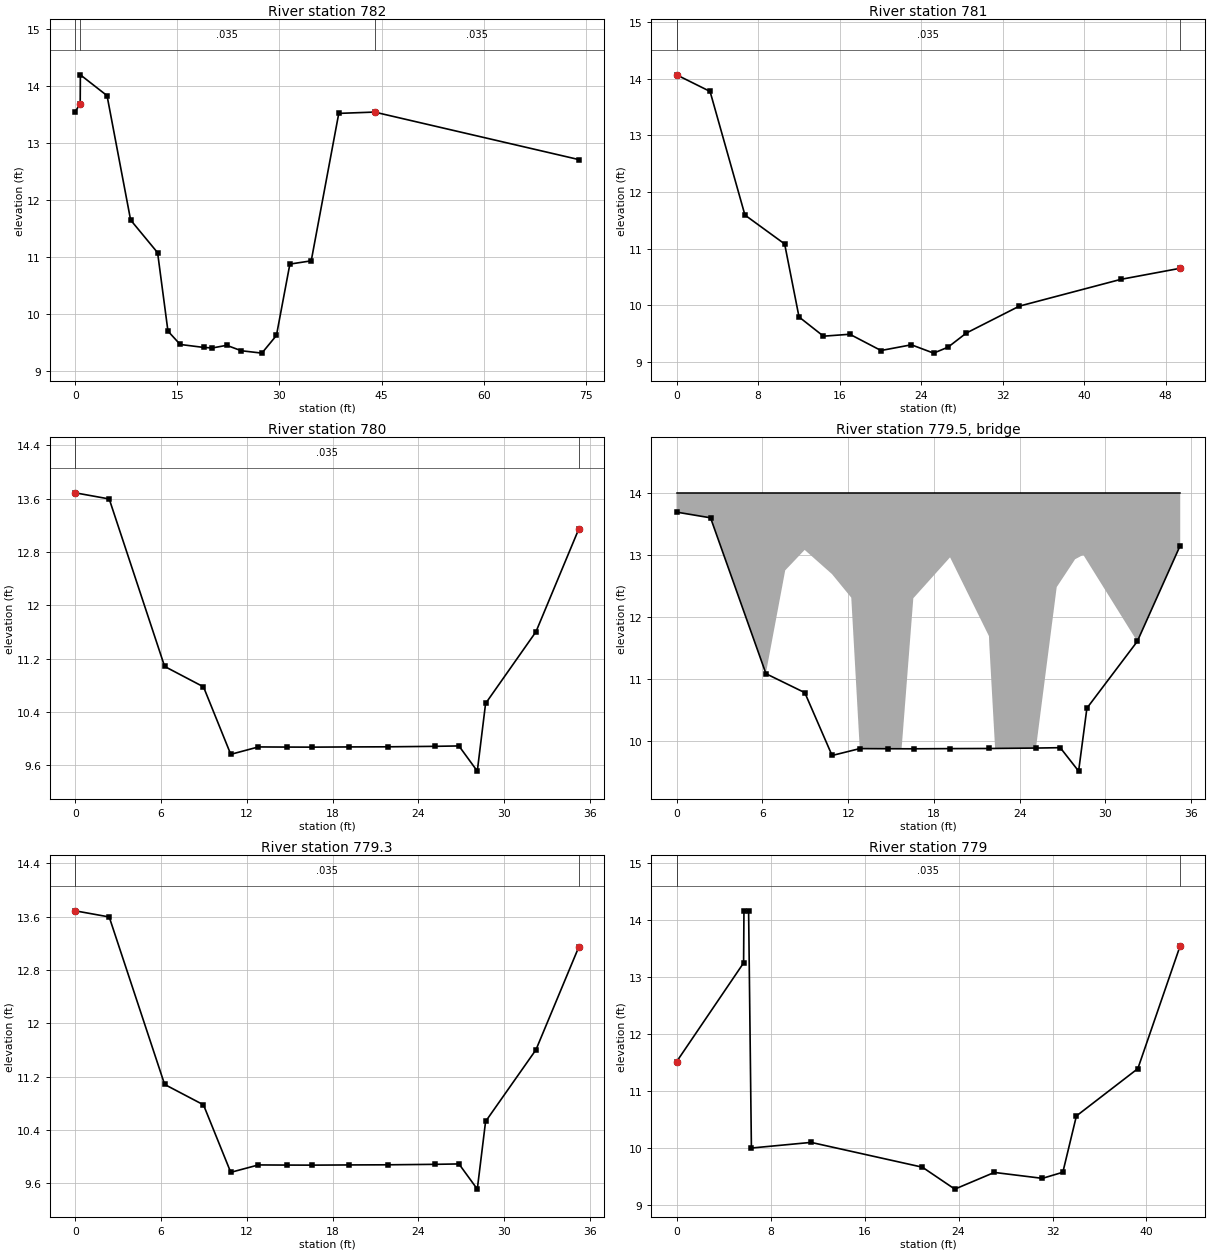
Type RM Length L Ch R = 1 ,782     ,37.5,37.5,37.5
XS GIS Cut Line= 3
      1620150.36      4853135.54      1620186.54      4853199.92
 1620186.5410279 4853199.9218291
#Sta/Elev= 19
       0   13.55     .73  13.692    .756  14.197   4.674  13.832   8.136  11.652
  12.101  11.079  13.622   9.704  15.416    9.47   18.93   9.417  20.158   9.409
  22.251   9.455  24.395    9.36   27.42   9.318   29.56   9.628  31.534  10.879
  34.671  10.936  38.717  13.521  43.967  13.544  73.992  12.711
#Mann= 3 , 0 , 0
       0    .035       0     .73    .035       0  43.967    .035       0
Bank Sta=.73,43.967
XS Rating Curve= 0
Exp/Cntr=.3,.1

Type RM Length L Ch R = 1 ,781     ,23.62,23.62,23.62
XS GIS Cut Line= 2
      1620120.18      4853151.24 1620140.4187484 4853195.2972754
#Sta/Elev= 15
       0  14.069   3.286  13.776   6.708  11.595  10.604  11.085  12.015   9.797
  14.412   9.458      17   9.492  20.057   9.205   23.04   9.306  25.222   9.159
  26.635   9.264  28.437   9.514  33.628   9.988  43.604  10.461  49.417  10.656
#Mann= 3 , 0 , 0
       0    .035       0       0    .035       0  49.417    .035       0
Bank Sta=0,49.417
XS Rating Curve= 0
Exp/Cntr=.3,.1

Type RM Length L Ch R = 1 ,780     ,9,9,9
XS GIS Cut Line= 2
      1620098.28      4853160.07 1620110.2993129 4853192.9081229
#Sta/Elev= 16
       0  13.689   2.377  13.597   6.252  11.084    8.97  10.778  10.878   9.765
  12.813   9.876  14.798   9.874  16.574   9.873   19.15   9.876  21.876   9.878
   25.14   9.885  26.838   9.891  28.122   9.513  28.702  10.528  32.225  11.604
  35.228   13.15
#Mann= 3 , 0 , 0
       0    .035       0       0    .035       0  35.228    .035       0
Bank Sta=0,35.228
XS Rating Curve= 0
Exp/Cntr=.3,.1

Type RM Length L Ch R = 3 ,779.5   ,,,
BEGIN DESCRIPTION:
Ponte di Pontetetto
END DESCRIPTION:
Bridge Culvert--1,0,-1,-1, 0
Deck Dist Width WeirC Skew NumUp NumDn MinLoCord MaxHiCord MaxSubmerge Is_Ogee
.5,8,1.44,0, 19, 19, , , .95, 0, 0,0,,
       0    2.37    6.24     7.6    8.96   10.87   12.22   12.85   15.74   16.56
   19.13   21.85   22.28    25.1   26.59   27.88   28.45   32.23   35.23
      14      14      14      14      14      14      14      14      14      14
      14      14      14      14      14      14      14      14      14
   13.69    13.6   11.08   12.75   13.08   12.69   12.31    9.52    9.37    12.3
   12.96   11.69    9.37     9.3   12.48   12.93      13    11.6   13.15
       0    2.37    6.24     7.6    8.96   10.87   12.22   12.85   15.74   16.56
   19.13   21.85   22.28    25.1   26.59   27.88   28.45   32.23   35.23
      14      14      14      14      14      14      14      14      14      14
      14      14      14      14      14      14      14      14      14
   13.69    13.6   11.08   12.75   13.08   12.69   12.31    9.52    9.37    12.3
   12.96   11.69    9.37     9.3   12.48   12.93      13    11.6   13.15
BR Coef=-1 , 0 , 0 ,1.25, 0 ,,,.8,-1,2,0,
WSPro=,,,, 1 ,,,, 0 ,,,, 0 ,,,,-1 ,-1 ,-1 , 0 , 0 , 0 , 0 , 0
BC Design=,, 0 ,, 0 ,,,,,,
BC HTab Sub Flow Pts= 40

Type RM Length L Ch R = 1 ,779.3   ,9.1,9.1,9.1
XS GIS Cut Line= 2
      1620098.28      4853160.07 1620110.2993129 4853192.9081229
#Sta/Elev= 16
       0  13.689   2.377  13.597   6.252  11.084    8.97  10.778  10.878   9.765
  12.813   9.876  14.798   9.874  16.574   9.873   19.15   9.876  21.876   9.878
   25.14   9.885  26.838   9.891  28.122   9.513  28.702  10.528  32.225  11.604
  35.228   13.15
#Mann= 3 , 0 , 0
       0    .035       0       0    .035       0  35.228    .035       0
Bank Sta=0,35.228
XS Rating Curve= 0
Exp/Cntr=.3,.1

Type RM Length L Ch R = 1 ,779     ,19.07,19.07,19.07
XS GIS Cut Line= 3
      1620088.08      4853157.61      1620102.44      4853197.85
 1620102.4406398 4853197.8517928
#Sta/Elev= 14
       0  11.508   5.706  13.242   5.736  14.151   6.132  14.156    6.37   9.994
  11.452  10.093  20.922   9.658  23.684   9.273  27.048   9.566  31.138   9.462
   32.88   9.569  34.034  10.557  39.263  11.387  42.872  13.546
#Mann= 3 , 0 , 0
       0    .035       0       0    .035       0  42.872    .035       0
Bank Sta=0,42.872
XS Rating Curve= 0
Exp/Cntr=.3,.1