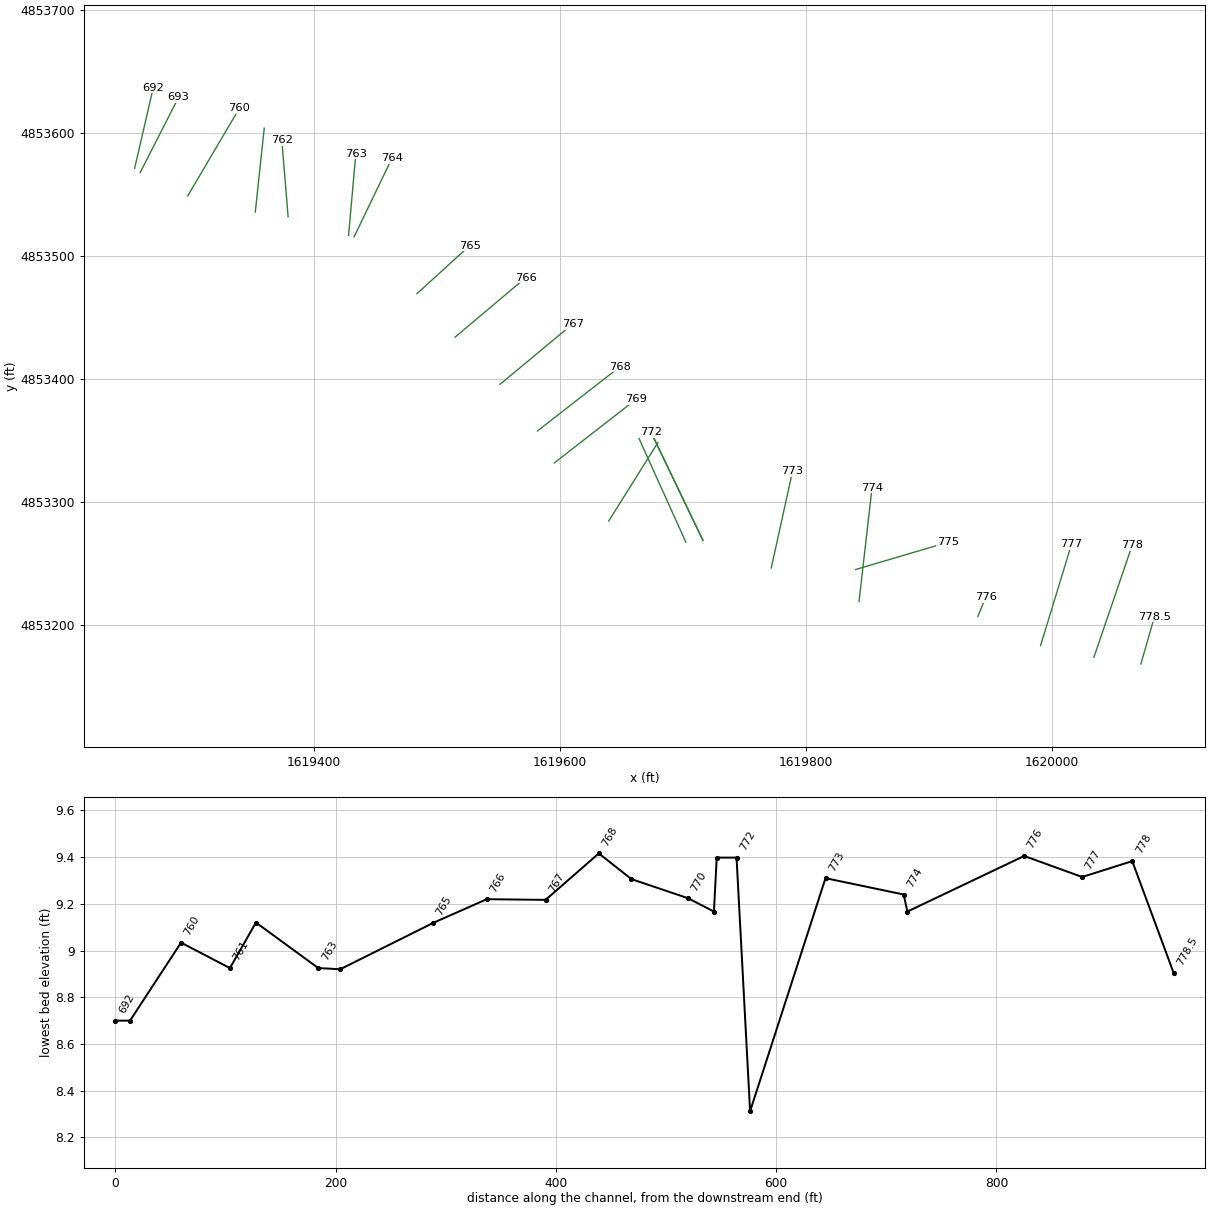
HEC-RAS study ozz_def.prj: ozzeri

--- ozz_def.g02 (geometry) --- (continued)

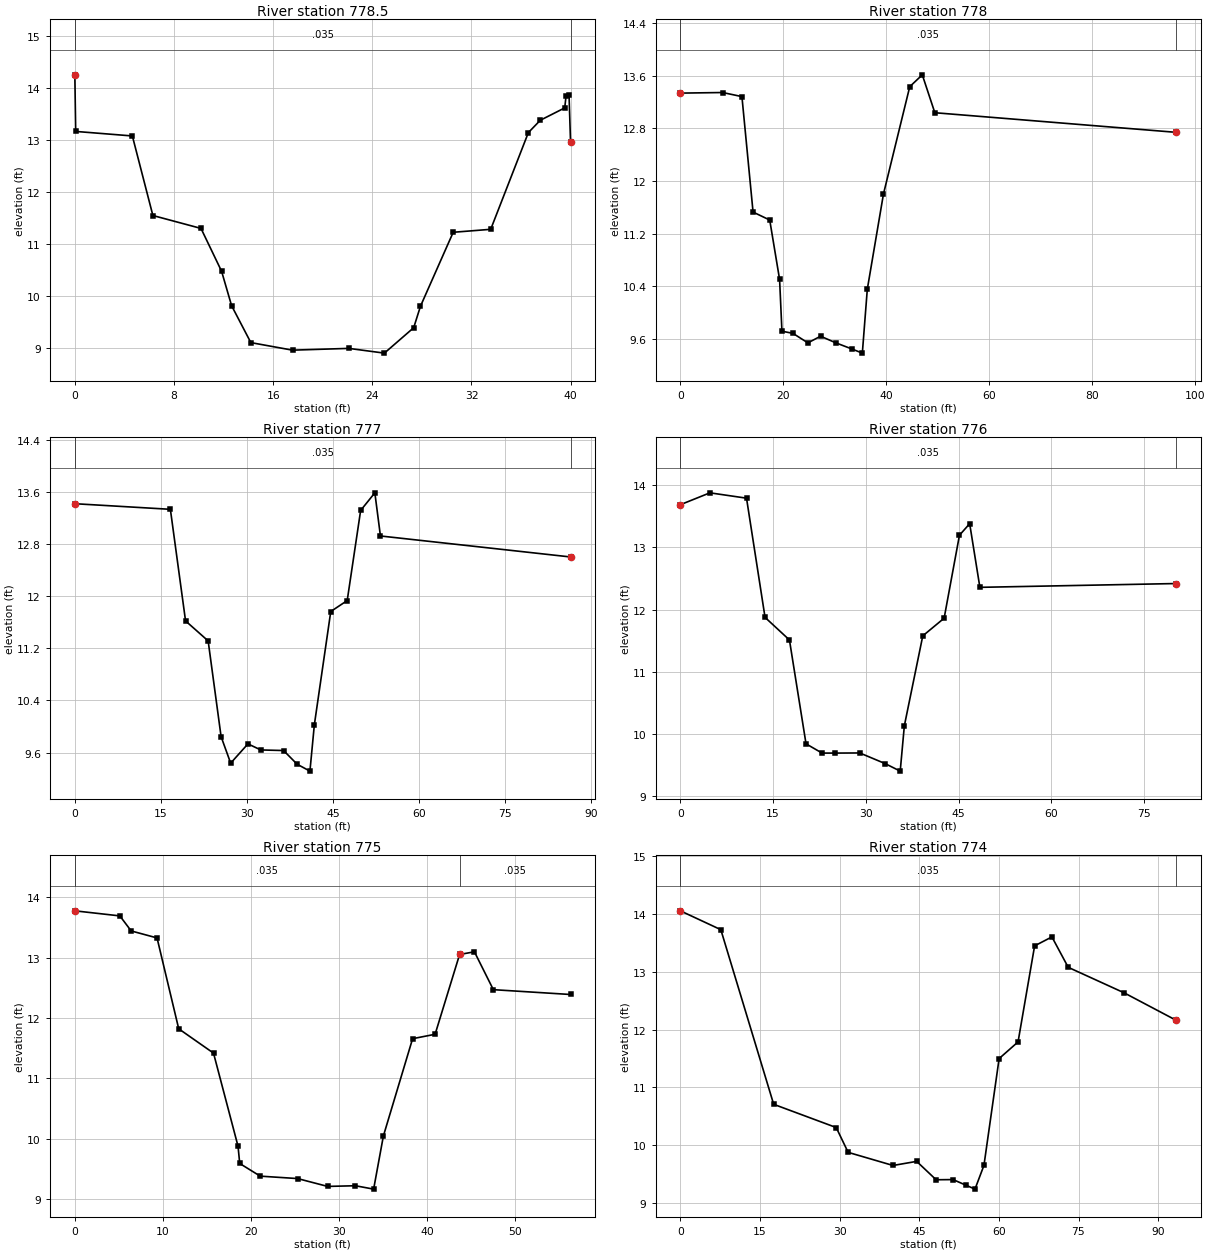
Type RM Length L Ch R = 1 ,778.5   ,37.61,37.61,37.61
XS GIS Cut Line= 2
      1620072.65      4853168.62 1620083.6699726 4853206.8999047
#Sta/Elev= 21
       0  14.249     .07  13.162   4.641  13.075   6.297  11.547  10.179  11.299
   11.84  10.476  12.647   9.815    14.2   9.106  17.562   8.961  22.099   8.995
  24.974   8.904  27.337   9.392  27.885   9.805  30.525  11.225  33.551  11.282
  36.587  13.139  37.548  13.376  39.522  13.614  39.633  13.851   39.87  13.862
   39.99  12.967
#Mann= 3 , 0 , 0
       0    .035       0       0    .035       0   39.99    .035       0
Bank Sta=0,39.99
XS Rating Curve= 0
Exp/Cntr=.3,.1

Type RM Length L Ch R = 1 ,778     ,45.47,45.47,45.47
XS GIS Cut Line= 2
      1620034.46      4853174.11  1620065.606733 4853265.1604497
#Sta/Elev= 19
       0  13.335   8.221  13.344  11.964  13.282  14.126  11.527  17.365  11.406
   19.28  10.503  19.737   9.716  21.866   9.684  24.775   9.539  27.244    9.64
  30.218   9.539  33.361   9.445  35.356   9.383   36.32  10.354  39.461  11.802
  44.566  13.433  47.004  13.613  49.438  13.037    96.3  12.739
#Mann= 3 , 0 , 0
       0    .035       0       0    .035       0    96.3    .035       0
Bank Sta=0,96.3
XS Rating Curve= 0
Exp/Cntr=.3,.1

Type RM Length L Ch R = 1 ,777     ,52.65,52.65,52.65
XS GIS Cut Line= 2
      1619991.09      4853183.58  1620016.289971 4853266.0099052
#Sta/Elev= 18
       0  13.418  16.654  13.332  19.299   11.62  23.238  11.313  25.494   9.844
  27.163   9.437  30.173   9.733  32.417    9.64  36.384   9.631  38.746   9.421
  40.978   9.315  41.747  10.025   44.61  11.764  47.475  11.932  49.818  13.315
  52.293  13.585  53.267  12.923    86.4  12.601
#Mann= 3 , 0 , 0
       0    .035       0       0    .035       0    86.4    .035       0
Bank Sta=0,86.4
XS Rating Curve= 0
Exp/Cntr=.3,.1

Type RM Length L Ch R = 1 ,776     ,106.06,106.06,106.06
XS GIS Cut Line= 2
      1619940.14      4853207.27  1619946.380491  4853222.750555
#Sta/Elev= 18
       0  13.687   4.782  13.878  10.701  13.792  13.697  11.876  17.643  11.513
  20.323   9.844  22.918   9.695   25.04   9.695  29.016   9.697  33.095   9.527
  35.555   9.405  36.222  10.133  39.203  11.579  42.657  11.863  45.136  13.197
  46.788  13.382  48.438  12.359   80.16   12.42
#Mann= 3 , 0 , 0
       0    .035       0       0    .035       0   80.16    .035       0
Bank Sta=0,80.16
XS Rating Curve= 0
Exp/Cntr=.3,.1

Type RM Length L Ch R = 1 ,775     ,3.39,3.39,3.39
XS GIS Cut Line= 3
      1619840.75      4853245.42      1619915.65      4853267.55
 1619915.6510536 4853267.5503113
#Sta/Elev= 20
       0  13.777   5.114  13.693   6.399  13.444   9.337  13.328  11.797  11.823
  15.749   11.42  18.534   9.877  18.725   9.592  21.054   9.382  25.291   9.342
  28.708   9.212  31.866   9.223  33.932   9.167  35.039  10.047  38.357  11.659
  40.913  11.732  43.694  13.054  45.378  13.098  47.526  12.471  56.291  12.391
#Mann= 3 , 0 , 0
       0    .035       0       0    .035       0  43.694    .035       0
Bank Sta=0,43.694
XS Rating Curve= 0
Exp/Cntr=.3,.1

Type RM Length L Ch R = 1 ,774     ,70.95,70.95,70.95
XS GIS Cut Line= 2
      1619843.51      4853219.32      1619854.09      4853311.96
#Sta/Elev= 19
       0  14.053   7.625  13.727  17.579  10.707  29.361  10.305  31.605   9.876
  40.062   9.649  44.514    9.72  48.179   9.402  51.367   9.405  53.772   9.309
  55.499    9.24  57.188   9.651  60.044  11.498   63.61  11.786   66.73  13.447
  69.989  13.602   73.06  13.076   83.59  12.635   93.37  12.161
#Mann= 3 , 0 , 0
       0    .035       0       0    .035       0   93.37    .035       0
Bank Sta=0,93.37
XS Rating Curve= 0
Exp/Cntr=.3,.1

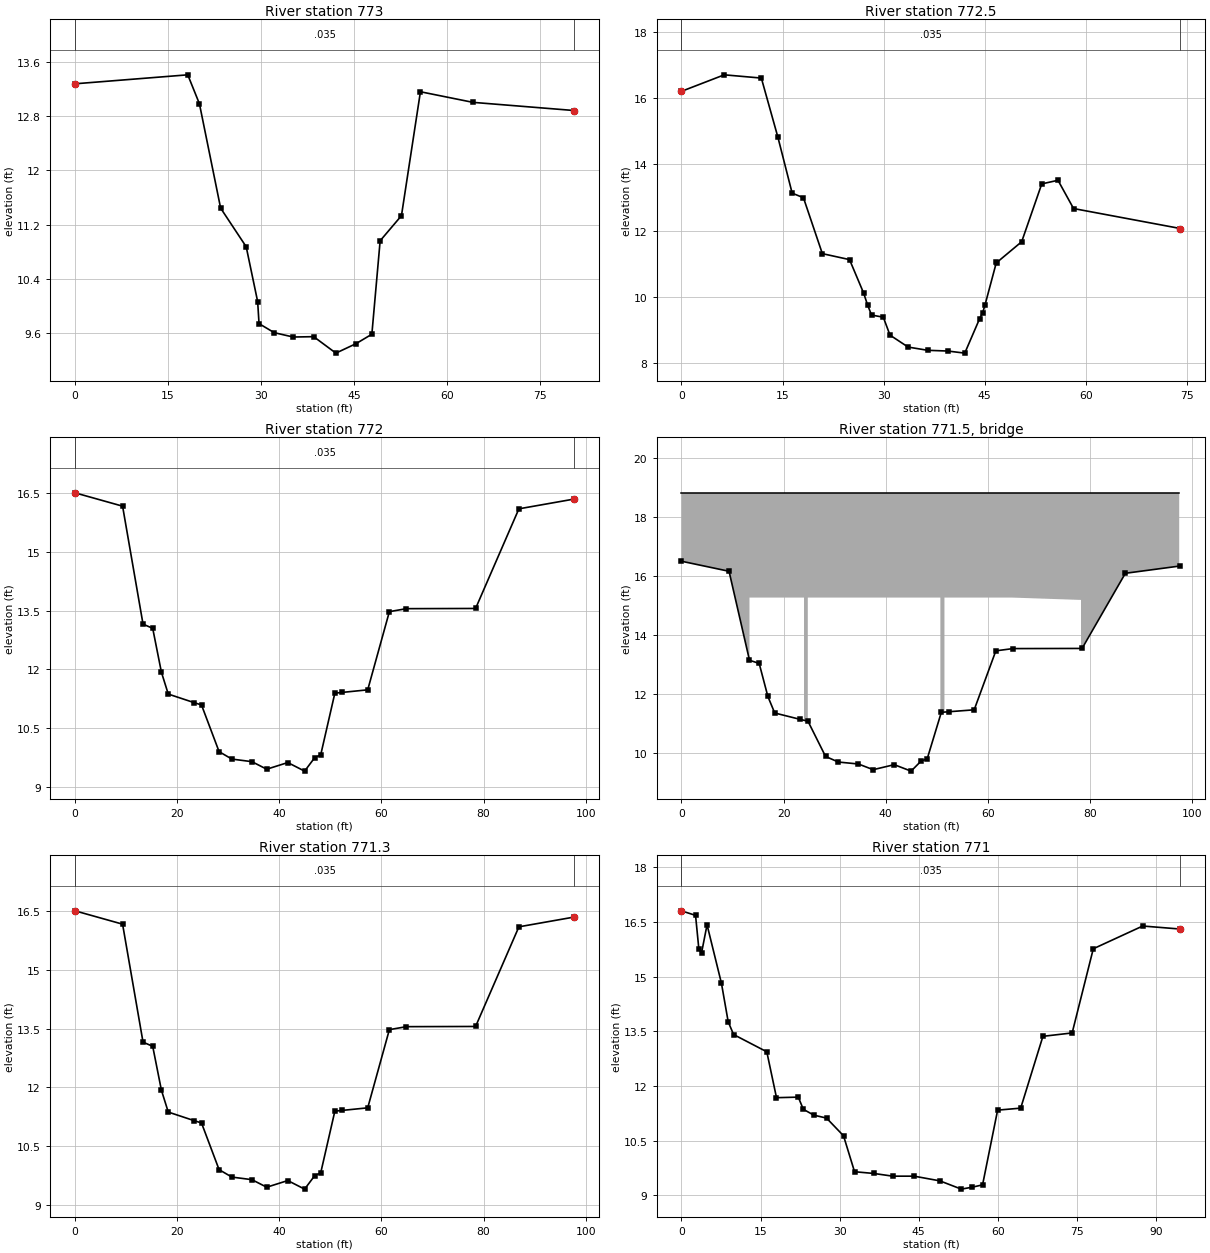
Type RM Length L Ch R = 1 ,773     ,68.49,68.49,68.49
XS GIS Cut Line= 3
      1619772.16      4853246.71      1619789.45      4853325.24
 1619789.4508613 4853325.2439117
#Sta/Elev= 18
       0  13.272  18.176  13.404  20.055  12.978  23.472  11.443  27.592  10.875
   29.44  10.068  29.661   9.744   32.11   9.611  35.157   9.547  38.472   9.552
  42.046    9.31  45.288   9.449  47.846   9.588  49.181  10.963  52.615  11.332
  55.672  13.155  64.143  12.999  80.424  12.879
#Mann= 3 , 0 , 0
       0    .035       0       0    .035       0  80.424    .035       0
Bank Sta=0,80.424
XS Rating Curve= 0
Exp/Cntr=.3,.1

Type RM Length L Ch R = 1 ,772.5   ,12.3,12.3,12.3
#Sta/Elev= 27
       0  16.206   6.349  16.704  11.854  16.606  14.312  14.821  16.425  13.136
    18.1  12.998  20.904  11.312  24.939  11.132  27.027  10.125  27.608   9.769
  28.206    9.46  29.948   9.396  30.942   8.855  33.627   8.495  36.539   8.397
  39.521   8.375  42.037   8.312   44.24    9.35  44.693   9.531  45.042   9.765
  46.736  11.054   46.77  11.042  50.482  11.671  53.461  13.415   55.87  13.524
  58.179  12.672  74.043  12.069
#Mann= 3 , 0 , 0
       0    .035       0       0    .035       0  74.043    .035       0
Bank Sta=0,74.043
XS Rating Curve= 0
Exp/Cntr=.3,.1

Type RM Length L Ch R = 1 ,772     ,18,18,18
XS GIS Cut Line= 2
      1619716.63      4853269.05 1619674.4509079 4853356.9281085
#Sta/Elev= 24
       0  16.512   9.319  16.171  13.324  13.155  15.218  13.049  16.921  11.928
  18.263  11.368    23.3   11.15  24.776  11.089  28.218   9.896  30.717   9.706
  34.646    9.64  37.544   9.447   41.67   9.617  44.965   9.398  46.941   9.742
  48.119   9.814  50.887  11.391  52.311   11.41  57.323  11.476  61.564  13.475
  64.912  13.551  78.448  13.556  86.928  16.103  97.718  16.352
#Mann= 3 , 0 , 0
       0    .035       0       0    .035       0  97.718    .035       0
Bank Sta=0,97.718
XS Rating Curve= 0
Exp/Cntr=.3,.1

Type RM Length L Ch R = 3 ,771.5   ,,,
BEGIN DESCRIPTION:
Bretellina
END DESCRIPTION:
Bridge Culvert--1,0,-1,-1, 0
Deck Dist Width WeirC Skew NumUp NumDn MinLoCord MaxHiCord MaxSubmerge Is_Ogee
.5,17,1.44,0, 30, 30, , , .95, 0, 0,0,,
       0    9.31   13.32   13.32    15.2   16.91   18.21      24      24   24.74
   24.74   28.16   30.64   34.56   37.46   41.59   44.88   46.85   48.01    50.7
    50.7    51.5    51.5   57.16   61.39   64.72   78.24   78.24   86.69   97.47
   18.83   18.83   18.83   18.83   18.83   18.83   18.83   18.83   18.83   18.83
   18.83   18.83   18.83   18.83   18.83   18.83   18.83   18.83   18.83   18.83
   18.83   18.83   18.83   18.83   18.83   18.83   18.83   18.83   18.83   18.83
   16.51   16.17   13.15   15.28   15.28   15.28   15.28   15.28   11.07   11.08
   15.28   15.28   15.28   15.28   15.28   15.28   15.28   15.28   15.28   15.28
   11.42    11.4   15.28   15.28   15.28   15.28    15.2   13.56   15.28   15.28
       0    9.31   13.32   13.32    15.2   16.91   18.21      24      24   24.74
   24.74   28.16   30.64   34.56   37.46   41.59   44.88   46.85   48.01    50.7
    50.7    51.5    51.5   57.16   61.39   64.72   78.24   78.24   86.69   97.47
   18.83   18.83   18.83   18.83   18.83   18.83   18.83   18.83   18.83   18.83
   18.83   18.83   18.83   18.83   18.83   18.83   18.83   18.83   18.83   18.83
   18.83   18.83   18.83   18.83   18.83   18.83   18.83   18.83   18.83   18.83
   16.51   16.17   13.15   15.28   15.28   15.28   15.28   15.28   11.07   11.08
   15.28   15.28   15.28   15.28   15.28   15.28   15.28   15.28   15.28   15.28
   11.42    11.4   15.28   15.28   15.28   15.28    15.2   13.56   15.28   15.28
BR Coef=-1 , 0 , 0 ,1.25, 0 ,,,.8,-1,2,0,
WSPro=,,,, 1 ,,,, 0 ,,,, 0 ,,,,-1 ,-1 ,-1 , 0 , 0 , 0 , 0 , 0
BC Design=,, 0 ,, 0 ,,,,,,
BC HTab Sub Flow Pts= 40

Type RM Length L Ch R = 1 ,771.3   ,2.54,2.54,2.54
XS GIS Cut Line= 2
      1619716.63      4853269.05 1619674.4509079 4853356.9281085
#Sta/Elev= 24
       0  16.512   9.319  16.171  13.324  13.155  15.218  13.049  16.921  11.928
  18.263  11.368    23.3   11.15  24.776  11.089  28.218   9.896  30.717   9.706
  34.646    9.64  37.544   9.447   41.67   9.617  44.965   9.398  46.941   9.742
  48.119   9.814  50.887  11.391  52.311   11.41  57.323  11.476  61.564  13.475
  64.912  13.551  78.448  13.556  86.928  16.103  97.718  16.352
#Mann= 3 , 0 , 0
       0    .035       0       0    .035       0  97.718    .035       0
Bank Sta=0,97.718
XS Rating Curve= 0
Exp/Cntr=.3,.1

Type RM Length L Ch R = 1 ,771     ,23.45,23.45,23.45
XS GIS Cut Line= 2
      1619702.69      4853267.74 1619664.6481939  4853351.921868
#Sta/Elev= 30
       0  16.809   2.673  16.684   3.295  15.765   3.808  15.653   4.854  16.426
   7.585  14.818   8.864  13.762   9.888  13.412  16.185  12.938  18.025  11.678
  22.157  11.693  23.108   11.36  25.088  11.199  27.511  11.118  30.736  10.632
  32.827   9.645  36.491   9.597  40.067   9.523  44.125   9.523  49.012   9.394
  53.075   9.167  55.135    9.22  57.107   9.284  59.962  11.336  64.338  11.391
  68.553  13.363  74.098  13.456  78.106  15.767   87.48  16.392   94.64  16.308
#Mann= 3 , 0 , 0
       0    .035       0       0    .035       0   94.64    .035       0
Bank Sta=0,94.64
XS Rating Curve= 0
Exp/Cntr=.3,.1

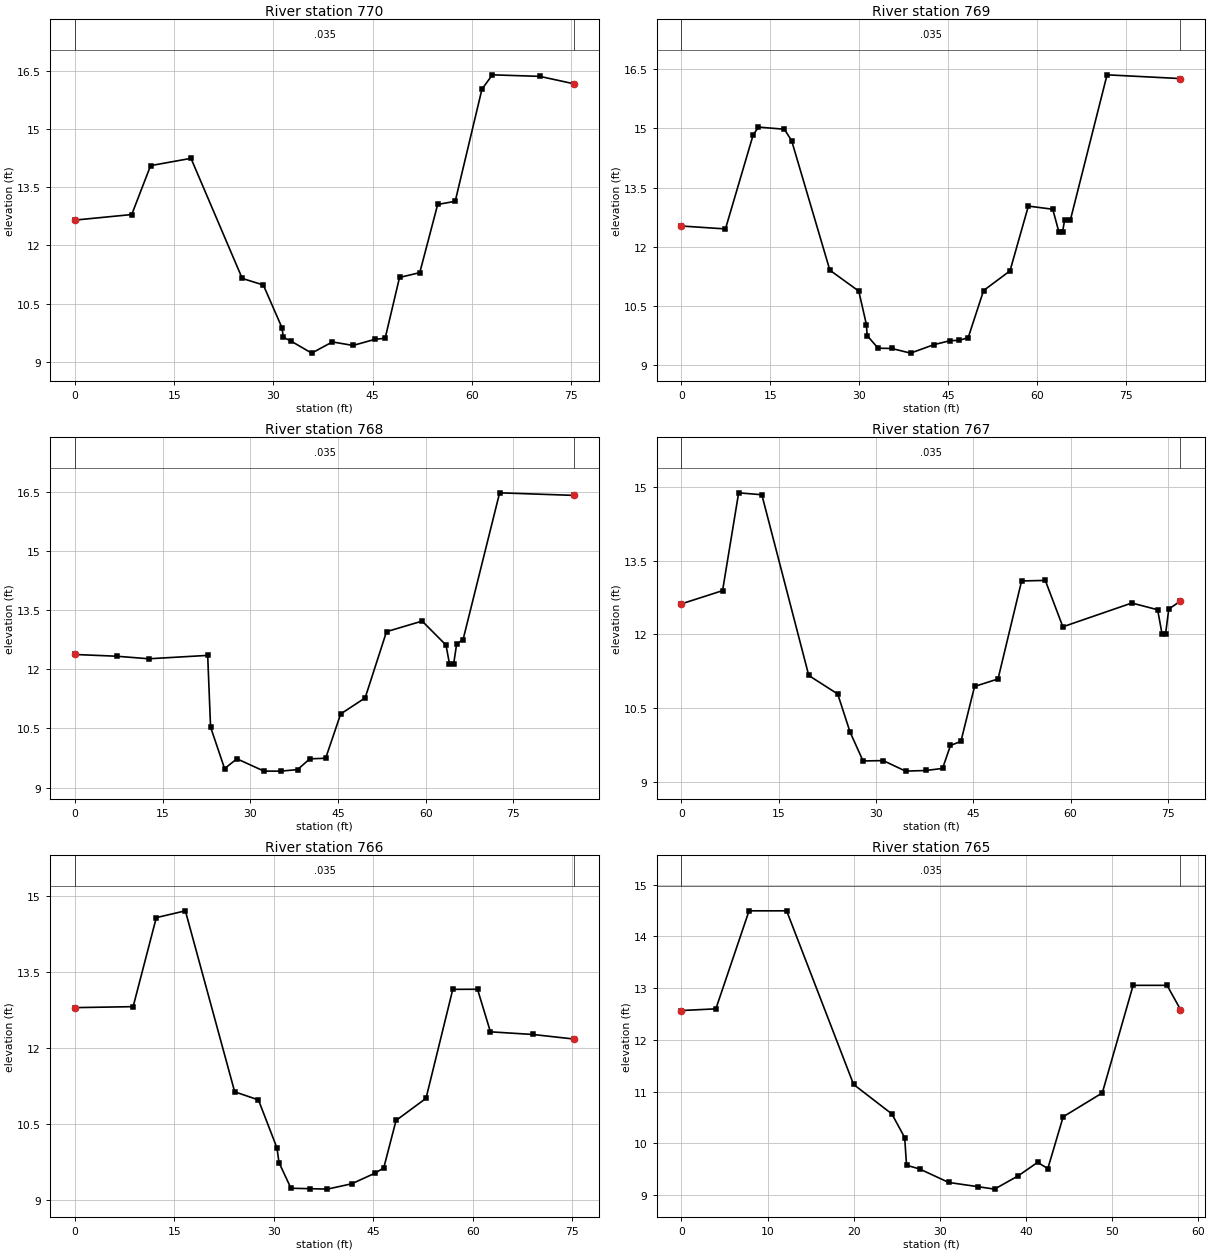
Type RM Length L Ch R = 1 ,770     ,51.48,51.48,51.48
XS GIS Cut Line= 2
      1619639.99       4853284.8  1619679.968886 4853348.6082221
#Sta/Elev= 22
       0  12.654   8.578  12.797  11.429  14.058  17.537  14.246   25.28   11.15
   28.47  10.981  31.296   9.877   31.49   9.635  32.683   9.531  35.785   9.224
  38.915   9.513  42.032   9.422  45.351    9.58  46.888   9.607  49.062  11.175
  52.123  11.299  54.831  13.057   57.48  13.138  61.524   16.03  63.097  16.399
  70.268  16.359  75.438  16.167
#Mann= 3 , 0 , 0
       0    .035       0       0    .035       0  75.438    .035       0
Bank Sta=0,75.438
XS Rating Curve= 0
Exp/Cntr=.3,.1

Type RM Length L Ch R = 1 ,769     ,29.6,29.6,29.6
XS GIS Cut Line= 2
      1619595.76      4853332.04      1619662.08      4853383.67
#Sta/Elev= 27
       0  12.528   7.425  12.454  12.092  14.832  12.994  15.035  17.362  14.981
  18.593  14.693  25.049  11.408   29.93  10.878  31.218   10.03  31.339   9.752
  33.189   9.431  35.486   9.424  38.677   9.306  42.596    9.52  45.358   9.622
  46.861    9.63  48.397   9.697  50.997  10.892  55.455  11.391  58.554  13.033
  62.676  12.953  63.686  12.388  64.337  12.385  64.663  12.671  65.647   12.68
  71.839   16.36   84.23  16.265
#Mann= 3 , 0 , 0
       0    .035       0       0    .035       0   84.23    .035       0
Bank Sta=0,84.23
XS Rating Curve= 0
Exp/Cntr=.3,.1

Type RM Length L Ch R = 1 ,768     ,48.35,48.35,48.35
XS GIS Cut Line= 3
      1619582.12      4853358.11      1619649.12      4853410.25
 1619649.1278153 4853410.2560819
#Sta/Elev= 23
       0  12.378   7.106  12.334  12.624  12.269  22.699  12.355  23.192  10.535
  25.591    9.48  27.702   9.729  32.327   9.416  35.192   9.416  38.066   9.454
  40.165   9.728  42.878   9.743  45.445  10.867  49.632  11.276  53.289  12.957
  59.385  13.226  63.459  12.618  64.059  12.143  64.782  12.146  65.289  12.648
  66.384  12.755  72.637  16.483   85.36  16.418
#Mann= 3 , 0 , 0
       0    .035       0       0    .035       0   85.36    .035       0
Bank Sta=0,85.36
XS Rating Curve= 0
Exp/Cntr=.3,.1

Type RM Length L Ch R = 1 ,767     ,53.37,53.37,53.37
XS GIS Cut Line= 3
      1619551.63      4853395.97      1619610.63        4853445.
 1619610.6322297  4853445.001853
#Sta/Elev= 25
       0  12.622   6.339  12.891   8.821  14.882  12.394  14.843  19.633  11.164
  24.097  10.787  25.997  10.013  28.006   9.424  31.126   9.431  34.558   9.217
  37.674    9.23  40.265   9.272  41.485   9.739  43.096   9.823  45.202  10.941
  48.819  11.093  52.453  13.088  56.109  13.099  58.817  12.155  69.453  12.639
  73.433  12.502  74.119  12.004  74.666  12.018  75.154  12.517  76.953  12.678
#Mann= 3 , 0 , 0
       0    .035       0       0    .035       0  76.953    .035       0
Bank Sta=0,76.953
XS Rating Curve= 0
Exp/Cntr=.3,.1

Type RM Length L Ch R = 1 ,766     ,48.89,48.89,48.89
XS GIS Cut Line= 2
      1619515.06      4853434.32 1619572.5493112 4853482.7094203
#Sta/Elev= 21
       0  12.796   8.773  12.815  12.267  14.569  16.652  14.703  24.095  11.137
  27.677  10.978  30.472  10.032  30.783   9.742  32.587   9.237  35.419   9.229
  38.066    9.22  41.751   9.325   45.19    9.53  46.577   9.635  48.441  10.573
  52.961  11.009  57.001  13.156  60.733  13.158  62.678  12.319   69.07  12.267
  75.289  12.177
#Mann= 3 , 0 , 0
       0    .035       0       0    .035       0  75.289    .035       0
Bank Sta=0,75.289
XS Rating Curve= 0
Exp/Cntr=.3,.1

Type RM Length L Ch R = 1 ,765     ,84.19,84.19,84.19
XS GIS Cut Line= 2
      1619484.15       4853469.7 1619526.9092616 4853508.6993265
#Sta/Elev= 20
       0  12.569   3.995  12.602   7.846  14.496  12.211  14.496  19.983  11.141
  24.427  10.571  25.913  10.114   26.13    9.58  27.638   9.508  31.023   9.247
  34.433   9.165  36.342   9.118  39.084   9.374  41.344   9.635   42.53   9.515
  44.313  10.516  48.856  10.977  52.434  13.056  56.374  13.056  57.929  12.589
#Mann= 3 , 0 , 0
       0    .035       0       0    .035       0  57.929    .035       0
Bank Sta=0,57.929
XS Rating Curve= 0
Exp/Cntr=.3,.1

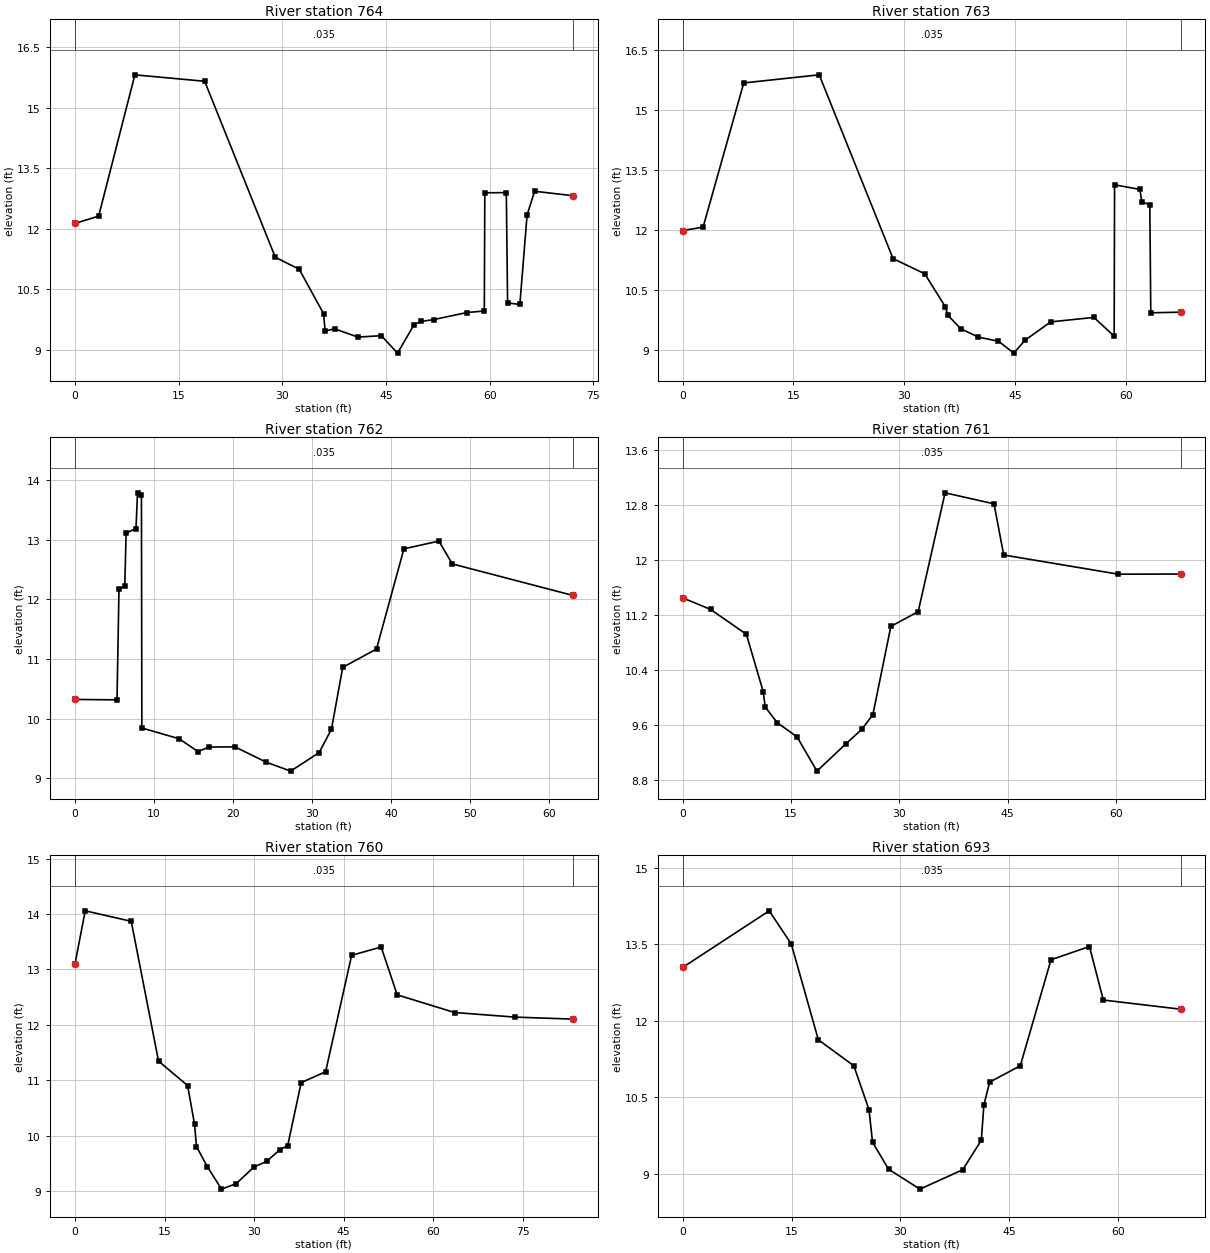
Type RM Length L Ch R = 1 ,764     ,19.92,19.92,19.92
XS GIS Cut Line= 3
      1619432.96      4853515.77 1619457.7043412 4853567.1917088
 1619463.8117765 4853579.8836918
#Sta/Elev= 24
       0  12.135   3.431  12.318   8.671  15.821  18.768  15.661  28.985  11.297
  32.445      11  35.963   9.901  36.197    9.47  37.579   9.523  40.922   9.318
  44.331   9.352  46.667    8.92  49.072   9.629   50.06   9.705  51.915   9.752
  56.661   9.925   59.22   9.965  59.295  12.896  62.404    12.9   62.59  10.164
  64.363  10.128  65.411  12.347  66.496  12.934  72.014  12.824
#Mann= 3 , 0 , 0
       0    .035       0       0    .035       0  72.014    .035       0
Bank Sta=0,72.014
XS Rating Curve= 0
Exp/Cntr=.3,.1

Type RM Length L Ch R = 1 ,763     ,56.61,56.61,56.61
XS GIS Cut Line= 2
       1619428.5      4853517.14 1619434.4296443 4853583.5160181
#Sta/Elev= 22
       0  11.993    2.76  12.077   8.267  15.686  18.487  15.889  28.491   11.29
  32.777  10.911   35.58  10.082  35.883   9.881  37.644   9.536  40.052   9.325
  42.756   9.224  44.848   8.925  46.351   9.245  49.841   9.707  55.699   9.819
  58.437   9.348  58.493  13.137  61.918  13.022  62.185  12.711  63.266  12.638
  63.398   9.934  67.426    9.95
#Mann= 3 , 0 , 0
       0    .035       0       0    .035       0  67.426    .035       0
Bank Sta=0,67.426
XS Rating Curve= 0
Exp/Cntr=.3,.1

Type RM Length L Ch R = 1 ,762     ,23.65,23.65,23.65
XS GIS Cut Line= 3
      1619379.36      4853532.17      1619374.24      4853594.51
 1619374.2397624 4853594.5128932
#Sta/Elev= 23
       0  10.323   5.322  10.316   5.571   12.17   6.306  12.228   6.473  13.117
   7.724  13.189   7.917   13.79   8.412  13.752   8.465   9.844   13.19   9.663
  15.555   9.449  16.974   9.524  20.247   9.527  24.193    9.27  27.282    9.12
  30.885   9.431  32.445   9.823   33.87  10.861  38.143  11.169  41.609   12.85
  46.031   12.98  47.731  12.597  62.963  12.069
#Mann= 3 , 0 , 0
       0    .035       0       0    .035       0  62.963    .035       0
Bank Sta=0,62.963
XS Rating Curve= 0
Exp/Cntr=.3,.1

Type RM Length L Ch R = 1 ,761     ,44.36,44.36,44.36
XS GIS Cut Line= 3
      1619352.68      4853536.12      1619359.95      4853604.25
  1619359.950531 4853604.2549766
#Sta/Elev= 18
       0  11.444   3.852  11.277   8.821  10.915  11.152   10.08  11.431   9.857
  13.089    9.63  15.834   9.424  18.592   8.925  22.614   9.323   24.79   9.531
  26.339   9.745  28.831   11.03  32.617  11.244  36.343  12.972  43.117  12.812
  44.466  12.068  60.335  11.789  68.955  11.791
#Mann= 3 , 0 , 0
       0    .035       0       0    .035       0  68.955    .035       0
Bank Sta=0,68.955
XS Rating Curve= 0
Exp/Cntr=.3,.1

Type RM Length L Ch R = 1 ,760     ,46.34,46.34,46.34
XS GIS Cut Line= 3
      1619297.78       4853549.2      1619339.63      4853620.24
 1619339.6300503 4853620.2400855
#Sta/Elev= 22
       0  13.092   1.723  14.056   9.426  13.867  13.996  11.344  18.866  10.903
  20.028  10.201   20.35   9.803  22.173   9.438  24.535   9.034  26.997   9.133
  29.942   9.431  32.089   9.535  34.318   9.745  35.615   9.818  37.877  10.956
  41.968  11.152   46.32  13.253  51.268  13.403  53.952   12.54  63.555  12.221
  73.696  12.138   83.34  12.102
#Mann= 3 , 0 , 0
       0    .035       0       0    .035       0   83.34    .035       0
Bank Sta=0,83.34
XS Rating Curve= 0
Exp/Cntr=.3,.1

Type RM Length L Ch R = 1 ,693     ,13.26,13.26,13.26
XS GIS Cut Line= 2
       1619259.1      4853568.11      1619290.24      4853629.23
#Sta/Elev= 18
       0   13.05 11.9201 14.1601 14.9599   13.51   18.69 11.6299 23.5799   11.12
   25.67 10.2599 26.1601  9.6201 28.3699  9.0901 32.6901  8.6999 38.5901    9.08
 41.1501    9.66    41.5 10.3501 42.3001    10.8 46.5201   11.12 50.7501    13.2
   56.05   13.46 57.9599 12.4099 68.6001 12.2301
#Mann= 3 , 0 , 0
       0    .035       0       0    .035       0 68.6001    .035       0
Bank Sta=0,68.6001
XS Rating Curve= 0
Exp/Cntr=.3,.1

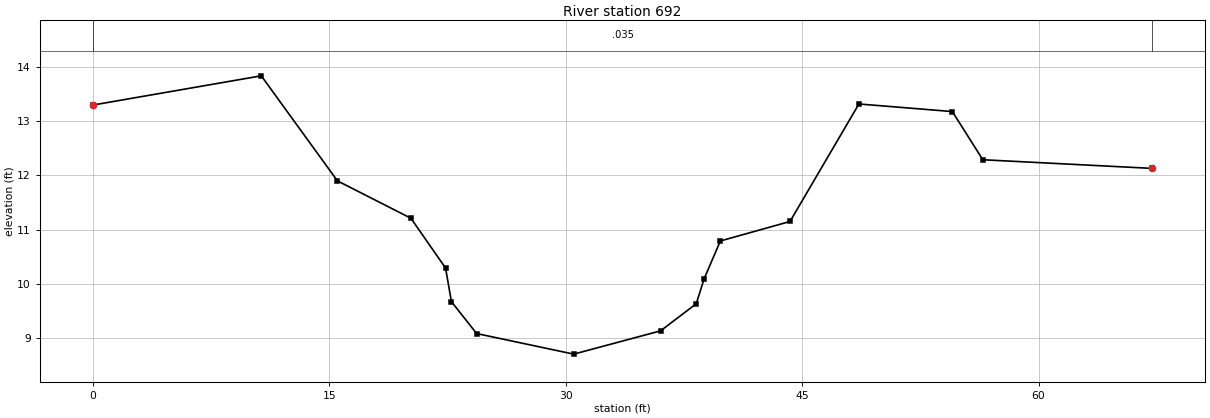
Type RM Length L Ch R = 1 ,692     ,11.67,11.67,11.67
XS GIS Cut Line= 2
       1619254.6      4853571.62      1619269.72      4853637.12
#Sta/Elev= 17
       0 13.2999 10.6899 13.8401 15.5201    11.9 20.1799 11.2099 22.3799   10.29
   22.75  9.6701 24.3499    9.08 30.5099  8.6999   36.02    9.13 38.2801  9.6299
   38.78 10.0901 39.8099 10.7899 44.2301 11.1499 48.6001 13.3201 54.5299 13.1799
 56.4599 12.2901   67.22 12.1301
#Mann= 3 , 0 , 0
       0    .035       0       0    .035       0   67.22    .035       0
Bank Sta=0,67.22
XS Rating Curve= 0
Exp/Cntr=.3,.1