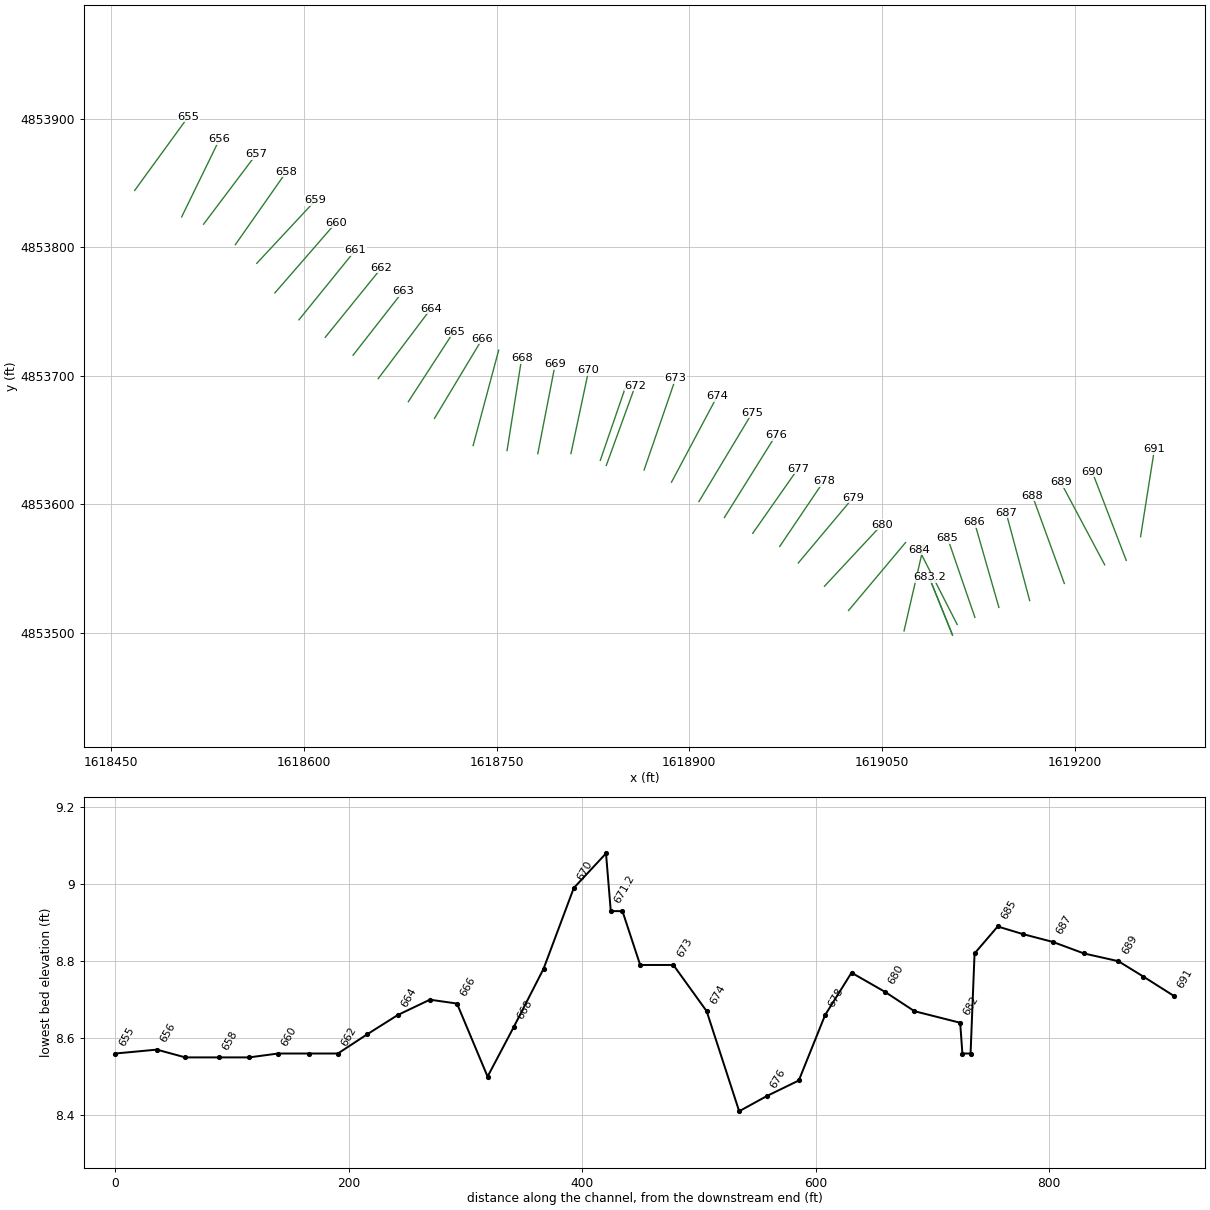
HEC-RAS study ozz_def.prj: ozzeri

--- ozz_def.g02 (geometry) --- (continued)

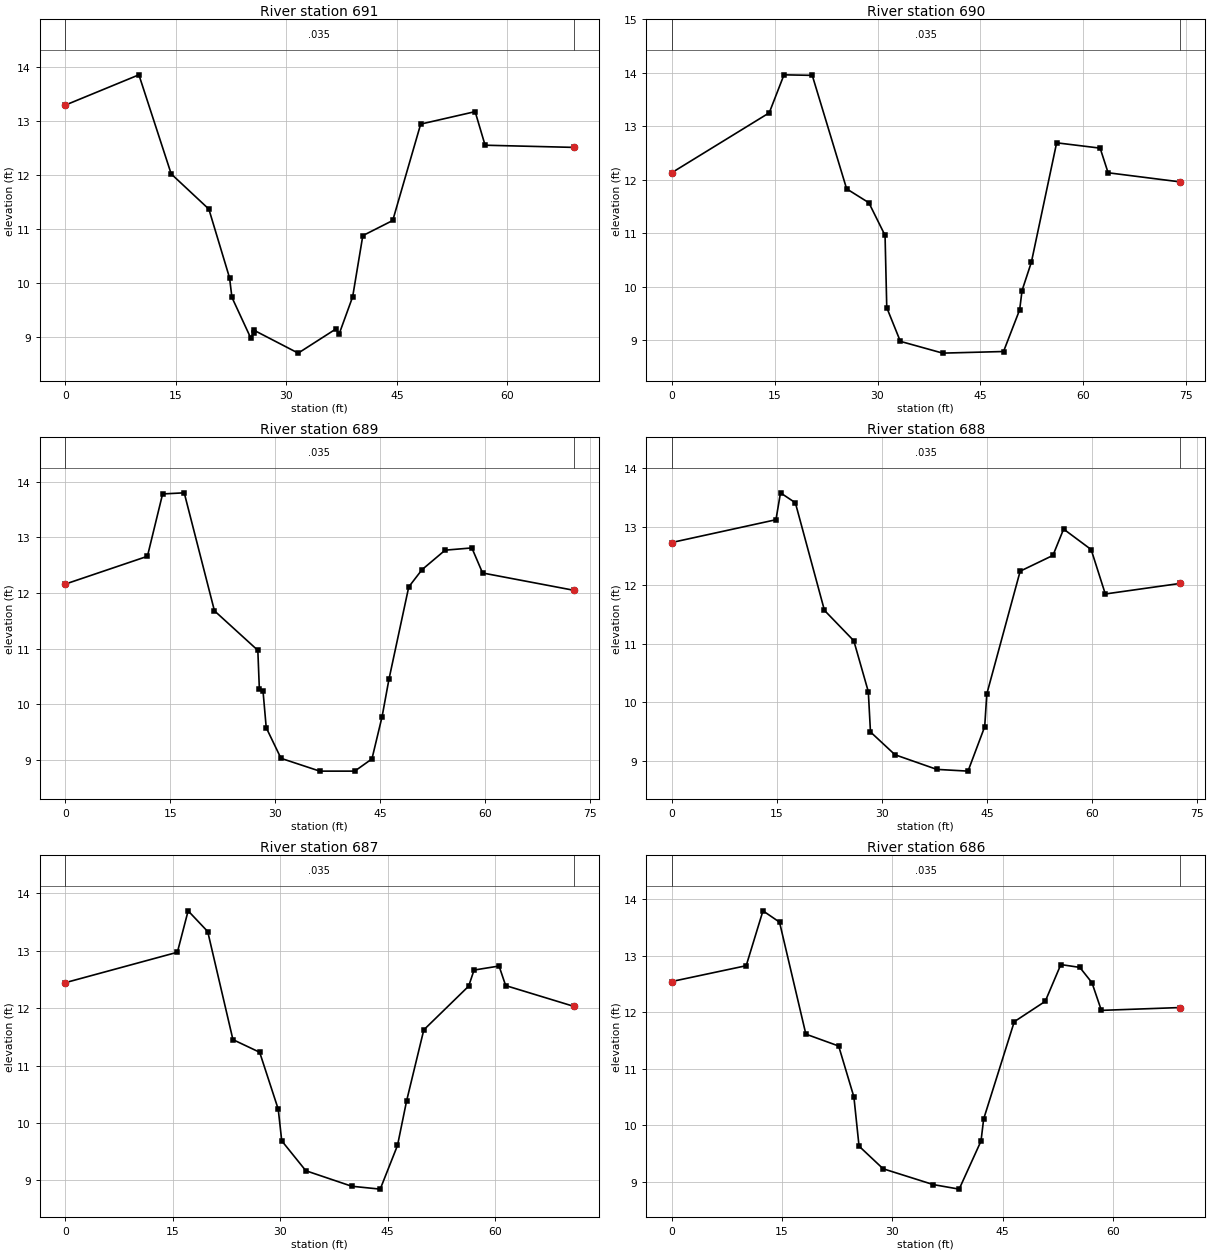
Type RM Length L Ch R = 1 ,691     ,25.99,25.99,25.99
XS GIS Cut Line= 2
      1619251.39      4853574.78      1619262.17       4853642.9
#Sta/Elev= 19
       0 13.2899  9.9999 13.8501 14.3799 12.0201 19.4901   11.37 22.3001 10.0999
 22.6201  9.7399 25.1701  8.9901 25.5599    9.08 25.6501    9.13 31.6099    8.71
 36.7699  9.1598   37.16  9.0599 39.0001  9.7499 40.3799 10.8801 44.4401 11.1599
   48.23   12.94 55.6199 13.1701 56.9699 12.5501 68.9701 12.5099
#Mann= 3 , 0 , 0
       0    .035       0       0    .035       0 68.9701    .035       0
Bank Sta=0,68.9701
XS Rating Curve= 0
Exp/Cntr=.3,.1

Type RM Length L Ch R = 1 ,690     ,21.37,21.37,21.37
XS GIS Cut Line= 2
      1619240.22      4853556.34      1619213.66      4853625.51
#Sta/Elev= 18
       0 12.1301 14.2201   13.25 16.3699 13.9601 20.4899 13.9501 25.4999 11.8299
 28.7399 11.5699    31.1   10.96 31.3499    9.61 33.3299    8.98 39.4999    8.76
 48.3699  8.7901 50.7199  9.5701 51.0699  9.9301 52.4299 10.4601   56.11   12.69
 62.4499 12.5901 63.6099 12.1301 74.0899   11.96
#Mann= 3 , 0 , 0
       0    .035       0       0    .035       0 74.0899    .035       0
Bank Sta=0,74.0899
XS Rating Curve= 0
Exp/Cntr=.3,.1

Type RM Length L Ch R = 1 ,689     ,29.5,29.5,29.5
XS GIS Cut Line= 2
      1619223.45      4853552.93      1619189.34      4853617.08
#Sta/Elev= 21
       0   12.16   11.75 12.6599 13.9199   13.78   17.01 13.8001 21.3299 11.6799
 27.5301 10.9701 27.7499 10.2699 28.2699 10.2401 28.7301  9.5799   30.84    9.03
   36.38  8.7999   41.38  8.7999   43.84  9.0199 45.2899  9.7801 46.2699 10.4501
 49.0999   12.11      51   12.42 54.3001 12.7699 58.1199 12.8101   59.65 12.3599
   72.65   12.05
#Mann= 3 , 0 , 0
       0    .035       0       0    .035       0   72.65    .035       0
Bank Sta=0,72.65
XS Rating Curve= 0
Exp/Cntr=.3,.1

Type RM Length L Ch R = 1 ,688     ,26.58,26.58,26.58
XS GIS Cut Line= 2
      1619192.04      4853538.39      1619167.23      4853606.56
#Sta/Elev= 19
       0   12.73   14.88 13.1201 15.5299 13.5801 17.6501   13.41 21.7999 11.5699
   25.99 11.0499 28.0599   10.18 28.3699  9.4899 31.8699  9.1001 37.8299  8.8499
 42.2901    8.82   44.67  9.5799 44.9699 10.1401 49.7299 12.2399 54.4098 12.5099
 55.9299 12.9601   59.86 12.6099 61.8799   11.85   72.54 12.0302
#Mann= 3 , 0 , 0
       0    .035       0       0    .035       0   72.54    .035       0
Bank Sta=0,72.54
XS Rating Curve= 0
Exp/Cntr=.3,.1

Type RM Length L Ch R = 1 ,687     ,25.37,25.37,25.37
XS GIS Cut Line= 2
      1619165.06      4853525.07       1619146.7      4853593.57
#Sta/Elev= 19
       0 12.4401   15.65 12.9698 17.1499 13.6901   19.88 13.3301 23.4001 11.4501
 27.1299 11.2301 29.7201 10.2401 30.2099  9.6899 33.5701  9.1699   39.98  8.8999
   43.95  8.8499 46.3601    9.61 47.6399   10.39 50.0299 11.6199 56.2899 12.3801
   57.04 12.6599 60.5299   12.73 61.4501 12.3901   70.92 12.0302
#Mann= 3 , 0 , 0
       0    .035       0       0    .035       0   70.92    .035       0
Bank Sta=0,70.92
XS Rating Curve= 0
Exp/Cntr=.3,.1

Type RM Length L Ch R = 1 ,686     ,21.98,21.98,21.98
XS GIS Cut Line= 2
       1619141.1      4853519.76      1619122.05      4853586.18
#Sta/Elev= 20
       0 12.5401   10.13 12.8199 12.4099 13.7901   14.66 13.5901 18.2401 11.6101
    22.7 11.4001 24.7699 10.5001   25.47  9.6299 28.7399    9.23 35.5601  8.9501
 39.0799    8.87 42.0499  9.7201 42.4099 10.1099 46.5701 11.8299   50.78 12.1899
 52.8999   12.84   55.48   12.79 57.1299   12.52   58.41 12.0302    69.1 12.0801
#Mann= 3 , 0 , 0
       0    .035       0       0    .035       0    69.1    .035       0
Bank Sta=0,69.1
XS Rating Curve= 0
Exp/Cntr=.3,.1

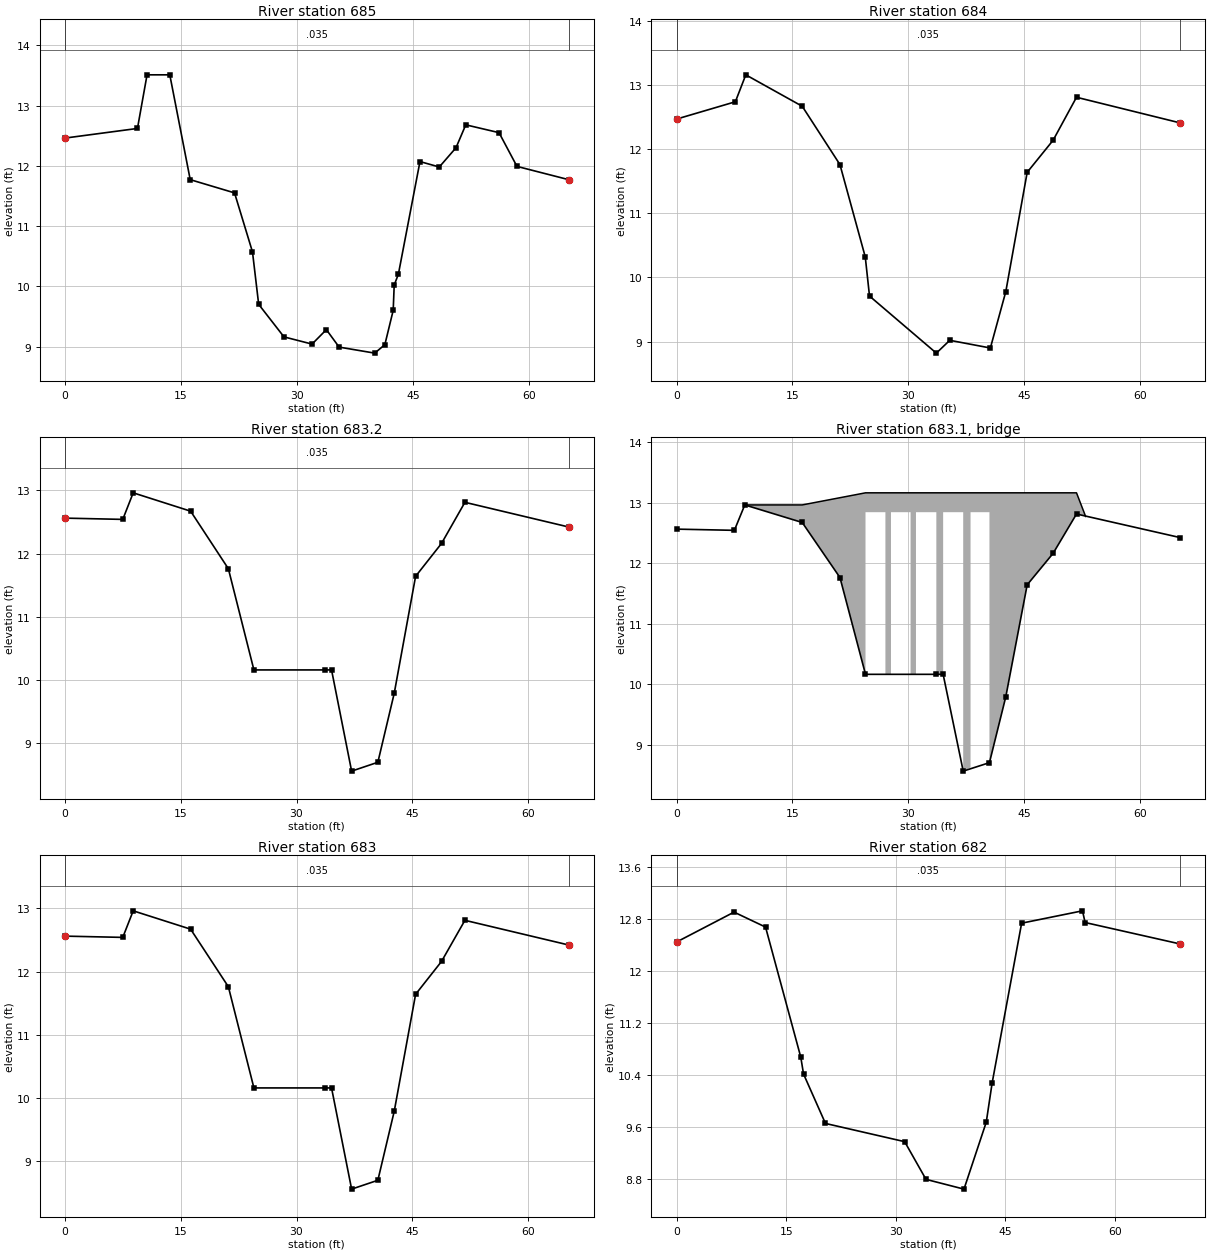
Type RM Length L Ch R = 1 ,685     ,19.82,19.82,19.82
XS GIS Cut Line= 2
      1619122.42      4853511.98      1619101.22      4853573.54
#Sta/Elev= 24
       0 12.4599  9.3699 12.6199 10.6101   13.51 13.5499   13.51 16.1901 11.7699
   21.92 11.5501 24.2401 10.5699 25.0399     9.7 28.3101  9.1598   31.94  9.0401
 33.7901  9.2799   35.44  8.9901 40.0401  8.8901 41.3501    9.03   42.43     9.6
 42.5601   10.02 43.0999 10.2001 45.8901 12.0701   48.39 11.9799 50.5499 12.2999
 51.8099   12.68   56.11 12.5501 58.4299 11.9899 65.1099 11.7699
#Mann= 3 , 0 , 0
       0    .035       0       0    .035       0 65.1099    .035       0
Bank Sta=0,65.1099
XS Rating Curve= 0
Exp/Cntr=.3,.1

Type RM Length L Ch R = 1 ,684     ,3.42,3.42,3.42
XS GIS Cut Line= 2
       1619108.6      4853506.47      1619078.97      4853564.62
#Sta/Elev= 15
       0   12.47    7.62   12.74    8.97   13.16   16.28 12.6699 21.1699 11.7601
 24.4501 10.3199      25    9.71   33.66    8.82 35.4001  9.0199   40.66  8.8999
 42.6601  9.7801 45.4301   11.64 48.7899 12.1399   51.82 12.8101 65.2601 12.4099
#Mann= 3 , 0 , 0
       0    .035       0       0    .035       0 65.2601    .035       0
Bank Sta=0,65.2601
XS Rating Curve= 0
Exp/Cntr=.3,.1

Type RM Length L Ch R = 1 ,683.2   ,7,7,7
XS GIS Cut Line= 2
      1619104.95       4853498.3 1619086.8200372  4853543.169908
#Sta/Elev= 15
       0   12.56    7.49   12.54    8.84   12.96   16.28   12.67   21.17   11.76
   24.48   10.16   33.66   10.16   34.54   10.16   37.14    8.56   40.54     8.7
   42.66    9.79   45.43   11.64   48.79   12.16   51.82   12.81   65.26   12.42
#Mann= 3 , 0 , 0
       0    .035       0       0    .035       0   65.26    .035       0
Bank Sta=0,65.26
XS Rating Curve= 0
Exp/Cntr=.3,.1

Type RM Length L Ch R = 3 ,683.1   ,,,
BEGIN DESCRIPTION:
Cateratte
END DESCRIPTION:
Bridge Culvert--1,0,-1,-1, 0
Deck Dist Width WeirC Skew NumUp NumDn MinLoCord MaxHiCord MaxSubmerge Is_Ogee
.5,6,1.44,0, 27, 27, , , .95, 0, 0,0,,
    8.84   16.28   24.48   24.48   27.06   27.06   27.78   27.78   30.32   30.32
   31.02   31.02   33.66   33.66   34.54   34.54   37.14   37.14   38.09   38.09
   40.54   40.54   42.66   45.43   48.79   51.82      53
   12.96   12.96   13.16   13.16   13.16   13.16   13.16   13.16   13.16   13.16
   13.16   13.16   13.16   13.16   13.16   13.16   13.16   13.16   13.16   13.16
   13.16   13.16   13.16   13.16   13.16   13.16   12.77
   12.96   12.67   10.16   12.84   12.84   10.16   10.16   12.84   12.84   10.16
   10.16   12.84   12.84   10.16   10.16   12.84   12.84    8.56    8.62   12.84
   12.84     8.7    9.79   11.64   12.16   12.81   12.77
    8.84   16.28   24.48   24.48   27.06   27.06   27.78   27.78   30.32   30.32
   31.02   31.02   33.66   33.66   34.54   34.54   37.14   37.14   38.09   38.09
   40.54   40.54   42.66   45.43   48.79   51.82      53
   12.96   12.96   13.16   13.16   13.16   13.16   13.16   13.16   13.16   13.16
   13.16   13.16   13.16   13.16   13.16   13.16   13.16   13.16   13.16   13.16
   13.16   13.16   13.16   13.16   13.16   13.16   12.77
   12.96   12.67   10.16   12.84   12.84   10.16   10.16   12.84   12.84   10.16
   10.16   12.84   12.84   10.16   10.16   12.84   12.84    8.56    8.62   12.84
   12.84     8.7    9.79   11.64   12.16   12.81   12.77
BR Coef=-1 , 0 , 0 ,1.25, 0 ,,,.8,-1,2,0,
WSPro=,,,, 1 ,,,, 0 ,,,, 0 ,,,,-1 ,-1 ,-1 , 0 , 0 , 0 , 0 , 0
BC Design=,, 0 ,, 0 ,,,,,,
BC HTab Sub Flow Pts= 40

Type RM Length L Ch R = 1 ,683     ,1.9,1.9,1.9
XS GIS Cut Line= 2
      1619104.95       4853498.3 1619086.8200372  4853543.169908
#Sta/Elev= 15
       0   12.56    7.49   12.54    8.84   12.96   16.28   12.67   21.17   11.76
   24.48   10.16   33.66   10.16   34.54   10.16   37.14    8.56   40.54     8.7
   42.66    9.79   45.43   11.64   48.79   12.16   51.82   12.81   65.26   12.42
#Mann= 3 , 0 , 0
       0    .035       0       0    .035       0   65.26    .035       0
Bank Sta=0,65.26
XS Rating Curve= 0
Exp/Cntr=.3,.1

Type RM Length L Ch R = 1 ,682     ,39.19,39.19,39.19
XS GIS Cut Line= 2
      1619067.26      4853501.48      1619082.77      4853568.65
#Sta/Elev= 15
       0 12.4401  7.8699 12.9001 12.1801 12.6699 16.9999 10.6701   17.38 10.4101
 20.3801    9.65 31.2201  9.3699   34.14  8.7901 39.3399  8.6399 42.3901  9.6701
 43.1899 10.2699   47.23   12.73 55.5599 12.9199 55.9201   12.74   68.94 12.4099
#Mann= 3 , 0 , 0
       0    .035       0       0    .035       0   68.94    .035       0
Bank Sta=0,68.94
XS Rating Curve= 0
Exp/Cntr=.3,.1

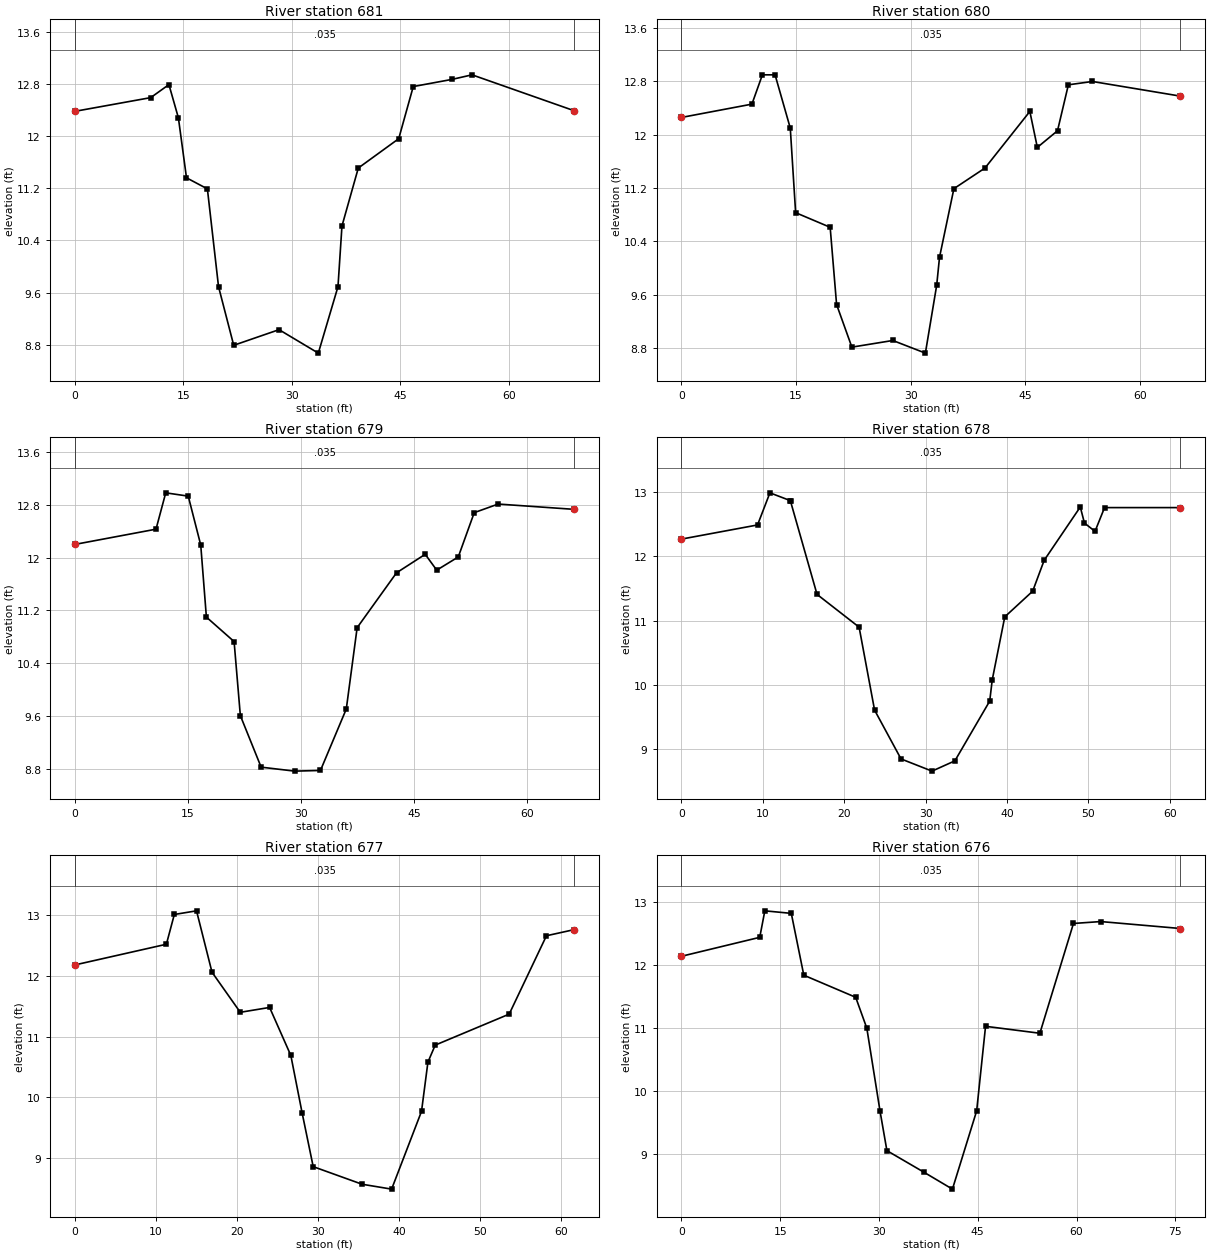
Type RM Length L Ch R = 1 ,681     ,25.13,25.13,25.13
XS GIS Cut Line= 2
      1619024.07      4853517.38      1619068.43      4853570.24
#Sta/Elev= 18
       0 12.3801 10.4699 12.5901   12.99   12.79    14.3 12.2801 15.4201 11.3599
 18.3099 11.1901 19.8501  9.6899 21.9499  8.7901 28.2199    9.03 33.6499    8.67
   36.37  9.6899 36.9201 10.6201 39.1799 11.5099 44.7699   11.96 46.7801 12.7601
   52.14 12.8699   54.91   12.94 69.0101 12.3901
#Mann= 3 , 0 , 0
       0    .035       0       0    .035       0 69.0101    .035       0
Bank Sta=0,69.0101
XS Rating Curve= 0
Exp/Cntr=.3,.1

Type RM Length L Ch R = 1 ,680     ,28.79,28.79,28.79
XS GIS Cut Line= 2
      1619005.32      4853536.26      1619049.85      4853584.02
#Sta/Elev= 21
       0   12.26  9.2199 12.4599   10.59 12.9001 12.2499 12.9001   14.24    12.1
 14.9401 10.8298   19.46 10.6101    20.3    9.45 22.3001  8.8099   27.66  8.9099
 31.9199    8.72    33.4  9.7399   33.77 10.1599   35.65 11.1901   39.72 11.5001
 45.5899 12.3499 46.5701 11.8101   49.21   12.06   50.63 12.7501 53.7801 12.8001
    65.3   12.58
#Mann= 3 , 0 , 0
       0    .035       0       0    .035       0    65.3    .035       0
Bank Sta=0,65.3
XS Rating Curve= 0
Exp/Cntr=.3,.1

Type RM Length L Ch R = 1 ,679     ,22.62,22.62,22.62
XS GIS Cut Line= 2
      1618984.95      4853554.39      1619027.55      4853605.15
#Sta/Elev= 20
       0 12.1999   10.76   12.43   12.05 12.9799 15.0401 12.9299    16.7 12.1899
 17.4501 11.0999   21.13 10.7299 21.9599    9.61 24.7199  8.8301   29.17    8.77
 32.5999  8.7801 36.0301    9.71   37.47 10.9399    42.7 11.7699   46.51   12.05
 48.0401 11.8101 50.9001   12.01   53.02   12.68 56.1999 12.8101 66.2699   12.73
#Mann= 3 , 0 , 0
       0    .035       0       0    .035       0 66.2699    .035       0
Bank Sta=0,66.2699
XS Rating Curve= 0
Exp/Cntr=.3,.1

Type RM Length L Ch R = 1 ,678     ,22.55,22.55,22.55
XS GIS Cut Line= 2
      1618970.47       4853567.2      1619004.76      4853618.04
#Sta/Elev= 21
       0   12.27    9.35 12.4901 10.8701   12.99 13.3499 12.8699 13.3999 12.8601
 16.6601 11.4099 21.8301    10.9 23.7299    9.61   26.98  8.8499   30.79    8.66
 33.5999    8.82 37.8799  9.7499 38.1899   10.08 39.7301   11.06   43.16 11.4599
   44.57 11.9399   49.01 12.7699 49.5199   12.52 50.8199 12.3901   51.99 12.7601
   61.32 12.7601
#Mann= 3 , 0 , 0
       0    .035       0       0    .035       0   61.32    .035       0
Bank Sta=0,61.32
XS Rating Curve= 0
Exp/Cntr=.3,.1

Type RM Length L Ch R = 1 ,677     ,27.05,27.05,27.05
XS GIS Cut Line= 2
      1618949.46      4853577.42      1618984.78      4853627.87
#Sta/Elev= 18
       0 12.1801   11.28   12.52   12.26 13.0101 15.0001 13.0701   16.91   12.06
    20.4 11.4001 24.0201   11.48 26.6401 10.6899 28.0401  9.7399 29.4001  8.8599
   35.44  8.5701 39.0799  8.4899 42.7701  9.7701 43.5599 10.5799   44.46   10.86
 53.5899   11.37   58.19 12.6599   61.59 12.7601
#Mann= 3 , 0 , 0
       0    .035       0       0    .035       0   61.59    .035       0
Bank Sta=0,61.59
XS Rating Curve= 0
Exp/Cntr=.3,.1

Type RM Length L Ch R = 1 ,676     ,24.04,24.04,24.04
XS GIS Cut Line= 2
       1618927.4      4853589.72      1618967.56      4853653.98
#Sta/Elev= 17
       0 12.1399 11.8899 12.4401 12.6599 12.8601 16.6799 12.8199   18.58   11.84
   26.46   11.49 28.1501 10.9999 30.1499  9.6899 31.1999  9.0599   36.79    8.72
 41.1501    8.45   44.83  9.6899 46.1799 11.0301   54.43 10.9201 59.5299 12.6599
   63.67   12.69   75.78   12.58
#Mann= 3 , 0 , 0
       0    .035       0       0    .035       0   75.78    .035       0
Bank Sta=0,75.78
XS Rating Curve= 0
Exp/Cntr=.3,.1

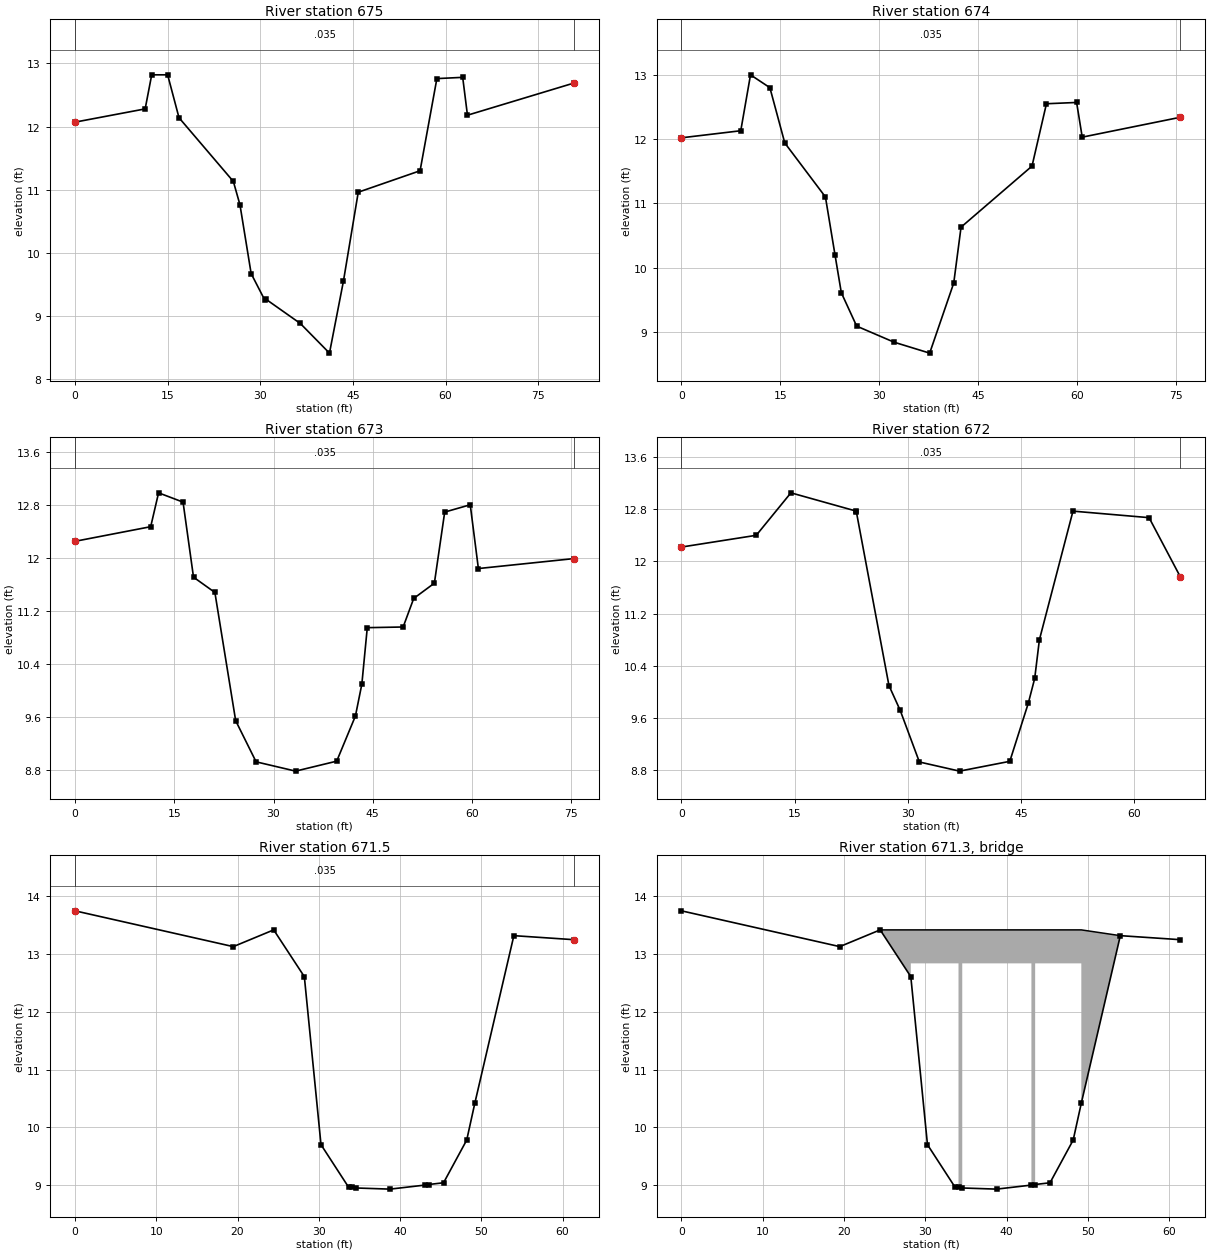
Type RM Length L Ch R = 1 ,675     ,27.86,27.86,27.86
XS GIS Cut Line= 2
      1618907.57      4853602.15      1618949.18       4853671.4
#Sta/Elev= 19
       0 12.0701 11.3599 12.2801   12.42 12.8199 15.0001 12.8199 16.8399 12.1399
 25.6401 11.1301 26.7099   10.76 28.5201  9.6701 30.7299  9.2501 30.9701  9.2601
   36.48    8.88 41.2001    8.41 43.4599    9.55 45.8599   10.96 55.8701 11.2999
 58.5899 12.7601 62.7699   12.78 63.5401 12.1801   80.79   12.69
#Mann= 3 , 0 , 0
       0    .035       0       0    .035       0   80.79    .035       0
Bank Sta=0,80.79
XS Rating Curve= 0
Exp/Cntr=.3,.1

Type RM Length L Ch R = 1 ,674     ,28.53,28.53,28.53
XS GIS Cut Line= 2
      1618886.22      4853617.23      1618921.77       4853684.1
#Sta/Elev= 18
       0 12.0201  9.0001 12.1301 10.4799      13   13.42 12.8001 15.6801 11.9399
 21.8499 11.0999 23.3001 10.2001 24.2599    9.61 26.5901  9.0901 32.2701  8.8401
 37.6699    8.67 41.3199    9.76   42.43 10.6299 53.2001   11.58 55.3901 12.5501
   59.97   12.57 60.8201 12.0302   75.73 12.3401
#Mann= 3 , 0 , 0
       0    .035       0       0    .035       0   75.73    .035       0
Bank Sta=0,75.73
XS Rating Curve= 0
Exp/Cntr=.3,.1

Type RM Length L Ch R = 1 ,673     ,28.44,28.44,28.44
XS GIS Cut Line= 2
      1618864.89      4853626.72      1618889.44      4853698.02
#Sta/Elev= 20
       0 12.2499 11.4401   12.47   12.63 12.9799   16.33   12.84   17.91 11.7101
   21.14   11.48 24.2801    9.55 27.3701    8.93 33.3399  8.7901 39.5499  8.9401
   42.38  9.6201 43.3499 10.0999 44.1701 10.9499   49.59   10.96 51.1899 11.3901
 54.3099 11.6199 55.8701   12.69 59.7301 12.8001   60.96   11.84   75.41 11.9899
#Mann= 3 , 0 , 0
       0    .035       0       0    .035       0   75.41    .035       0
Bank Sta=0,75.41
XS Rating Curve= 0
Exp/Cntr=.3,.1

Type RM Length L Ch R = 1 ,672     ,15.18,15.18,15.18
XS GIS Cut Line= 2
      1618835.45      4853630.29      1618858.06      4853692.41
#Sta/Elev= 16
       0   12.22    9.91 12.3999 14.4999   13.05 23.1599 12.7699   23.17 12.7601
 27.4899 10.0999 28.9801  9.7201   31.52    8.93   36.84  8.7901 43.5001  8.9401
 45.9501  9.8301 46.7999 10.2099 47.4199    10.8 51.8699 12.7699   61.95 12.6699
 66.1099 11.7601
#Mann= 3 , 0 , 0
       0    .035       0       0    .035       0 66.1099    .035       0
Bank Sta=0,66.1099
XS Rating Curve= 0
Exp/Cntr=.3,.1

Type RM Length L Ch R = 1 ,671.5   ,10,10,10
#Sta/Elev= 16
       0   13.75   19.48   13.13   24.45   13.42   28.22   12.61   30.27     9.7
   33.68    8.96   34.09    8.96   34.55    8.95   38.77    8.93   43.06       9
   43.52    9.01   45.35    9.04    48.2    9.78    49.2   10.42      54   13.32
    61.4   13.25
#Mann= 3 , 0 , 0
       0    .035       0       0    .035       0    61.4    .035       0
Bank Sta=0,61.4
XS Rating Curve= 0
Exp/Cntr=.3,.1

Type RM Length L Ch R = 3 ,671.3   ,,,
BEGIN DESCRIPTION:
Ponte di ferro
END DESCRIPTION:
Bridge Culvert--1,0,-1,-1, 0
Deck Dist Width WeirC Skew NumUp NumDn MinLoCord MaxHiCord MaxSubmerge Is_Ogee
.5,9,1.44,0, 14, 14, , , .95, 0, 0,0,,
   24.45   28.22   28.22   34.09   34.09   34.55   34.55   43.06   43.06   43.52
   43.52    49.2    49.2      54
   13.42   13.42   13.42   13.42   13.42   13.42   13.42   13.42   13.42   13.42
   13.42   13.42   13.42   13.32
   13.42   10.64   12.84   12.84    8.96    8.95   12.84   12.84       9    9.01
   12.84   12.84   10.42   13.32
   24.45   28.22   28.22   34.09   34.09   34.55   34.55   43.06   43.06   43.52
   43.52    49.2    49.2      54
   13.42   13.42   13.42   13.42   13.42   13.42   13.42   13.42   13.42   13.42
   13.42   13.42   13.42   13.32
   13.42   10.64   12.84   12.84    8.96    8.95   12.84   12.84       9    9.01
   12.84   12.84   10.42   13.32
BR Coef=-1 , 0 , 0 ,1.25, 0 ,,,.8,-1,2,0,
WSPro=,,,, 1 ,,,, 0 ,,,, 0 ,,,,-1 ,-1 ,-1 , 0 , 0 , 0 , 0 , 0
BC Design=,, 0 ,, 0 ,,,,,,
BC HTab Sub Flow Pts= 40

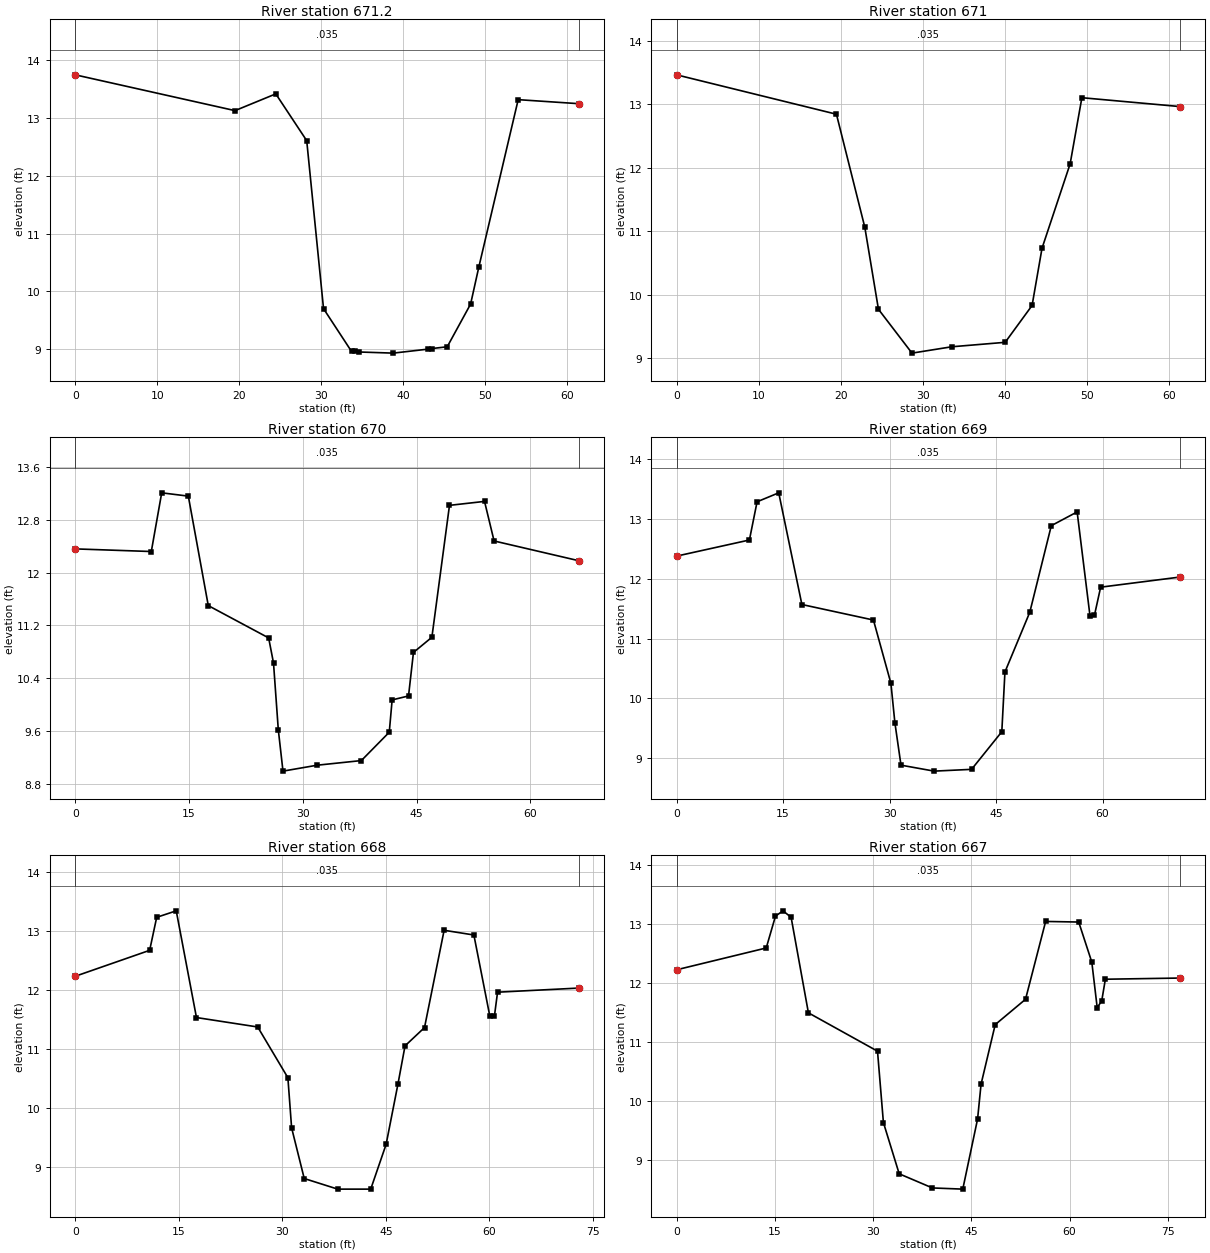
Type RM Length L Ch R = 1 ,671.2   ,4.1,4.1,4.1
#Sta/Elev= 16
       0   13.75   19.48   13.13   24.45   13.42   28.22   12.61   30.27     9.7
   33.68    8.96   34.09    8.96   34.55    8.95   38.77    8.93   43.06       9
   43.52    9.01   45.35    9.04    48.2    9.78    49.2   10.42      54   13.32
    61.4   13.25
#Mann= 3 , 0 , 0
       0    .035       0       0    .035       0    61.4    .035       0
Bank Sta=0,61.4
XS Rating Curve= 0
Exp/Cntr=.3,.1

Type RM Length L Ch R = 1 ,671     ,27.6,27.6,27.6
XS GIS Cut Line= 2
       1618830.8      4853634.26      1618850.79      4853692.31
#Sta/Elev= 12
       0   13.46 19.4901   12.84 22.9499   11.06 24.6099  9.7701    28.7    9.08
 33.5499    9.18 40.0599  9.2501 43.3401  9.8301 44.5499 10.7299 47.9801   12.06
 49.4099    13.1 61.4001 12.9601
#Mann= 3 , 0 , 0
       0    .035       0       0    .035       0 61.4001    .035       0
Bank Sta=0,61.4001
XS Rating Curve= 0
Exp/Cntr=.3,.1

Type RM Length L Ch R = 1 ,670     ,25.91,25.91,25.91
XS GIS Cut Line= 2
      1618807.94       4853639.5      1618821.75      4853704.45
#Sta/Elev= 20
       0 12.3599 10.0301   12.32 11.4001   13.21 14.9099   13.16   17.54 11.5001
 25.4999   11.01   26.14 10.6299   26.77  9.6201 27.3899  8.9901 31.9001    9.08
 37.7199  9.1501 41.4001  9.5799 41.7799   10.07   43.94   10.13 44.5901 10.7899
   47.02   11.02 49.3401 13.0201   53.96 13.0799   55.22   12.48 66.4001 12.1801
#Mann= 3 , 0 , 0
       0    .035       0       0    .035       0 66.4001    .035       0
Bank Sta=0,66.4001
XS Rating Curve= 0
Exp/Cntr=.3,.1

Type RM Length L Ch R = 1 ,669     ,25.31,25.31,25.31
XS GIS Cut Line= 2
      1618782.13      4853639.42      1618795.67      4853709.06
#Sta/Elev= 20
       0 12.3801 10.2599 12.6501 11.3401 13.2899 14.3899 13.4399 17.6501 11.5699
 27.7301 11.3099 30.1901 10.2501 30.7501  9.5899 31.6099    8.88   36.28  8.7801
   41.55  8.8099 45.8099    9.44   46.25   10.44 49.7501 11.4401 52.7801   12.89
   56.42 13.1201   58.24   11.37 58.8599 11.3901 59.7301 11.8601 70.9401 12.0302
#Mann= 3 , 0 , 0
       0    .035       0       0    .035       0 70.9401    .035       0
Bank Sta=0,70.9401
XS Rating Curve= 0
Exp/Cntr=.3,.1

Type RM Length L Ch R = 1 ,668     ,22.64,22.64,22.64
XS GIS Cut Line= 2
       1618758.2      4853641.84      1618769.62      4853713.89
#Sta/Elev= 21
       0 12.2399 10.7799   12.68    11.8 13.2399 14.6301 13.3499 17.5601   11.54
 26.4301   11.38    30.8 10.5199 31.3401  9.6701 33.1699  8.8099 38.0201  8.6301
    42.8  8.6301 45.0299    9.39 46.7399 10.4101 47.7701   11.06 50.5901   11.37
 53.4299 13.0201 57.7401   12.94 60.0401 11.5699 60.7201 11.5699   61.17 11.9701
 72.9499 12.0399
#Mann= 3 , 0 , 0
       0    .035       0       0    .035       0 72.9499    .035       0
Bank Sta=0,72.9499
XS Rating Curve= 0
Exp/Cntr=.3,.1

Type RM Length L Ch R = 1 ,667     ,26.22,26.22,26.22
XS GIS Cut Line= 2
      1618731.78      4853645.72      1618751.69        4853720.
#Sta/Elev= 22
       0   12.22 13.6901 12.5901 15.1001 13.1299 16.2501 13.2201   17.49 13.1101
 20.1299   11.49 30.6799 10.8399   31.58  9.6299 33.9901    8.76 39.0601  8.5201
 43.7001     8.5 45.9599  9.6899 46.4899   10.28   48.65 11.2901   53.28 11.7199
 56.3499   13.04 61.4001 13.0299 63.3999 12.3499 64.2201   11.58 64.9099   11.69
 65.4701   12.06 76.9001 12.0801
#Mann= 3 , 0 , 0
       0    .035       0       0    .035       0 76.9001    .035       0
Bank Sta=0,76.9001
XS Rating Curve= 0
Exp/Cntr=.3,.1

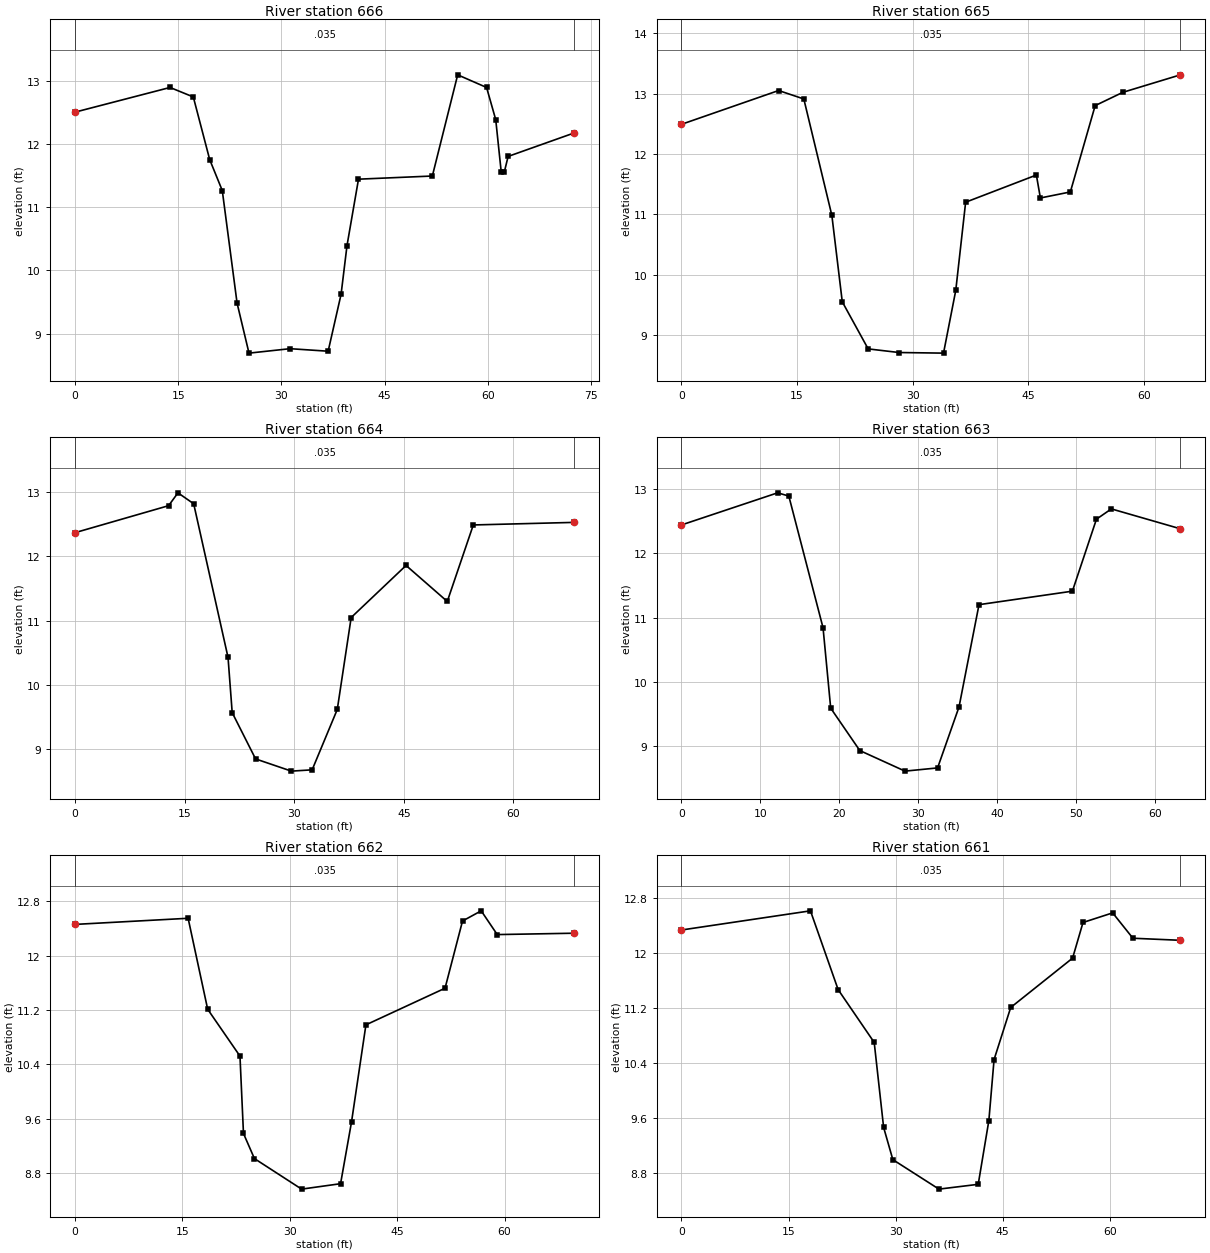
Type RM Length L Ch R = 1 ,666     ,23.22,23.22,23.22
XS GIS Cut Line= 2
      1618701.73      4853666.93      1618739.07      4853729.08
#Sta/Elev= 20
       0 12.4998 13.8099   12.89 17.1901   12.74   19.57   11.75    21.4 11.2599
 23.5501  9.4799 25.2801  8.6898 31.2499    8.76 36.7799    8.72 38.6599  9.6201
 39.5201   10.39 41.1901 11.4401 51.9199   11.49 55.6001 13.0899 59.7999   12.89
 61.1301 12.3801 61.9201 11.5601 62.3901 11.5601 62.9299    11.8    72.5 12.1701
#Mann= 3 , 0 , 0
       0    .035       0       0    .035       0    72.5    .035       0
Bank Sta=0,72.5
XS Rating Curve= 0
Exp/Cntr=.3,.1

Type RM Length L Ch R = 1 ,665     ,27.53,27.53,27.53
XS GIS Cut Line= 2
      1618681.39      4853679.98      1618716.66      4853734.29
#Sta/Elev= 16
       0 12.4901 12.6099   13.05 15.8801 12.9101   19.52 10.9801   20.87    9.55
 24.2301    8.77   28.24    8.71 34.0099  8.6999    35.6  9.7399 36.8799 11.1999
 46.0599 11.6501 46.5801   11.27   50.47   11.37 53.6899 12.8001 57.2798 13.0201
 64.7599   13.31
#Mann= 3 , 0 , 0
       0    .035       0       0    .035       0 64.7599    .035       0
Bank Sta=0,64.7599
XS Rating Curve= 0
Exp/Cntr=.3,.1

Type RM Length L Ch R = 1 ,664     ,26.15,26.15,26.15
XS GIS Cut Line= 2
      1618657.91      4853697.88        1618699.      4853752.41
#Sta/Elev= 15
       0   12.37 12.8101   12.79   14.09   12.99   16.24 12.8199 20.9401   10.43
   21.51  9.5701 24.7101  8.8499 29.6101    8.66 32.4499  8.6801 35.8899  9.6201
   37.79 11.0499    45.3 11.8601   50.94 11.2999 54.5001 12.4901 68.2801   12.53
#Mann= 3 , 0 , 0
       0    .035       0       0    .035       0 68.2801    .035       0
Bank Sta=0,68.2801
XS Rating Curve= 0
Exp/Cntr=.3,.1

Type RM Length L Ch R = 1 ,663     ,25.14,25.14,25.14
XS GIS Cut Line= 2
      1618638.34       4853716.1      1618677.29      4853765.95
#Sta/Elev= 14
       0 12.4401 12.1899   12.94 13.6099   12.89   17.95 10.8399 18.9199  9.5899
 22.6101    8.93   28.34    8.61   32.47    8.66 35.1901    9.61 37.7199 11.1999
 49.5599 11.4099   52.61   12.53 54.5001   12.69   63.26 12.3801
#Mann= 3 , 0 , 0
       0    .035       0       0    .035       0   63.26    .035       0
Bank Sta=0,63.26
XS Rating Curve= 0
Exp/Cntr=.3,.1

Type RM Length L Ch R = 1 ,662     ,24.58,24.58,24.58
XS GIS Cut Line= 2
      1618616.67      4853730.03      1618660.53      4853784.19
#Sta/Elev= 15
       0 12.4599 15.7999 12.5501   18.53 11.2099 23.0401 10.5199 23.5299  9.3799
   25.06  9.0099 31.6501    8.56 37.0899  8.6399   38.62    9.55 40.6301 10.9801
 51.6801 11.5199   54.12 12.5099   56.73 12.6599   58.97   12.31 69.6901 12.3301
#Mann= 3 , 0 , 0
       0    .035       0       0    .035       0 69.6901    .035       0
Bank Sta=0,69.6901
XS Rating Curve= 0
Exp/Cntr=.3,.1

Type RM Length L Ch R = 1 ,661     ,26.67,26.67,26.67
XS GIS Cut Line= 2
      1618596.21      4853743.65       1618640.2      4853797.97
#Sta/Elev= 16
       0 12.3401 18.0701 12.6199 21.9499 11.4699 27.0001    10.7 28.3199  9.4601
 29.6101  8.9901   36.07    8.56 41.5701  8.6301   43.06  9.5601   43.79 10.4501
 46.1199 11.2099 54.7899 11.9299 56.2499 12.4499 60.4001 12.5901 63.2399   12.22
 69.9001 12.1899
#Mann= 3 , 0 , 0
       0    .035       0       0    .035       0 69.9001    .035       0
Bank Sta=0,69.9001
XS Rating Curve= 0
Exp/Cntr=.3,.1

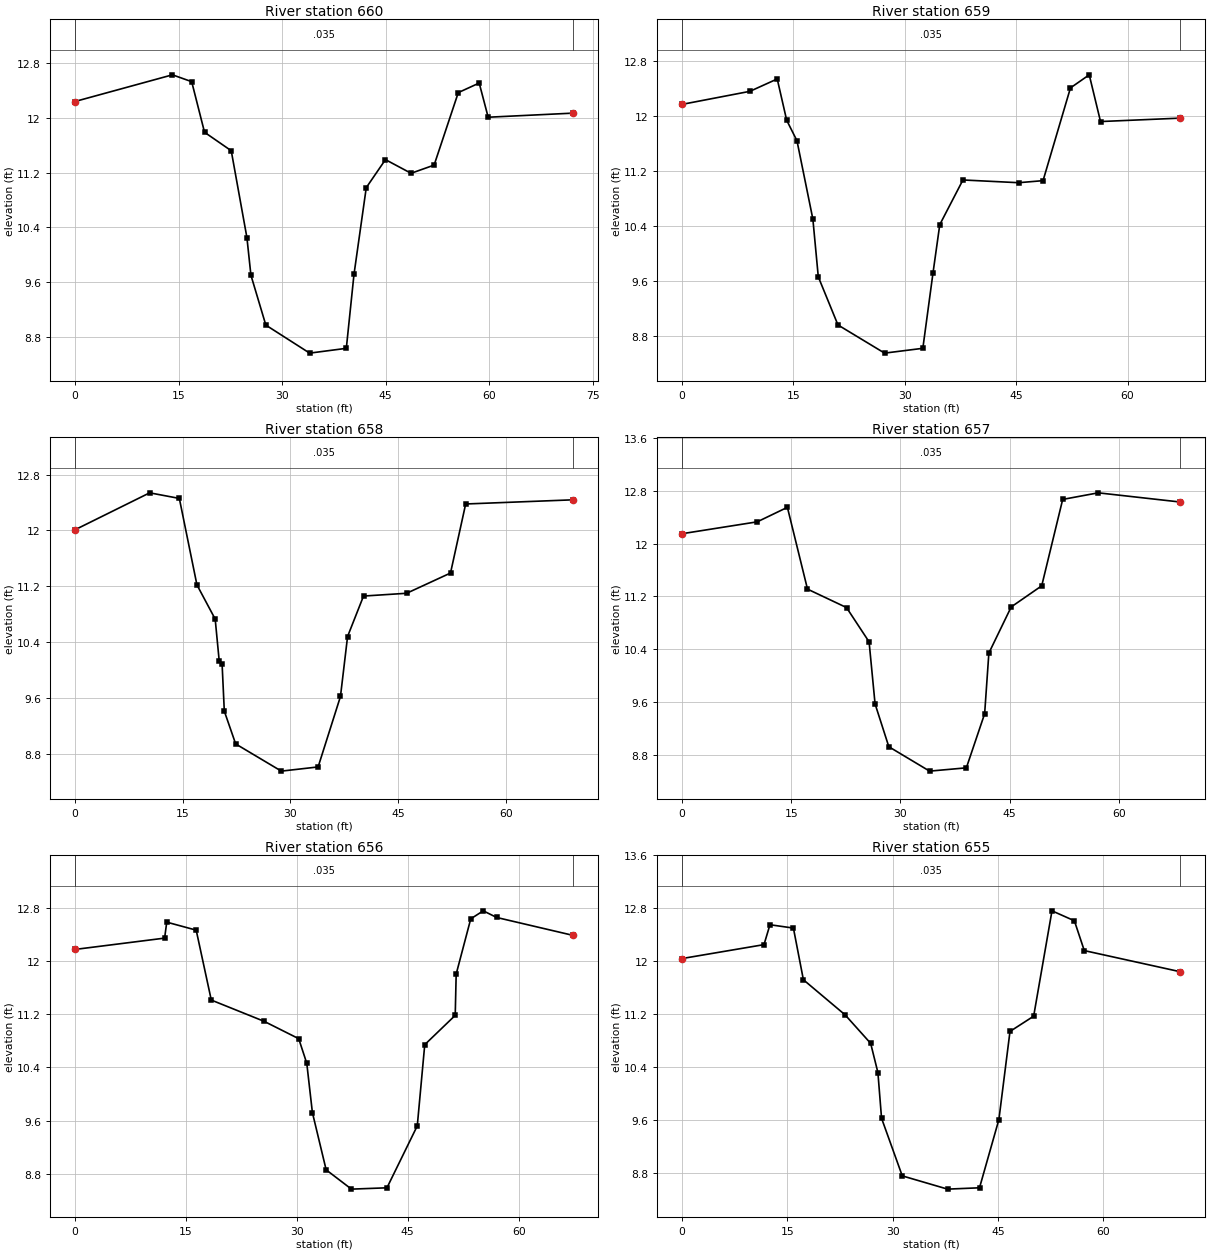
Type RM Length L Ch R = 1 ,660     ,24.85,24.85,24.85
XS GIS Cut Line= 2
      1618577.48      4853764.61      1618624.85      4853819.11
#Sta/Elev= 19
       0 12.2399 14.1199   12.63   16.91   12.53 18.7699   11.79 22.6399 11.5199
 24.9101 10.2501 25.4901     9.7 27.6499    8.97 34.0001    8.56 39.3101  8.6301
 40.4201    9.71 42.1999 10.9801 44.9799 11.3901   48.69 11.1901   52.03 11.3099
   55.53   12.37   58.56 12.5099   59.86   12.01 72.2099 12.0701
#Mann= 3 , 0 , 0
       0    .035       0       0    .035       0 72.2099    .035       0
Bank Sta=0,72.2099
XS Rating Curve= 0
Exp/Cntr=.3,.1

Type RM Length L Ch R = 1 ,659     ,26.07,26.07,26.07
XS GIS Cut Line= 2
      1618563.37      4853787.62      1618609.15      4853836.72
#Sta/Elev= 19
       0 12.1701    9.14 12.3599 12.8199 12.5401   14.09 11.9399 15.4799   11.64
 17.6199 10.5001 18.3499    9.66 21.0001  8.9599 27.2799  8.5499 32.4301    8.62
 33.7901    9.71   34.71 10.4199 37.8299   11.07 45.3299 11.0301 48.6199   11.06
 52.3101 12.4099 54.8399 12.6001   56.36 11.9201 67.1301 11.9701
#Mann= 3 , 0 , 0
       0    .035       0       0    .035       0 67.1301    .035       0
Bank Sta=0,67.1301
XS Rating Curve= 0
Exp/Cntr=.3,.1

Type RM Length L Ch R = 1 ,658     ,28.55,28.55,28.55
XS GIS Cut Line= 2
      1618546.67       4853802.1      1618586.47      4853858.94
#Sta/Elev= 18
       0   12.01 10.4001 12.5401 14.5301 12.4599 16.9801   11.22   19.52 10.7299
 20.0799   10.13 20.4801 10.0901 20.7901  9.4101 22.3699  8.9401 28.7301  8.5499
 33.8499    8.61   36.96  9.6201   37.95 10.4799 40.1699   11.06 46.1699 11.0999
 52.2799 11.3901   54.39 12.3801 69.3899 12.4401
#Mann= 3 , 0 , 0
       0    .035       0       0    .035       0 69.3899    .035       0
Bank Sta=0,69.3899
XS Rating Curve= 0
Exp/Cntr=.3,.1

Type RM Length L Ch R = 1 ,657     ,24.44,24.44,24.44
XS GIS Cut Line= 2
      1618521.97       4853818.1      1618563.17      4853872.78
#Sta/Elev= 17
       0 12.1499   10.33 12.3301 14.4701 12.5501   17.23 11.3099 22.5899 11.0301
 25.6901 10.5101   26.51  9.5701    28.4    8.92 34.0001  8.5499 39.0501  8.5999
 41.5601  9.4201 42.1401   10.34 45.2101 11.0399 49.4002 11.3599 52.2799 12.6699
 57.1601 12.7699 68.4599   12.63
#Mann= 3 , 0 , 0
       0    .035       0       0    .035       0 68.4599    .035       0
Bank Sta=0,68.4599
XS Rating Curve= 0
Exp/Cntr=.3,.1

Type RM Length L Ch R = 1 ,656     ,35.48,35.48,35.48
XS GIS Cut Line= 2
       1618504.9      4853823.76      1618534.44      4853884.33
#Sta/Elev= 20
       0 12.1701 12.1201 12.3401 12.4099   12.58   16.39 12.4599   18.43 11.4099
   25.58 11.0901 30.2499 10.8298 31.3401 10.4601    32.1  9.7201 33.9599  8.8599
 37.3801  8.5701 42.1801  8.5899 46.2799  9.5201   47.29 10.7399   51.41 11.1801
 51.5398    11.8 53.5101   12.63 55.1999 12.7501 57.0199 12.6501 67.3901 12.3801
#Mann= 3 , 0 , 0
       0    .035       0       0    .035       0 67.3901    .035       0
Bank Sta=0,67.3901
XS Rating Curve= 0
Exp/Cntr=.3,.1

Type RM Length L Ch R = 1 ,655     ,26.75,26.75,26.75
XS GIS Cut Line= 2
       1618468.3      4853844.31      1618510.02      4853901.73
#Sta/Elev= 19
       0 12.0399 11.6699 12.2499   12.52 12.5501   15.86 12.4998   17.28 11.7199
   23.22 11.1901 26.8599   10.76 27.8901 10.3199 28.4101  9.6299   31.36    8.76
 37.8101    8.56 42.3599  8.5801 45.1199    9.61 46.6999 10.9399 50.0701   11.17
 52.6801 12.7601 55.8701 12.6099 57.2798   12.16   70.98   11.84
#Mann= 3 , 0 , 0
       0    .035       0       0    .035       0   70.98    .035       0
Bank Sta=0,70.98
XS Rating Curve= 0
Exp/Cntr=.3,.1