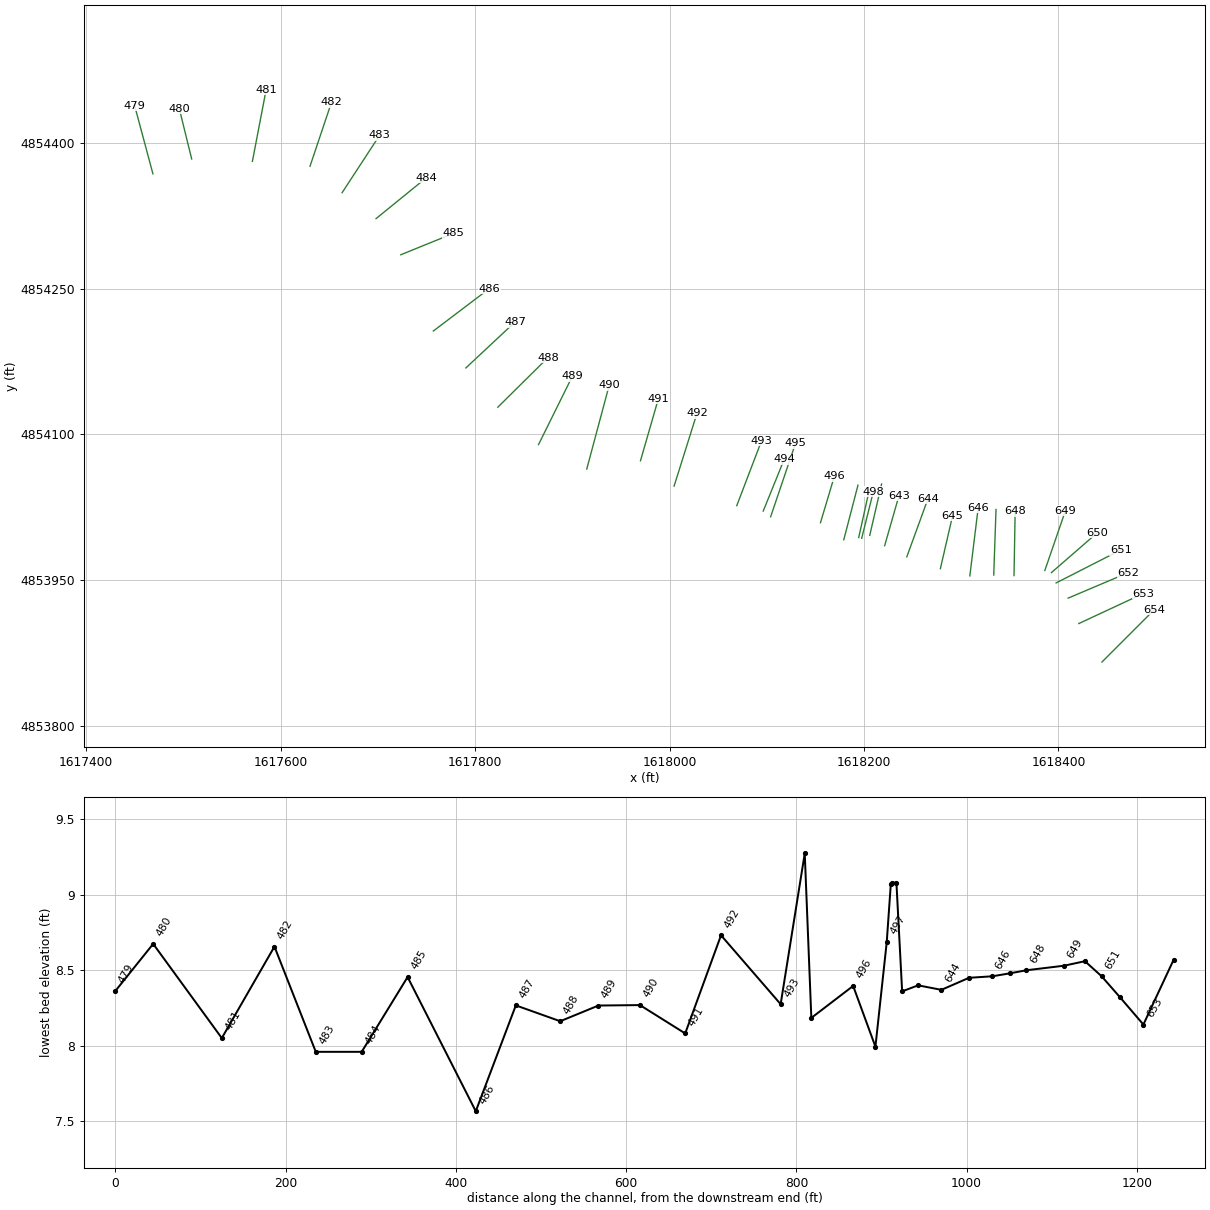
HEC-RAS study ozz_def.prj: ozzeri

--- ozz_def.g02 (geometry) --- (continued)

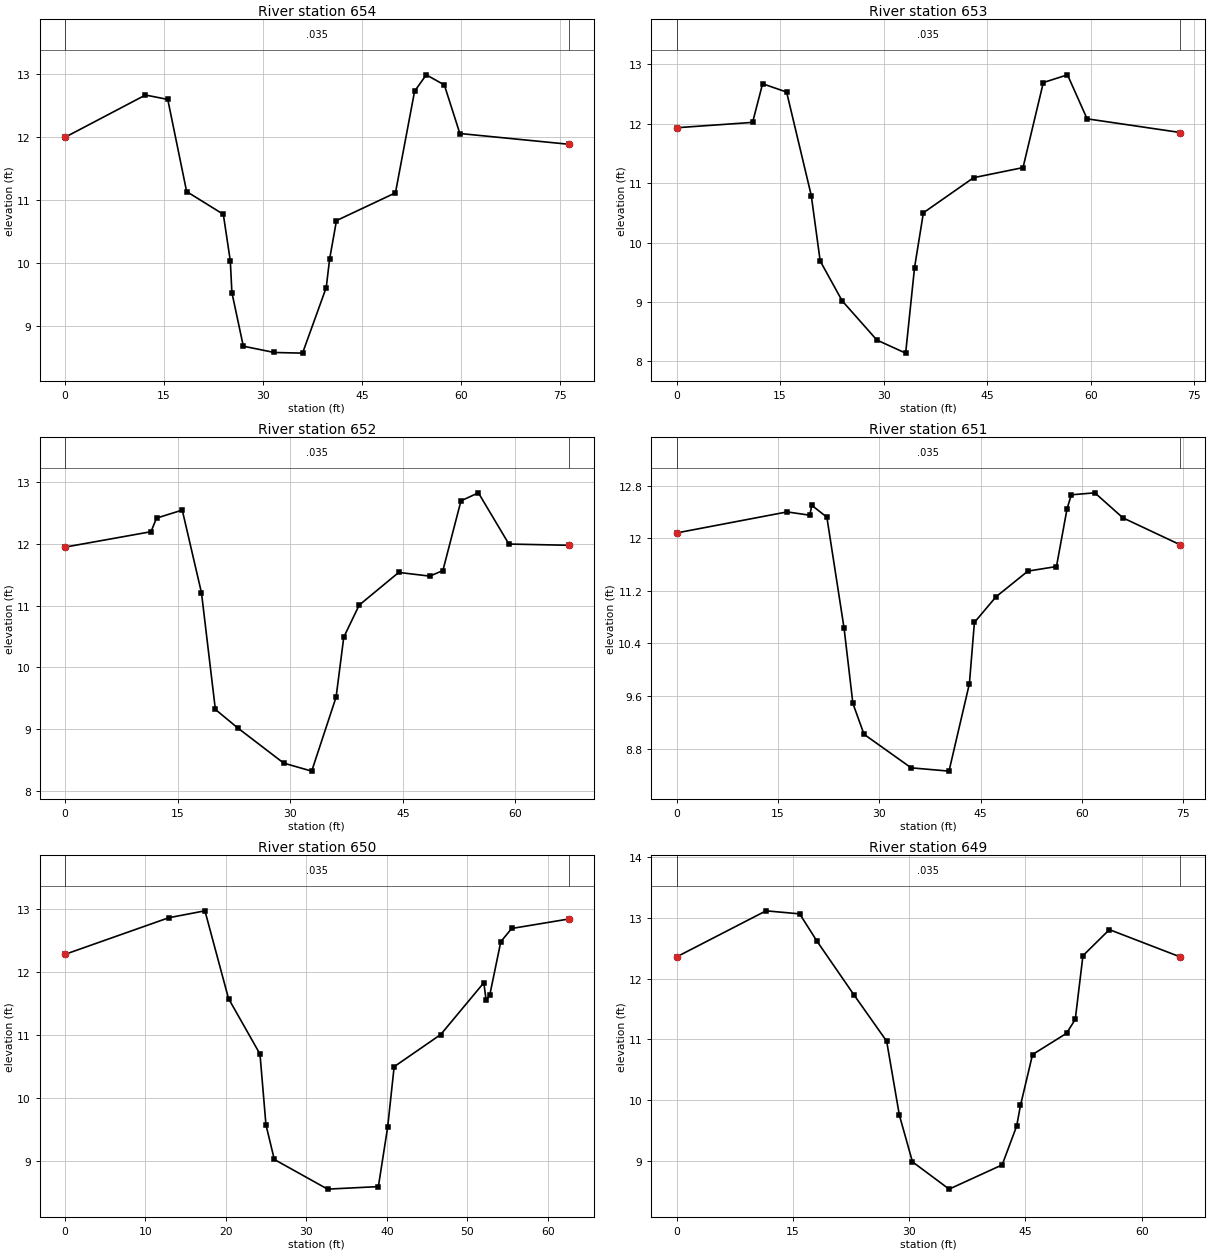
Type RM Length L Ch R = 1 ,654     ,35.56,35.56,35.56
XS GIS Cut Line= 2
      1618444.81      4853865.89      1618498.79      4853919.87
#Sta/Elev= 19
       0 11.9899 12.1999 12.6599 15.5799 12.5901 18.4401 11.1301      24 10.7701
   25.06 10.0301 25.2999  9.5299   27.03  8.6801   31.73  8.5801   36.01  8.5701
 39.5999    9.61 40.1098 10.0599 41.1501 10.6701 50.0899   11.11 52.9901 12.7199
 54.7601 12.9799 57.4999 12.8199 59.8499   12.05 76.3399 11.8799
#Mann= 3 , 0 , 0
       0    .035       0       0    .035       0 76.3399    .035       0
Bank Sta=0,76.3399
XS Rating Curve= 0
Exp/Cntr=.3,.1

Type RM Length L Ch R = 1 ,653     ,27.38,27.38,27.38
XS GIS Cut Line= 2
      1618421.04      4853905.42      1618487.16      4853936.25
#Sta/Elev= 17
       0 11.9299   11.01 12.0201 12.4599 12.6699 15.9401   12.53 19.5099 10.7899
 20.7999  9.6899 23.9801  9.0199   29.01  8.3601 33.1799    8.14 34.4701  9.5799
   35.75 10.5001 43.0201 11.0901 50.1801 11.2599 53.1199   12.69   56.62 12.8199
 59.4601 12.0801 72.9499   11.85
#Mann= 3 , 0 , 0
       0    .035       0       0    .035       0 72.9499    .035       0
Bank Sta=0,72.9499
XS Rating Curve= 0
Exp/Cntr=.3,.1

Type RM Length L Ch R = 1 ,652     ,21.66,21.66,21.66
XS GIS Cut Line= 2
      1618410.07      4853931.58      1618471.82      4853957.79
#Sta/Elev= 19
       0   11.95 11.4599 12.1999 12.1899   12.42 15.6201 12.5501 18.1801 11.2099
 20.0299  9.3199   23.01  9.0199   29.13    8.45 32.8599  8.3201   36.11  9.5201
 37.1301   10.49 39.1799   11.01 44.4499   11.54   48.59   11.48 50.3301 11.5699
 52.7398 12.7001   55.06 12.8299 59.1199      12 67.0801 11.9799
#Mann= 3 , 0 , 0
       0    .035       0       0    .035       0 67.0801    .035       0
Bank Sta=0,67.0801
XS Rating Curve= 0
Exp/Cntr=.3,.1

Type RM Length L Ch R = 1 ,651     ,19.66,19.66,19.66
XS GIS Cut Line= 2
      1618397.68      4853947.22      1618464.11      4853981.07
#Sta/Elev= 20
       0 12.0801 16.3601 12.3999 19.7199 12.3499 20.0199 12.4998 22.2501   12.32
 24.8001 10.6299    26.1  9.4899 27.7499  9.0199 34.7301    8.51 40.3299    8.46
 43.3499  9.7899 44.0899 10.7201   47.29   11.11 52.0099 11.5001 56.2399 11.5699
 57.8099 12.4499 58.4399 12.6599 61.9201   12.69   66.07   12.31 74.5599    11.9
#Mann= 3 , 0 , 0
       0    .035       0       0    .035       0 74.5599    .035       0
Bank Sta=0,74.5599
XS Rating Curve= 0
Exp/Cntr=.3,.1

Type RM Length L Ch R = 1 ,650     ,24.62,24.62,24.62
XS GIS Cut Line= 2
      1618392.86      4853957.84      1618440.09      4853998.89
#Sta/Elev= 18
       0 12.2801   12.89 12.8601 17.3901 12.9698 20.3201   11.58 24.2301    10.7
 24.9701  9.5799 26.0101    9.03 32.6301    8.56   38.94  8.5999   40.09  9.5399
 40.8999 10.5001 46.6899   11.01   52.04 11.8299 52.3299 11.5501   52.77 11.6299
 54.1499   12.48 55.5001   12.69   62.58   12.84
#Mann= 3 , 0 , 0
       0    .035       0       0    .035       0   62.58    .035       0
Bank Sta=0,62.58
XS Rating Curve= 0
Exp/Cntr=.3,.1

Type RM Length L Ch R = 1 ,649     ,44.1,44.1,44.1
XS GIS Cut Line= 2
      1618386.06      4853959.99      1618407.22      4854021.42
#Sta/Elev= 18
       0 12.3599   11.54 13.1201 15.8801 13.0701   18.11 12.6199 22.8499   11.74
 27.1001 10.9701 28.7399  9.7499   30.43    8.98 35.1599  8.5301 41.9999    8.93
 43.8699  9.5701   44.36    9.91   45.92   10.75 50.2999 11.0999 51.4301   11.33
 52.4201 12.3801 55.8299 12.8101 64.9699 12.3599
#Mann= 3 , 0 , 0
       0    .035       0       0    .035       0 64.9699    .035       0
Bank Sta=0,64.9699
XS Rating Curve= 0
Exp/Cntr=.3,.1

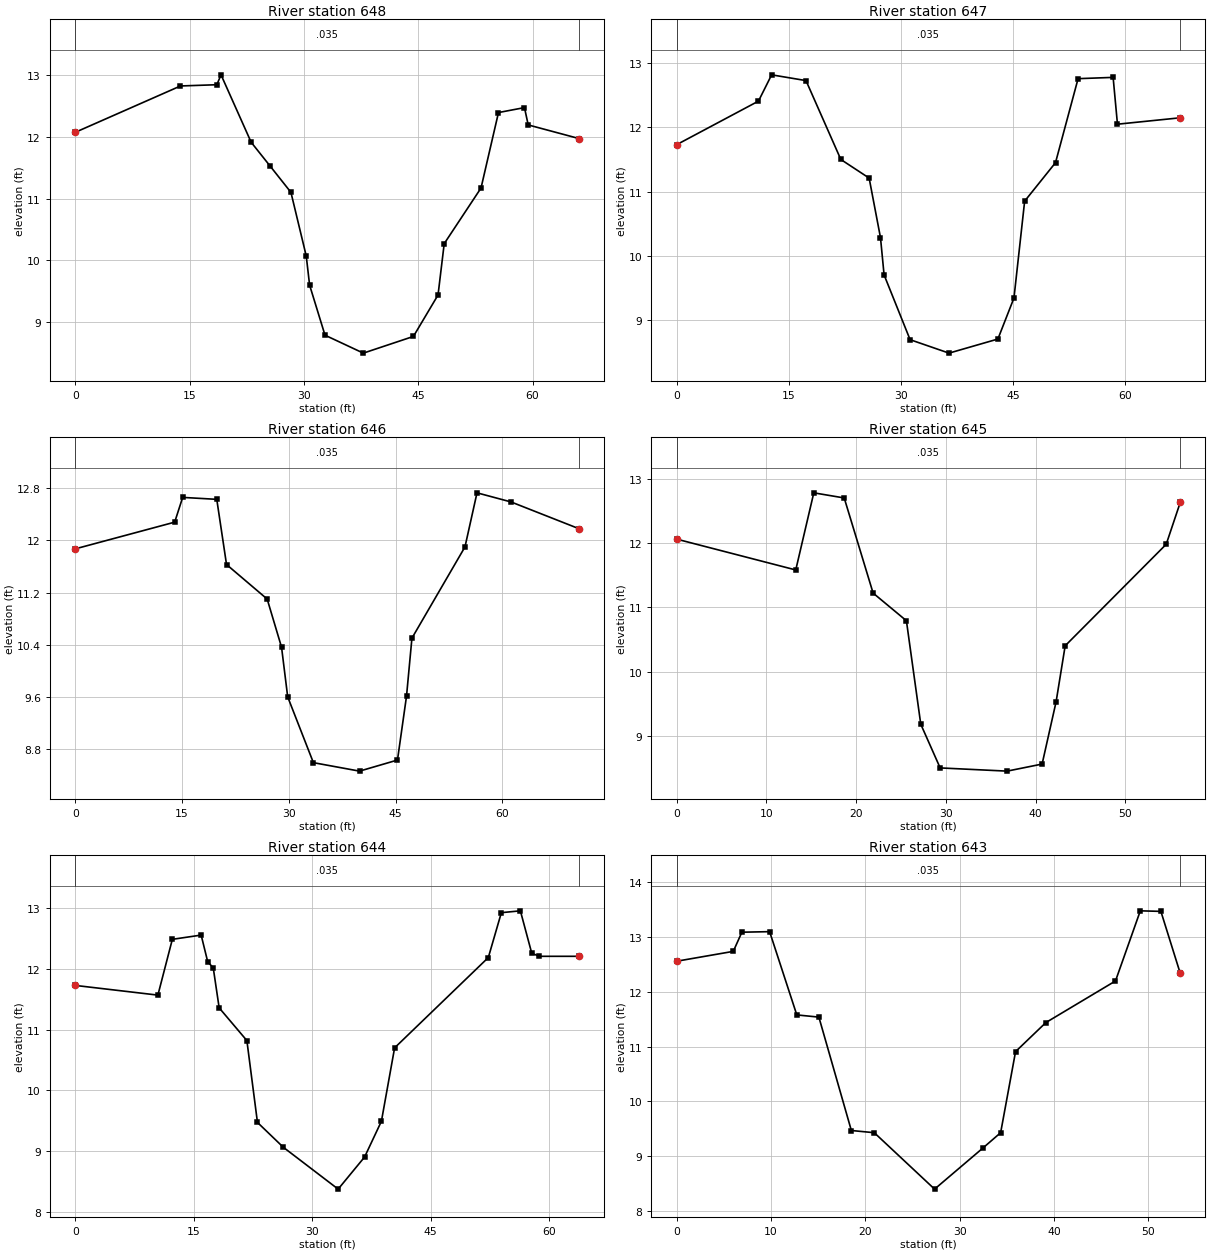
Type RM Length L Ch R = 1 ,648     ,18.96,18.96,18.96
XS GIS Cut Line= 2
      1618354.37      4853954.77      1618355.52      4854020.84
#Sta/Elev= 19
       0 12.0701 13.8099 12.8199   18.58   12.84 19.1299      13 23.0801 11.9101
 25.6002 11.5199 28.3001 11.0999 30.3099   10.07 30.7501     9.6   32.77  8.7901
 37.8001     8.5   44.37    8.77    47.6    9.44 48.4099 10.2699   53.24   11.17
   55.53 12.3901 58.9401   12.47 59.4299 12.1899   66.08 11.9701
#Mann= 3 , 0 , 0
       0    .035       0       0    .035       0   66.08    .035       0
Bank Sta=0,66.08
XS Rating Curve= 0
Exp/Cntr=.3,.1

Type RM Length L Ch R = 1 ,647     ,21.14,21.14,21.14
XS GIS Cut Line= 2
       1618333.5      4853955.37      1618335.85      4854022.73
#Sta/Elev= 18
       0 11.7299   10.96 12.4099 12.7199 12.8199   17.32   12.73   21.98 11.5001
 25.7699 11.2099   27.29   10.28   27.77     9.7 31.2499  8.6898 36.4599  8.4801
      43  8.6999   45.15    9.34 46.5801   10.85 50.7099 11.4501 53.7301 12.7601
 58.4201   12.78 59.0001   12.05 67.4001 12.1499
#Mann= 3 , 0 , 0
       0    .035       0       0    .035       0 67.4001    .035       0
Bank Sta=0,67.4001
XS Rating Curve= 0
Exp/Cntr=.3,.1

Type RM Length L Ch R = 1 ,646     ,27.3,27.3,27.3
XS GIS Cut Line= 2
      1618308.92      4853954.48      1618317.54      4854024.69
#Sta/Elev= 17
       0 11.8701 13.9699 12.2801   15.09 12.6599   19.88   12.63   21.25 11.6299
 26.9599 11.0999 28.9801 10.3602 29.8399     9.6   33.45  8.5899   39.93    8.46
 45.2601  8.6301 46.5299    9.61   47.29 10.5001 54.7399    11.9 56.4301   12.73
 61.2099 12.5901 70.7401 12.1801
#Mann= 3 , 0 , 0
       0    .035       0       0    .035       0 70.7401    .035       0
Bank Sta=0,70.7401
XS Rating Curve= 0
Exp/Cntr=.3,.1

Type RM Length L Ch R = 1 ,645     ,32.51,32.51,32.51
XS GIS Cut Line= 2
      1618278.61      4853961.88      1618291.23      4854016.56
#Sta/Elev= 14
       0   12.06 13.2801   11.58   15.29   12.78   18.68 12.7001 21.8999   11.22
 25.6099 10.7899 27.2101    9.18 29.3699     8.5 36.8299    8.45 40.7301    8.56
 42.2901  9.5299 43.2999 10.4001 54.5601 11.9799 56.1201   12.63
#Mann= 3 , 0 , 0
       0    .035       0       0    .035       0 56.1201    .035       0
Bank Sta=0,56.1201
XS Rating Curve= 0
Exp/Cntr=.3,.1

Type RM Length L Ch R = 1 ,644     ,27.3,27.3,27.3
XS GIS Cut Line= 2
      1618244.09      4853974.04      1618265.91      4854033.98
#Sta/Elev= 20
       0 11.7299 10.4699 11.5699 12.2999 12.4901 15.9499 12.5599 16.7798 12.1201
   17.48 12.0201 18.2301 11.3599 21.7399 10.8201 23.0801  9.4701   26.36  9.0599
    33.3  8.3701 36.6501  8.8999   38.78  9.4899   40.45    10.7 52.3201 12.1899
   53.97 12.9299 56.3801 12.9601   57.82   12.26 58.7901   12.21 63.7901   12.21
#Mann= 3 , 0 , 0
       0    .035       0       0    .035       0 63.7901    .035       0
Bank Sta=0,63.7901
XS Rating Curve= 0
Exp/Cntr=.3,.1

Type RM Length L Ch R = 1 ,643     ,18.81,18.81,18.81
XS GIS Cut Line= 2
      1618221.28      4853985.49      1618235.99      4854036.79
#Sta/Elev= 17
       0 12.5599    6.01   12.74  6.9199 13.0899    9.86    13.1   12.74   11.58
   15.08   11.54   18.52  9.4701 20.9501  9.4299   27.34     8.4   32.46  9.1501
   34.34  9.4299 35.9201   10.91 39.1299 11.4401   46.51 12.1999 49.1399 13.4801
 51.3201   13.47 53.3699 12.3401
#Mann= 3 , 0 , 0
       0    .035       0       0    .035       0 53.3699    .035       0
Bank Sta=0,53.3699
XS Rating Curve= 0
Exp/Cntr=.3,.1

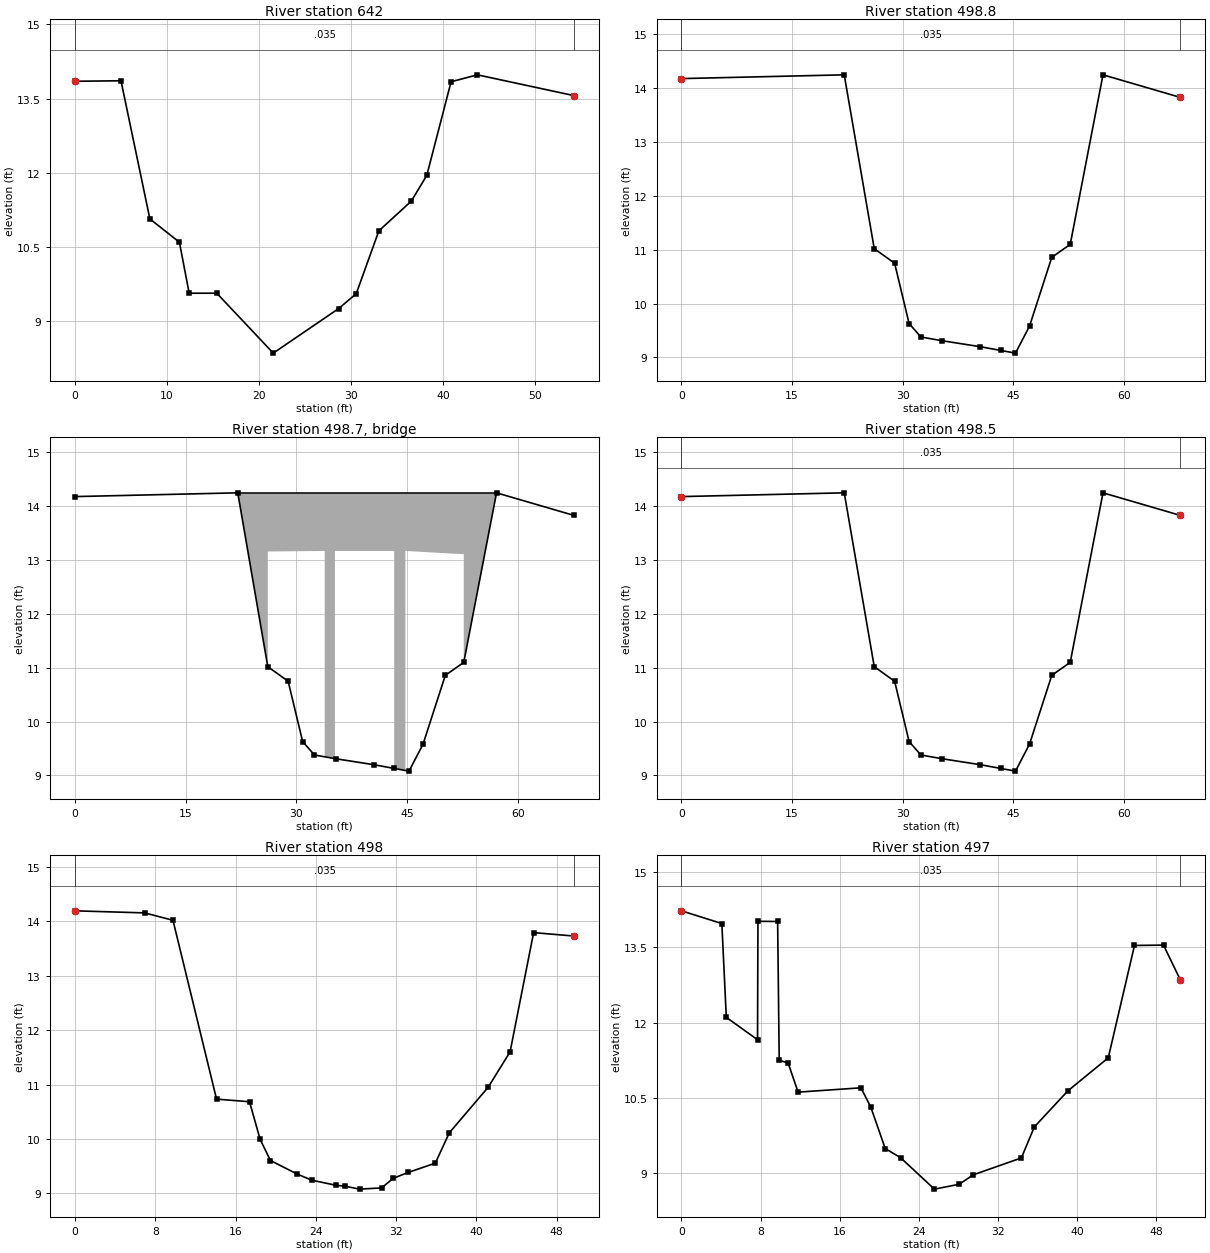
Type RM Length L Ch R = 1 ,642     ,6.71,6.71,6.71
XS GIS Cut Line= 2
      1618205.96      4853996.13      1618218.16      4854048.98
#Sta/Elev= 15
       0 13.8501  4.9999 13.8599    8.14   11.07 11.3501    10.6 12.4099  9.5701
 15.4101  9.5701   21.55  8.3601   28.66  9.2601 30.5699  9.5601   33.03 10.8298
 36.5602   11.43 38.2399   11.95 40.8801 13.8401   43.74   13.98 54.2401 13.5599
#Mann= 3 , 0 , 0
       0    .035       0       0    .035       0 54.2401    .035       0
Bank Sta=0,54.2401
XS Rating Curve= 0
Exp/Cntr=.3,.1

Type RM Length L Ch R = 1 ,498.8   ,5,5,5
#Sta/Elev= 15
       0   14.18   22.06   14.25   26.13   11.02   28.89   10.75   30.85    9.63
   32.45    9.38   35.33    9.31   40.48     9.2   43.26    9.13   45.27    9.08
   47.17    9.58   50.19   10.86   52.69    11.1   57.13   14.25   67.63   13.83
#Mann= 3 , 0 , 0
       0    .035       0       0    .035       0   67.63    .035       0
Bank Sta=0,67.63
XS Rating Curve= 0
Exp/Cntr=.3,.1

Type RM Length L Ch R = 3 ,498.7   ,,,
BEGIN DESCRIPTION:
Ponte Salissimo
END DESCRIPTION:
Bridge Culvert--1,0,-1,-1, 0
Deck Dist Width WeirC Skew NumUp NumDn MinLoCord MaxHiCord MaxSubmerge Is_Ogee
.5,4,1.44,0, 14, 14, , , .95, 0, 0,0,,
   22.06   26.13   26.13   33.84   33.84   35.23   35.23   43.26   43.26   44.78
   44.78   52.69   52.69   57.13
   14.25   14.25   14.25   14.25   14.25   14.25   14.25   14.25   14.25   14.25
   14.25   14.25   14.25   14.25
   14.25   11.02   13.16   13.17    9.35    9.31   13.17   13.17    9.13    9.09
   13.17   13.11    11.1   14.25
   22.06   26.13   26.13   33.84   33.84   35.23   35.23   43.26   43.26   44.78
   44.78   52.69   52.69   57.13
   14.25   14.25   14.25   14.25   14.25   14.25   14.25   14.25   14.25   14.25
   14.25   14.25   14.25   14.25
   14.25   11.02   13.16   13.17    9.35    9.31   13.17   13.17    9.13    9.09
   13.17   13.11    11.1   14.25
BR Coef=-1 , 0 , 0 ,1.25, 0 ,,,.8,-1,2,0,
WSPro=,,,, 1 ,,,, 0 ,,,, 0 ,,,,-1 ,-1 ,-1 , 0 , 0 , 0 , 0 , 0
BC Design=,, 0 ,, 0 ,,,,,,
BC HTab Sub Flow Pts= 40

Type RM Length L Ch R = 1 ,498.5   ,1.55,1.55,1.55
#Sta/Elev= 15
       0   14.18   22.06   14.25   26.13   11.02   28.89   10.75   30.85    9.63
   32.45    9.38   35.33    9.31   40.48     9.2   43.26    9.13   45.27    9.08
   47.17    9.58   50.19   10.86   52.69    11.1   57.13   14.25   67.63   13.83
#Mann= 3 , 0 , 0
       0    .035       0       0    .035       0   67.63    .035       0
Bank Sta=0,67.63
XS Rating Curve= 0
Exp/Cntr=.3,.1

Type RM Length L Ch R = 1 ,498     ,4.81,4.81,4.81
XS GIS Cut Line= 3
      1618197.67      4853993.08      1618209.61       4854040.9
 1618209.6105092 4854040.9020393
#Sta/Elev= 21
       0  14.196   6.938  14.158   9.763  14.022  14.105  10.731   17.39  10.683
  18.443   9.993  19.477   9.601  22.156   9.351  23.582    9.24  25.977   9.147
  26.927   9.128  28.352   9.075  30.551   9.097  31.697   9.273  33.199   9.382
  35.905   9.553  37.293   10.11  41.171   10.95  43.354  11.601  45.698  13.795
  49.722  13.732
#Mann= 3 , 0 , 0
       0    .035       0       0    .035       0  49.722    .035       0
Bank Sta=0,49.722
XS Rating Curve= 0
Exp/Cntr=.3,.1

Type RM Length L Ch R = 1 ,497     ,13.31,13.31,13.31
XS GIS Cut Line= 2
       1618194.6      4853993.84 1618205.4697611 4854042.8089238
#Sta/Elev= 23
       0  14.226   4.082  13.973   4.533  12.106    7.69  11.661   7.732  14.018
   9.722  14.014   9.881  11.253  10.783  11.197  11.789  10.618  18.136  10.704
  19.135  10.323  20.595   9.496  22.153   9.313  25.567   8.688  28.081   8.785
  29.486   8.972  34.359   9.309  35.667   9.926  39.056  10.643  43.141  11.301
  45.791  13.537  48.726  13.544  50.439  12.846
#Mann= 3 , 0 , 0
       0    .035       0       0    .035       0  50.439    .035       0
Bank Sta=0,50.439
XS Rating Curve= 0
Exp/Cntr=.3,.1

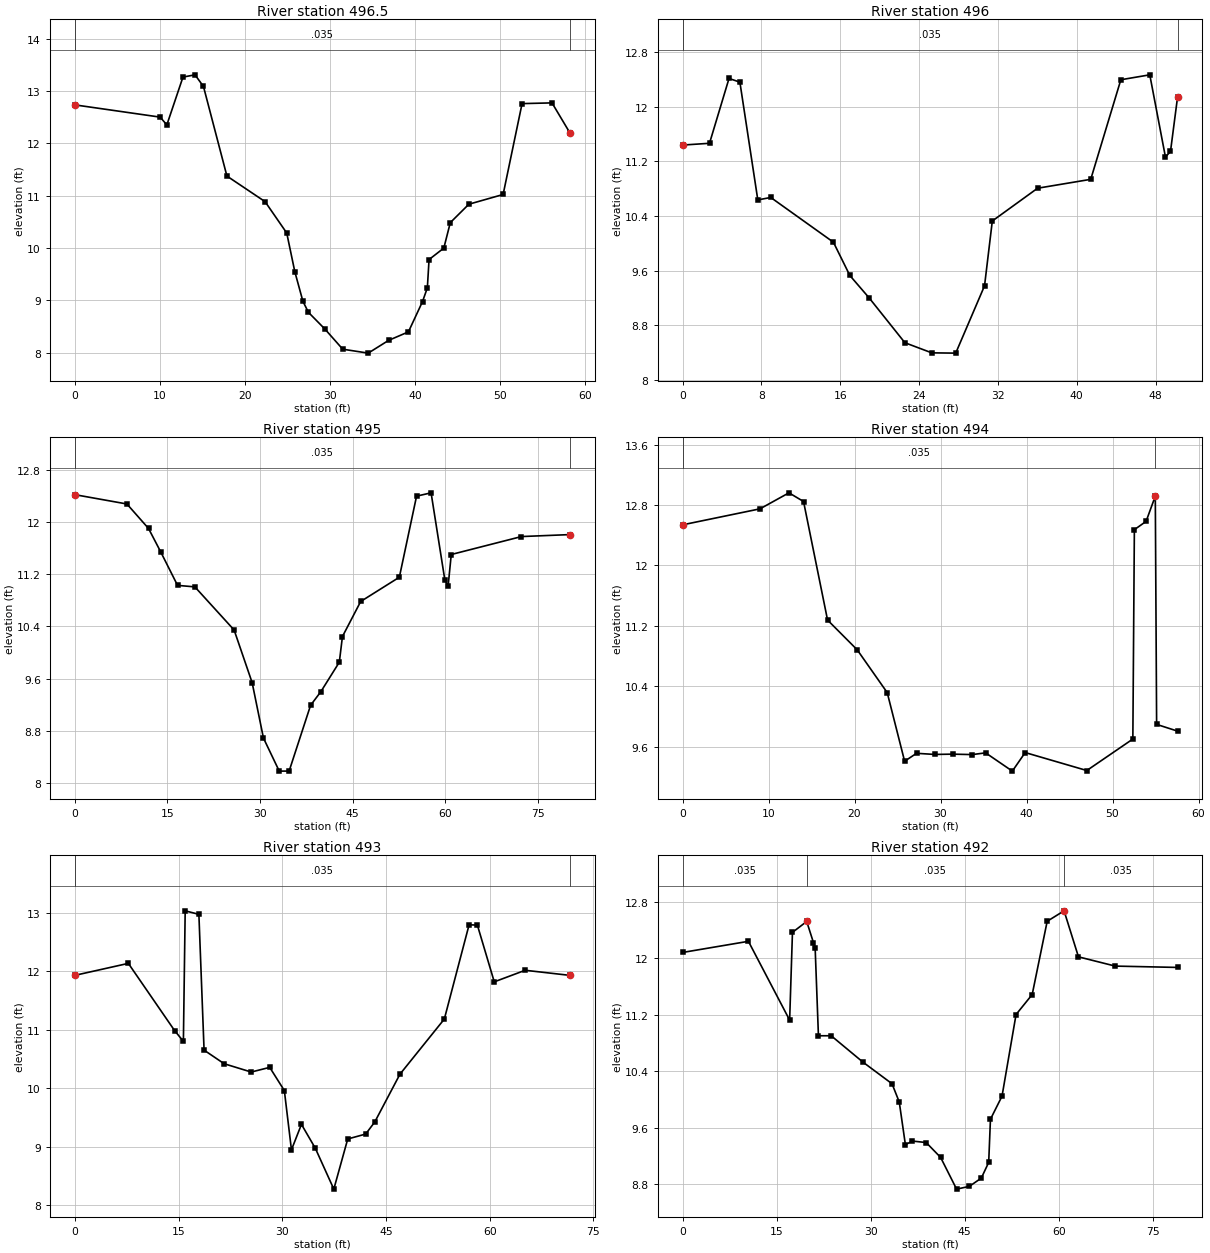
Type RM Length L Ch R = 1 ,496.5   ,26.17,26.17,26.17
XS GIS Cut Line= 2
      1618179.24      4853991.58      1618193.86      4854047.74
#Sta/Elev= 27
       0  12.736  10.034  12.502  10.821  12.353  12.716  13.267  14.132   13.31
  15.125  13.088  17.883  11.376  22.369  10.887  24.914  10.288  25.863    9.55
  26.814   8.984  27.465   8.772  29.395   8.454  31.498   8.068  34.493   7.993
  36.895   8.237  39.218   8.399  40.876   8.978  41.445   9.241  41.645   9.781
  43.381      10  44.141  10.486  46.325  10.838  50.351  11.024  52.578   12.76
  56.098  12.774   58.19  12.204
#Mann= 3 , 0 , 0
       0    .035       0       0    .035       0   58.19    .035       0
Bank Sta=0,58.19
XS Rating Curve= 0
Exp/Cntr=.3,.1

Type RM Length L Ch R = 1 ,496     ,49.12,49.12,49.12
XS GIS Cut Line= 2
      1618155.27      4854009.13 1618169.6496847 4854057.1289476
#Sta/Elev= 21
       0  11.438   2.738  11.464   4.718  12.412   5.821  12.358   7.639  10.636
   8.954  10.672  15.309  10.018  16.979   9.531  18.933   9.204  22.565   8.548
  25.293     8.4  27.722   8.396  30.645    9.38  31.434  10.328  36.028  10.807
  41.422  10.937  44.476  12.393  47.413  12.465  49.002  11.263  49.515  11.345
  50.229  12.137
#Mann= 3 , 0 , 0
       0    .035       0       0    .035       0  50.229    .035       0
Bank Sta=0,50.229
XS Rating Curve= 0
Exp/Cntr=.3,.1

Type RM Length L Ch R = 1 ,495     ,7.74,7.74,7.74
XS GIS Cut Line= 3
      1618103.99       4854015.2      1618129.64      4854090.85
 1618129.6409628 4854090.8528396
#Sta/Elev= 24
       0   12.42   8.438  12.277  11.934  11.902  13.907  11.543  16.632   11.03
  19.436  11.007   25.79  10.346  28.708   9.539  30.535   8.691  33.094   8.184
  34.693   8.185  38.167   9.193  39.832   9.402  42.815   9.853  43.322  10.246
  46.272  10.783  52.534  11.155  55.319  12.397   57.67  12.448   59.91  11.105
  60.432  11.024  60.935  11.503  72.301  11.778  80.123  11.808
#Mann= 3 , 0 , 0
       0    .035       0       0    .035       0  80.123    .035       0
Bank Sta=0,80.123
XS Rating Curve= 0
Exp/Cntr=.3,.1

Type RM Length L Ch R = 1 ,494     ,28.31,28.31,28.31
XS GIS Cut Line= 2
      1618096.41      4854021.13 1618117.8992489 4854074.2481435
#Sta/Elev= 22
       0  12.537    9.01  12.749  12.377  12.961  14.072  12.846  16.864  11.276
  20.309  10.882  23.801  10.315  25.824   9.406  27.212   9.511  29.333   9.496
  31.407     9.5   33.68   9.494  35.244   9.517   38.35   9.275  39.842   9.521
  47.009   9.283  52.362     9.7  52.539  12.473  53.903  12.583  54.973  12.918
  55.126   9.894  57.558   9.805
#Mann= 3 , 0 , 0
       0    .035       0       0    .035       0  54.973    .035       0
Bank Sta=0,54.973
XS Rating Curve= 0
Exp/Cntr=.3,.1

Type RM Length L Ch R = 1 ,493     ,70.04,70.04,70.04
XS GIS Cut Line= 2
      1618069.18      4854026.68 1618094.6285737 4854093.3162653
#Sta/Elev= 25
       0  11.932   7.745  12.137  14.442  10.986  15.707  10.803  15.967  13.036
  17.948  12.976  18.698  10.653  21.604   10.42  25.521  10.278  28.193  10.358
  30.309   9.961  31.337   8.947  32.782   9.383  34.794   8.973  37.464   8.275
  39.477   9.133  42.071   9.217  43.388   9.424  47.028  10.241   53.45  11.185
  57.028  12.797  58.227  12.792   60.67  11.821  65.144  12.019  71.596  11.932
#Mann= 3 , 0 , 0
       0    .035       0       0    .035       0  71.596    .035       0
Bank Sta=0,71.596
XS Rating Curve= 0
Exp/Cntr=.3,.1

Type RM Length L Ch R = 1 ,492     ,42.09,42.09,42.09
XS GIS Cut Line= 2
      1618004.71      4854046.76 1618028.2494007 4854121.6580931
#Sta/Elev= 29
       0  12.085  10.505  12.243  17.078  11.126  17.527   12.37  19.799  12.524
  20.873  12.225  21.143  12.151  21.668  10.905    23.7  10.905  28.757  10.532
  33.401  10.225  34.553   9.966   35.53   9.362  36.648   9.413  38.847   9.392
  41.149   9.181  43.692   8.732  45.723   8.771  47.633   8.888  48.812   9.111
  49.092   9.722  50.935  10.049  53.174  11.206  55.746  11.489  58.137  12.527
  60.828  12.675  63.124  12.023  68.984  11.892  78.918  11.873
#Mann= 3 , 0 , 0
       0    .035       0  19.799    .035       0  60.828    .035       0
Bank Sta=19.799,60.828
XS Rating Curve= 0
Exp/Cntr=.3,.1

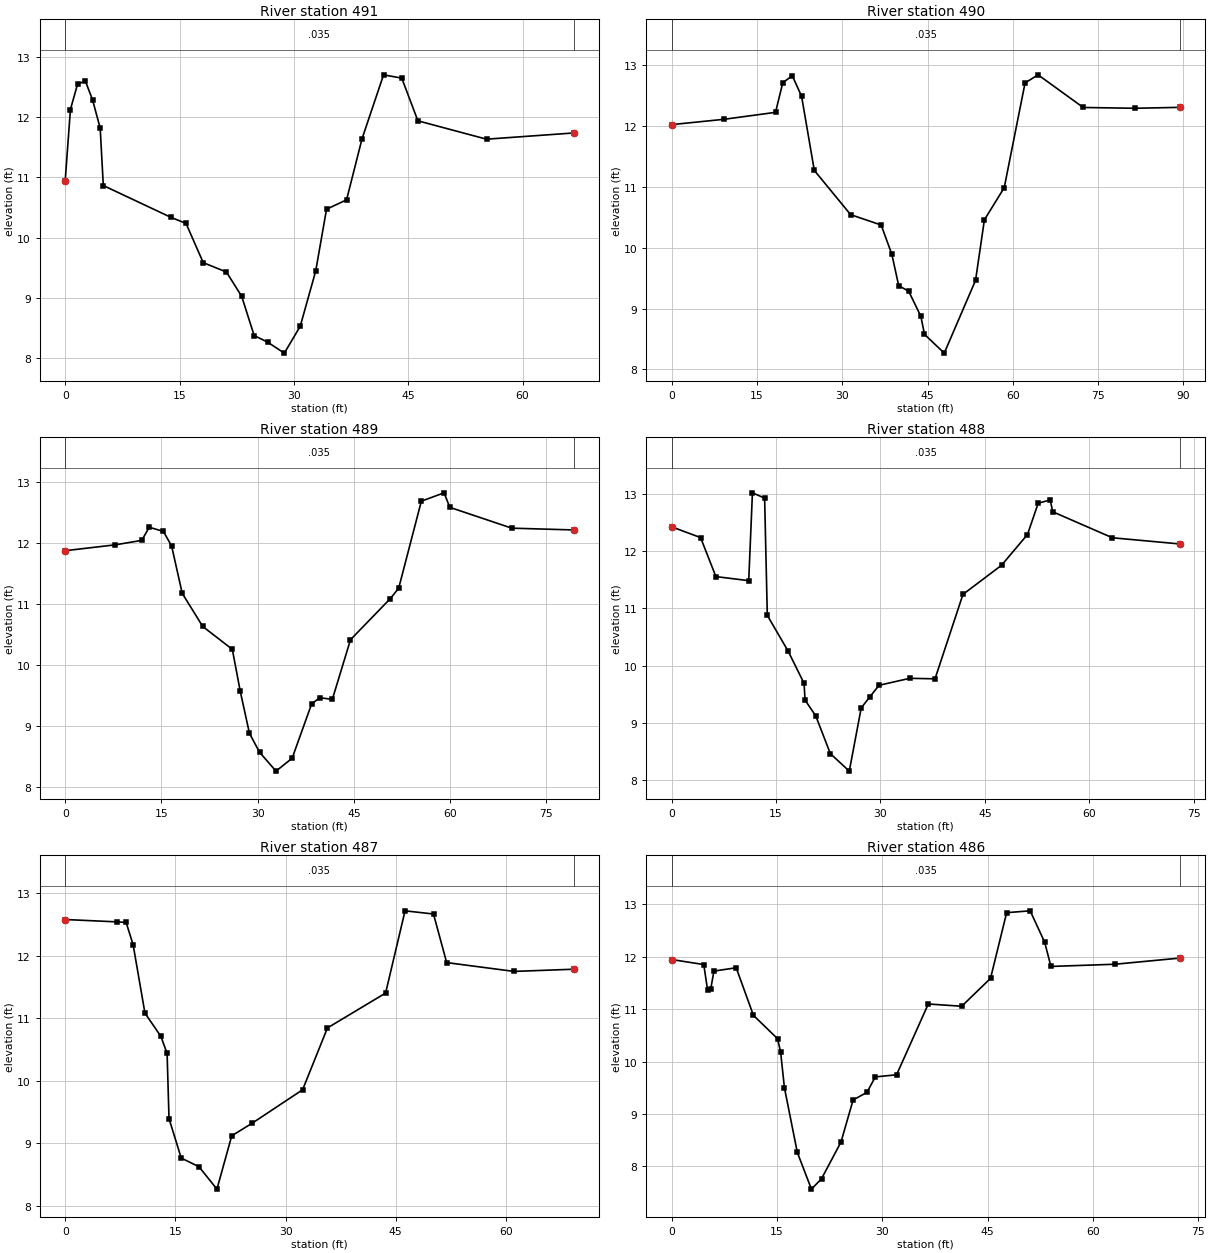
Type RM Length L Ch R = 1 ,491     ,53.17,53.17,53.17
XS GIS Cut Line= 2
      1617970.14      4854072.88 1617988.5597504  4854136.719135
#Sta/Elev= 25
       0  10.948    .683  12.128   1.622   12.55   2.643  12.601   3.592  12.286
   4.588  11.818   4.998  10.865  13.894  10.335  15.849  10.236  18.105   9.584
  21.149   9.428  23.151   9.024  24.786   8.373   26.54   8.264  28.744   8.081
  30.829   8.527  32.858   9.445  34.279  10.472  36.907  10.627  38.936  11.642
  41.762  12.704  44.147  12.649  46.264   11.94  55.265  11.635  66.679  11.738
#Mann= 3 , 0 , 0
       0    .035       0       0    .035       0  66.679    .035       0
Bank Sta=0,66.679
XS Rating Curve= 0
Exp/Cntr=.3,.1

Type RM Length L Ch R = 1 ,490     ,48.79,48.79,48.79
XS GIS Cut Line= 2
      1617914.88      4854064.35  1617937.937411 4854150.3903388
#Sta/Elev= 23
       0  12.027   9.244  12.115  18.263  12.229  19.536  12.716  21.216  12.831
  22.846  12.493  25.081  11.274  31.476  10.546  36.837  10.376  38.714   9.895
  39.923   9.378  41.681   9.287  43.821   8.874  44.458   8.578  47.932   8.269
  53.439   9.466  54.992  10.461   58.48   10.99  62.145  12.713  64.434  12.846
  72.373  12.309  81.455  12.296   89.39  12.311
#Mann= 3 , 0 , 0
       0    .035       0       0    .035       0   89.39    .035       0
Bank Sta=0,89.39
XS Rating Curve= 0
Exp/Cntr=.3,.1

Type RM Length L Ch R = 1 ,489     ,44.86,44.86,44.86
XS GIS Cut Line= 3
      1617865.27      4854089.51      1617900.23       4854160.1
 1617900.2317743 4854160.1035825
#Sta/Elev= 25
       0  11.877   7.797  11.973  11.935  12.046  13.094  12.261  15.293  12.194
  16.584  11.954  18.235  11.179  21.432  10.636  26.045  10.261  27.277   9.576
  28.713   8.886  30.289   8.575  32.854   8.266  35.367   8.477  38.405   9.367
  39.668   9.469  41.633   9.441  44.463  10.419  50.679  11.093  51.975  11.263
  55.503  12.688  59.044  12.825  59.946  12.587  69.605  12.246  79.224  12.217
#Mann= 3 , 0 , 0
       0    .035       0       0    .035       0  79.224    .035       0
Bank Sta=0,79.224
XS Rating Curve= 0
Exp/Cntr=.3,.1

Type RM Length L Ch R = 1 ,488     ,52.16,52.16,52.16
XS GIS Cut Line= 2
      1617823.41      4854127.96  1617875.027798 4854179.0278215
#Sta/Elev= 26
       0  12.423   4.155  12.235   6.354  11.555   11.07  11.484  11.604  13.016
  13.355  12.924  13.741  10.879  16.749  10.251  19.023   9.693  19.164   9.401
  20.702   9.125    22.8   8.467   25.52   8.162  27.232   9.264  28.473   9.458
  29.797   9.659  34.215   9.781  37.838   9.772  41.853  11.245  47.392  11.752
  51.124  12.289  52.661  12.835  54.393  12.892  54.742  12.686  63.328  12.232
  73.037  12.124
#Mann= 3 , 0 , 0
       0    .035       0       0    .035       0  73.037    .035       0
Bank Sta=0,73.037
XS Rating Curve= 0
Exp/Cntr=.3,.1

Type RM Length L Ch R = 1 ,487     ,47.06,47.06,47.06
XS GIS Cut Line= 2
      1617790.54      4854168.36 1617841.0156189 4854215.5359053
#Sta/Elev= 21
       0  12.579   7.109  12.541   8.295  12.532   9.247  12.175  10.856  11.082
  13.026   10.71  13.872  10.437  14.132   9.395  15.794   8.764  18.213   8.625
  20.657   8.267  22.673    9.12  25.395   9.317  32.317   9.856  35.702  10.845
   43.62  11.403  46.266  12.718   50.14  12.667  51.932   11.89  61.101  11.749
  69.204  11.784
#Mann= 3 , 0 , 0
       0    .035       0       0    .035       0  69.204    .035       0
Bank Sta=0,69.204
XS Rating Curve= 0
Exp/Cntr=.3,.1

Type RM Length L Ch R = 1 ,486     ,80.08,80.08,80.08
XS GIS Cut Line= 3
      1617757.09      4854206.35      1617814.48      4854249.82
 1617814.4807176 4854249.8205436
#Sta/Elev= 27
       0  11.949    4.57  11.853   5.119  11.362   5.555   11.38   6.017  11.728
   9.188  11.792  11.644  10.883  15.076  10.438  15.514  10.186  16.058   9.502
  17.895   8.266  19.903   7.565  21.341   7.763   24.11   8.462  25.842   9.268
    27.8   9.411  29.012   9.708  32.033   9.748  36.548    11.1   41.31  11.057
  45.412  11.589  47.712  12.844  51.061  12.879  53.121  12.281  54.019  11.817
  63.126  11.859  72.401  11.977
#Mann= 3 , 0 , 0
       0    .035       0       0    .035       0  72.401    .035       0
Bank Sta=0,72.401
XS Rating Curve= 0
Exp/Cntr=.3,.1

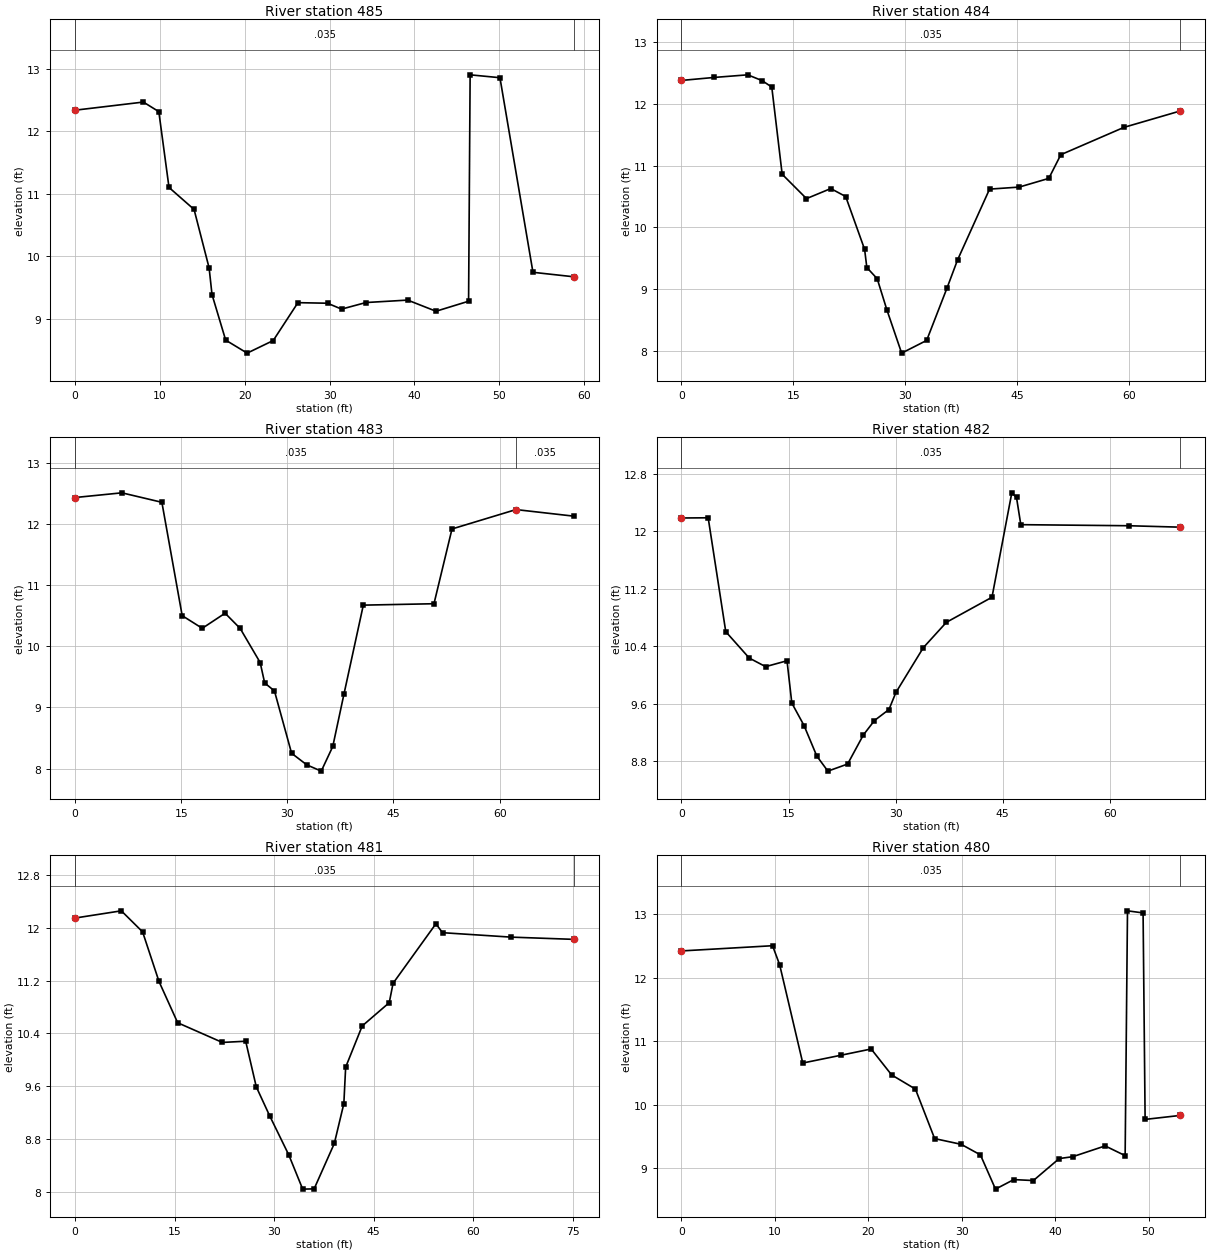
Type RM Length L Ch R = 1 ,485     ,53.94,53.94,53.94
XS GIS Cut Line= 3
      1617723.57      4854284.76       1617777.9      4854306.83
 1617777.9037993 4854306.8315434
#Sta/Elev= 21
       0  12.335   8.059  12.465   9.878  12.312  11.079  11.101  14.032   10.75
  15.805   9.816  16.146   9.391  17.755   8.663  20.288   8.455  23.359   8.656
  26.272   9.261  29.756   9.252   31.41   9.158  34.289   9.263  39.204   9.302
  42.542   9.124  46.382   9.284  46.564    12.9  50.078  12.854  53.968   9.746
  58.804   9.674
#Mann= 3 , 0 , 0
       0    .035       0       0    .035       0  58.804    .035       0
Bank Sta=0,58.804
XS Rating Curve= 0
Exp/Cntr=.3,.1

Type RM Length L Ch R = 1 ,484     ,53.95,53.95,53.95
XS GIS Cut Line= 3
      1617698.14      4854321.94      1617749.95      4854364.04
   1617749.95225 4854364.0418283
#Sta/Elev= 23
       0   12.38   4.418  12.429   8.878  12.471  10.821  12.376  12.098  12.272
  13.488  10.859  16.746  10.464  19.998  10.627  21.997  10.498   24.53   9.641
  24.827   9.347  26.217   9.165  27.514    8.66   29.49   7.959  32.839   8.165
   35.58   9.019  36.975   9.469  41.265  10.618  45.235  10.651  49.198  10.792
  50.808  11.176  59.256  11.619  66.833  11.886
#Mann= 3 , 0 , 0
       0    .035       0       0    .035       0  66.833    .035       0
Bank Sta=0,66.833
XS Rating Curve= 0
Exp/Cntr=.3,.1

Type RM Length L Ch R = 1 ,483     ,48.54,48.54,48.54
XS GIS Cut Line= 3
      1617663.24      4854348.64      1617701.76      4854407.57
 1617701.7616948 4854407.5725928
#Sta/Elev= 20
       0  12.434   6.624  12.511  12.276  12.356  15.144  10.502  17.982  10.295
  21.208  10.542  23.337  10.293  26.163   9.735  26.799   9.401   28.18   9.271
  30.603   8.251  32.756   8.061  34.793   7.959  36.421   8.362  37.998   9.217
  40.735  10.674   50.72  10.697  53.266   11.92  62.307  12.237  70.503  12.129
#Mann= 3 , 0 , 0
       0    .035       0       0    .035       0  62.307    .035       0
Bank Sta=0,62.307
XS Rating Curve= 0
Exp/Cntr=.3,.1

Type RM Length L Ch R = 1 ,482     ,61.86,61.86,61.86
XS GIS Cut Line= 2
       1617630.2      4854375.78 1617652.4184083  4854441.905263
#Sta/Elev= 23
       0  12.187   3.742   12.19   6.204  10.602   9.492  10.234  11.785  10.114
  14.781  10.196  15.457   9.606  17.166   9.293  18.956   8.867  20.505   8.657
  23.272   8.756  25.473   9.161  27.032   9.363  29.058   9.516  30.034   9.754
  33.875  10.379  37.099  10.732  43.489  11.082  46.264  12.538  46.923  12.473
  47.525  12.094  62.677  12.079  69.885  12.059
#Mann= 3 , 0 , 0
       0    .035       0       0    .035       0  69.885    .035       0
Bank Sta=0,69.885
XS Rating Curve= 0
Exp/Cntr=.3,.1

Type RM Length L Ch R = 1 ,481     ,80.61,80.61,80.61
XS GIS Cut Line= 2
      1617570.95      4854380.82 1617585.0797931  4854454.518921
#Sta/Elev= 22
       0  12.143   6.981  12.252  10.185  11.934  12.655  11.185  15.468  10.562
  22.195  10.265  25.712  10.283  27.311   9.594  29.307   9.161  32.212   8.565
  34.299    8.05  36.023   8.054  39.066    8.74  40.499   9.341  40.772   9.891
  43.267  10.514  47.336  10.865  47.915  11.158  54.364  12.056  55.367  11.922
  65.672  11.855  75.169  11.821
#Mann= 3 , 0 , 0
       0    .035       0       0    .035       0  75.169    .035       0
Bank Sta=0,75.169
XS Rating Curve= 0
Exp/Cntr=.3,.1

Type RM Length L Ch R = 1 ,480     ,44.37,44.37,44.37
XS GIS Cut Line= 3
       1617508.5       4854383.3      1617495.78      4854434.97
 1617495.7799763 4854434.9700963
#Sta/Elev= 22
       0  12.423   9.754  12.505  10.513  12.205  12.985  10.659  17.048  10.781
   20.31   10.88  22.499  10.472  25.047  10.249  27.103    9.47  29.946    9.38
  32.005   9.214  33.619   8.675  35.575   8.825  37.672    8.81   40.44   9.156
  41.881   9.185  45.358   9.355  47.497   9.202  47.749  13.054  49.418  13.021
  49.636   9.772   53.42   9.835
#Mann= 3 , 0 , 0
       0    .035       0       0    .035       0   53.42    .035       0
Bank Sta=0,53.42
XS Rating Curve= 0
Exp/Cntr=.3,.1

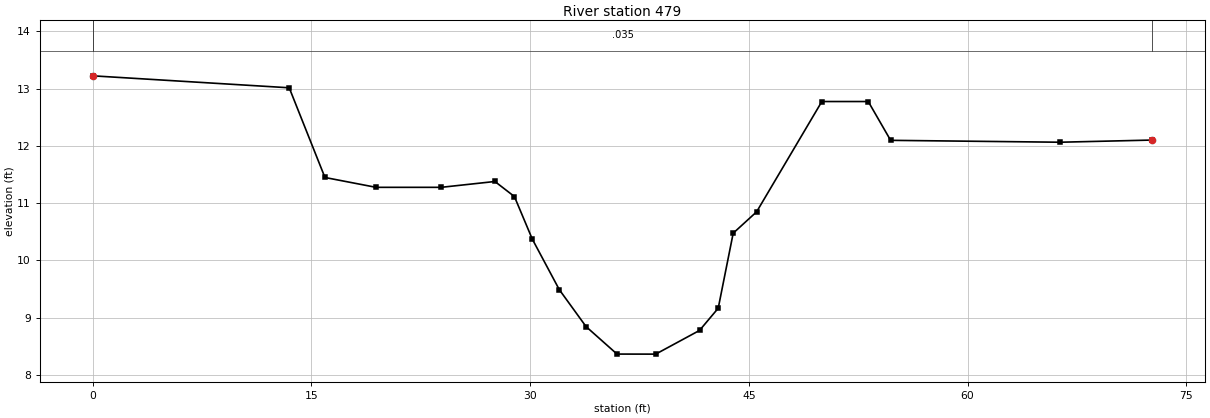
Type RM Length L Ch R = 1 ,479     ,52.32,52.32,52.32
XS GIS Cut Line= 2
      1617468.61      4854368.03 1617449.8412695 4854438.0852614
#Sta/Elev= 21
       0  13.225  13.475  13.016  15.925  11.449   19.43  11.277  23.898  11.277
  27.584  11.379  28.921  11.116  30.147  10.373  32.001   9.489  33.836   8.844
  35.958   8.364  38.613   8.363  41.619   8.777  42.901   9.165  43.928  10.476
  45.534  10.849  50.009  12.776  53.192  12.776  54.727  12.098  66.349  12.065
  72.685  12.103
#Mann= 3 , 0 , 0
       0    .035       0       0    .035       0  72.685    .035       0
Bank Sta=0,72.685
XS Rating Curve= 0
Exp/Cntr=.3,.1