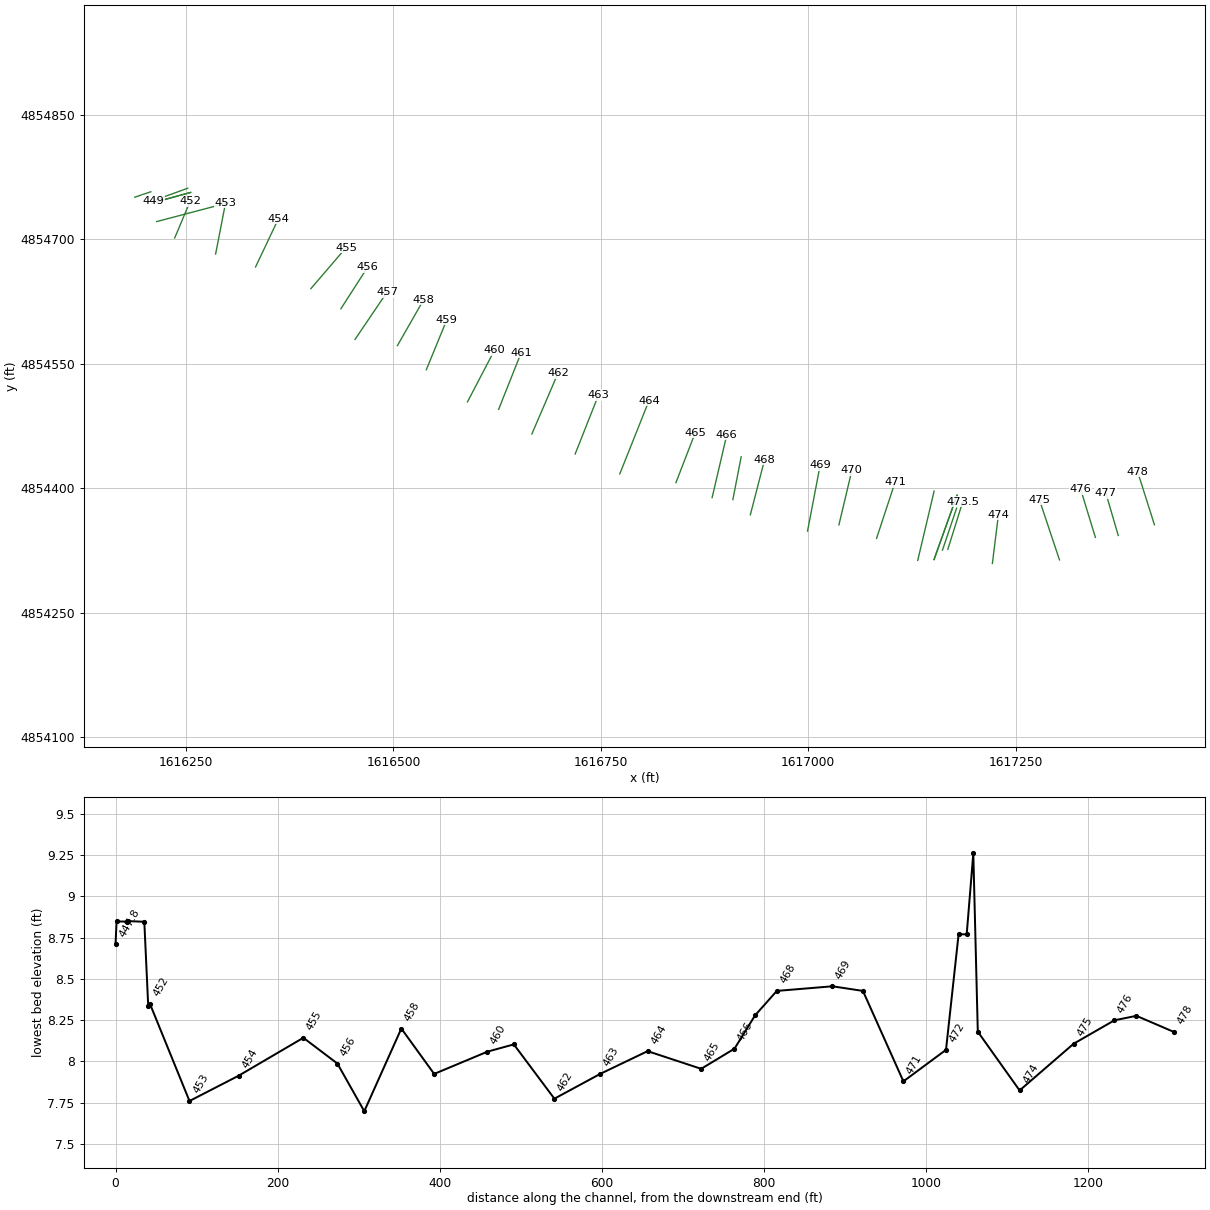
HEC-RAS study ozz_def.prj: ozzeri

--- ozz_def.g02 (geometry) --- (continued)

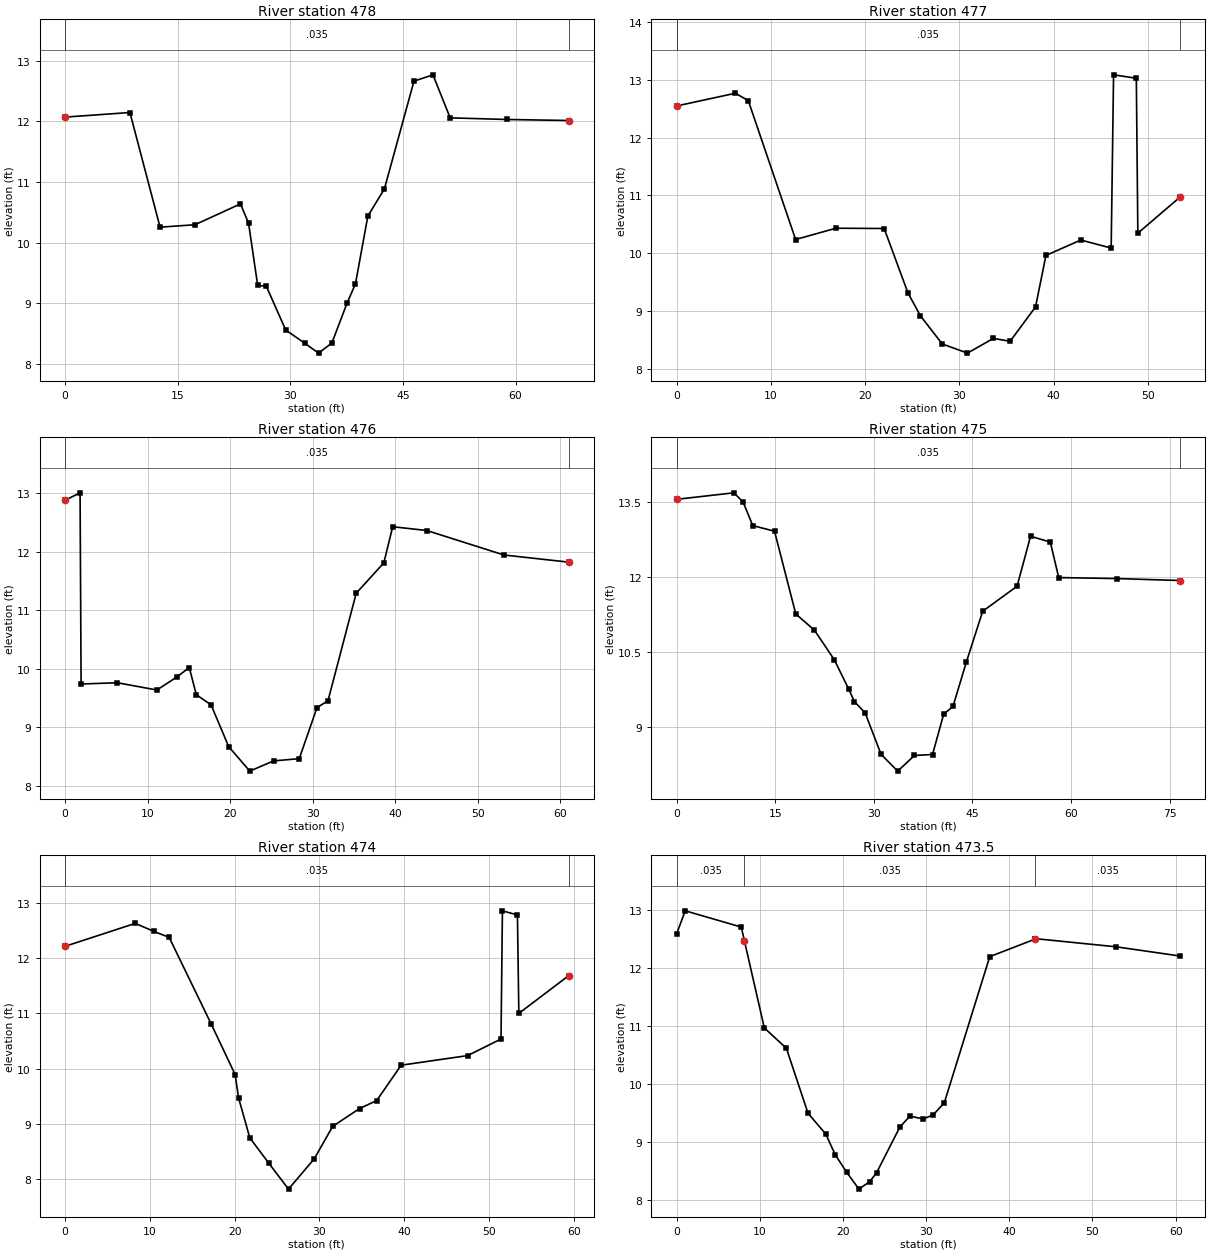
Type RM Length L Ch R = 1 ,478     ,45.94,45.94,45.94
XS GIS Cut Line= 3
      1617417.25      4854355.94      1617397.08      4854419.71
 1617397.0796986 4854419.7109529
#Sta/Elev= 21
       0  12.069   8.649  12.145   12.66  10.255  17.305  10.295  23.366  10.639
  24.446  10.319  25.656   9.298  26.817   9.279   29.39    8.56  31.894   8.345
  33.758   8.179  35.536   8.345  37.544   8.999   38.68   9.323  40.327  10.438
  42.531  10.886  46.467  12.662  48.996  12.766  51.285  12.057  58.794   12.03
  67.061  12.013
#Mann= 3 , 0 , 0
       0    .035       0       0    .035       0  67.061    .035       0
Bank Sta=0,67.061
XS Rating Curve= 0
Exp/Cntr=.3,.1

Type RM Length L Ch R = 1 ,477     ,27.16,27.16,27.16
XS GIS Cut Line= 3
      1617373.64      4854343.08      1617358.66      4854394.26
 1617358.6588759 4854394.2638405
#Sta/Elev= 20
       0  12.546   6.245  12.766   7.611  12.638  12.632  10.239  16.911  10.434
   22.03  10.429  24.553   9.316  25.879    8.92  28.189   8.435  30.867   8.276
  33.615    8.53  35.397   8.481  38.092   9.075  39.194   9.964  42.901   10.23
  46.116  10.091   46.37  13.084  48.785  13.025  48.946  10.348  53.444  10.975
#Mann= 3 , 0 , 0
       0    .035       0       0    .035       0  53.444    .035       0
Bank Sta=0,53.444
XS Rating Curve= 0
Exp/Cntr=.3,.1

Type RM Length L Ch R = 1 ,476     ,50.35,50.35,50.35
XS GIS Cut Line= 3
      1617346.09      4854340.69      1617328.35      4854398.72
 1617328.3493866 4854398.7220064
#Sta/Elev= 21
       0  12.883   1.828  13.011   1.952    9.74   6.356   9.761  11.132   9.637
  13.521   9.857  15.055  10.022  15.907   9.557  17.692   9.383   19.83   8.668
  22.383   8.249  25.267   8.424  28.374   8.462  30.517   9.334  31.859   9.455
  35.273  11.293  38.617  11.813  39.694  12.431  43.826  12.366  53.173  11.947
  61.002  11.825
#Mann= 3 , 0 , 0
       0    .035       0       0    .035       0  61.002    .035       0
Bank Sta=0,61.002
XS Rating Curve= 0
Exp/Cntr=.3,.1

Type RM Length L Ch R = 1 ,475     ,66.68,66.68,66.68
XS GIS Cut Line= 3
       1617302.8      4854313.67      1617278.56       4854386.2
 1617278.5587642 4854386.2036976
#Sta/Elev= 25
       0  13.547   8.704  13.677   10.11  13.496   11.59  13.021  14.896  12.909
  18.126  11.253  20.973  10.927  23.975  10.339  26.195   9.744  27.044   9.499
  28.668   9.275  31.097   8.444  33.629   8.107  36.178   8.421  38.922   8.439
  40.621   9.247  42.034   9.401  44.066  10.289  46.553  11.307  51.782  11.808
  53.833  12.808  56.834  12.691  58.116  11.981  66.935  11.961  76.594  11.922
#Mann= 3 , 0 , 0
       0    .035       0       0    .035       0  76.594    .035       0
Bank Sta=0,76.594
XS Rating Curve= 0
Exp/Cntr=.3,.1

Type RM Length L Ch R = 1 ,474     ,51.6,51.6,51.6
XS GIS Cut Line= 2
      1617221.91      4854309.33 1617229.1895079 4854368.0160326
#Sta/Elev= 21
       0  12.212   8.284  12.627  10.488  12.482  12.284  12.374  17.261  10.802
   20.06   9.895   20.47   9.473   21.79   8.752  24.023   8.295  26.356   7.824
  29.386   8.371  31.563   8.958  34.736   9.281  36.749   9.424  39.641  10.064
  47.465  10.237  51.411  10.537  51.578  12.854  53.349  12.779  53.513      11
  59.386  11.682
#Mann= 3 , 0 , 0
       0    .035       0       0    .035       0  59.386    .035       0
Bank Sta=0,59.386
XS Rating Curve= 0
Exp/Cntr=.3,.1

Type RM Length L Ch R = 1 ,473.5   ,5.54,5.54,5.54
XS GIS Cut Line= 2
      1617168.21      4854326.38      1617186.27      4854384.01
#Sta/Elev= 23
       0   12.58    1.04 12.9799    7.78 12.7001  8.1601 12.4599   10.55   10.96
    13.2 10.6101 15.7999  9.4899 17.9299    9.13 19.0899    8.77 20.4499  8.4701
 21.9301  8.1799   23.22  8.3101 24.0399    8.46 26.8401  9.2501 28.0599    9.44
 29.6299    9.39   30.85  9.4601 32.1899  9.6701 37.6501 12.1899 43.0701 12.4901
 43.1499 12.4998   52.82 12.3599   60.55 12.1999
#Mann= 3 , 0 , 0
       0    .035       0  8.1601    .035       0 43.0701    .035       0
Bank Sta=8.1601,43.0701
XS Rating Curve= 0
Exp/Cntr=.3,.1

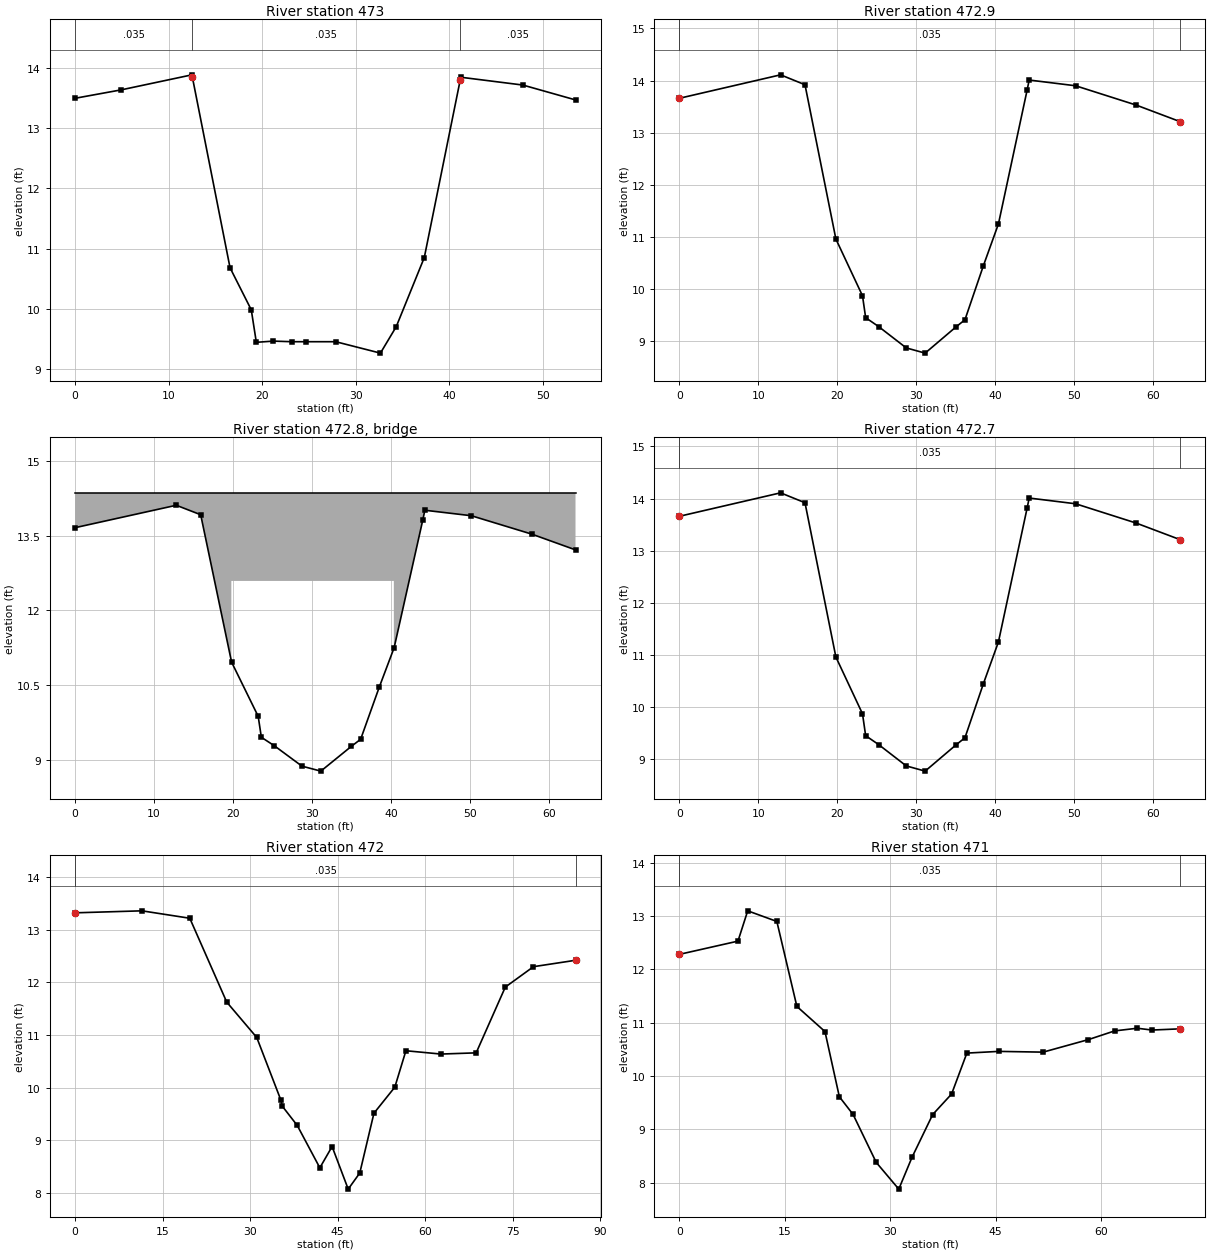
Type RM Length L Ch R = 1 ,473     ,8.15,8.15,8.15
XS GIS Cut Line= 2
      1617161.75       4854325.4      1617178.77      4854375.95
#Sta/Elev= 18
       0 13.4999  4.9399 13.6401 12.4998   13.89   12.53 13.8599 16.5701 10.6799
   18.84  9.9801 19.3801    9.44 21.2001  9.4601   23.18    9.45   24.69    9.45
   27.87    9.45 32.6499  9.2601   34.34     9.7 37.3401   10.85 41.1901 13.8099
   41.23 13.8501 47.8801   13.72 53.5701   13.47
#Mann= 3 , 0 , 0
       0    .035       0   12.53    .035       0 41.1901    .035       0
Bank Sta=12.53,41.1901
XS Rating Curve= 0
Exp/Cntr=.3,.1

Type RM Length L Ch R = 1 ,472.9   ,10,10,10
XS GIS Cut Line= 2
       1617151.6      4854314.11      1617179.34      4854391.64
#Sta/Elev= 18
       0 13.6599 12.8101 14.1101 15.8999 13.9199 19.8099   10.96   23.18    9.87
 23.5799    9.45 25.2201  9.2799 28.7201    8.87   31.11    8.77 34.9901  9.2699
 36.1499  9.4101 38.4901 10.4501   40.39 11.2499 44.0101 13.8099 44.2801 14.0101
   50.16 13.9001   57.82 13.5301   63.42   13.21
#Mann= 3 , 0 , 0
       0    .035       0       0    .035       0   63.42    .035       0
Bank Sta=0,63.42
XS Rating Curve= 0
Exp/Cntr=.3,.1

Type RM Length L Ch R = 3 ,472.8   ,,,
BEGIN DESCRIPTION:
ponte di meati
END DESCRIPTION:
Bridge Culvert--1,0,-1,-1, 0
Deck Dist Width WeirC Skew NumUp NumDn MinLoCord MaxHiCord MaxSubmerge Is_Ogee
.5,9,1.44,0, 11, 11, , , .95, 0, 0,0,,
       0 12.8101 15.8901   19.78   19.78      25   40.35   40.35 50.0899 57.7599
 63.3499
   14.36   14.36   14.36   14.36   14.36   14.36   14.36   14.36   14.36   14.36
   14.36
 12.5901 12.5901 12.5901   10.96 12.5901 12.5901 12.5901 11.2499 12.5901 12.5901
 12.5901
       0 12.8101 15.8901   19.78   19.78      25   40.35   40.35 50.0899 57.7599
 63.3499
   14.36   14.36   14.36   14.36   14.36   14.36   14.36   14.36   14.36   14.36
   14.36
 12.5901 12.5901 12.5901   10.96 12.5901 12.5901 12.5901 11.2499 12.5901 12.5901
 12.5901
BR Coef=-1 , 0 , 0 ,1.25, 0 ,,,.8,-1,2,0,
WSPro=,,,, 1 ,,,, 0 ,,,, 0 ,,,,-1 ,-1 ,-1 , 0 , 0 , 0 , 0 , 0
BC Design=,, 0 ,, 0 ,,,,,,
BC HTab Sub Flow Pts= 40

Type RM Length L Ch R = 1 ,472.7   ,15.54,15.54,15.54
XS GIS Cut Line= 2
       1617151.6      4854314.11      1617179.34      4854391.64
#Sta/Elev= 18
       0 13.6599 12.8101 14.1101 15.8999 13.9199 19.8099   10.96   23.18    9.87
 23.5799    9.45 25.2201  9.2799 28.7201    8.87   31.11    8.77 34.9901  9.2699
 36.1499  9.4101 38.4901 10.4501   40.39 11.2499 44.0101 13.8099 44.2801 14.0101
   50.16 13.9001   57.82 13.5301   63.42   13.21
#Mann= 3 , 0 , 0
       0    .035       0       0    .035       0   63.42    .035       0
Bank Sta=0,63.42
XS Rating Curve= 0
Exp/Cntr=.3,.1

Type RM Length L Ch R = 1 ,472     ,52.56,52.56,52.56
XS GIS Cut Line= 2
      1617131.94      4854313.08      1617151.69      4854396.57
#Sta/Elev= 20
       0  13.319  11.459  13.357  19.657  13.216   25.99  11.623  31.135  10.951
  35.277   9.759  35.511   9.646  38.073    9.28  41.947   8.475  44.047   8.879
  46.807    8.07   48.79   8.376  51.218   9.512  54.796  10.007  56.697  10.699
  62.703  10.636   68.74  10.659  73.733  11.908  78.561  12.296   85.86  12.419
#Mann= 3 , 0 , 0
       0    .035       0       0    .035       0   85.86    .035       0
Bank Sta=0,85.86
XS Rating Curve= 0
Exp/Cntr=.3,.1

Type RM Length L Ch R = 1 ,471     ,49.97,49.97,49.97
XS GIS Cut Line= 2
      1617082.32      4854339.62 1617104.5590596 4854407.1371449
#Sta/Elev= 21
       0   12.28   8.336  12.528   9.722  13.096   13.87  12.897  16.719  11.304
  20.718  10.833  22.764   9.611  24.723   9.278  28.013    8.38  31.224   7.879
  33.104   8.475  36.048   9.277  38.739   9.662  40.912  10.429  45.461  10.461
  51.764  10.447  58.207  10.682  61.939  10.845  65.158  10.895  67.265  10.861
  71.297  10.884
#Mann= 3 , 0 , 0
       0    .035       0       0    .035       0  71.297    .035       0
Bank Sta=0,71.297
XS Rating Curve= 0
Exp/Cntr=.3,.1

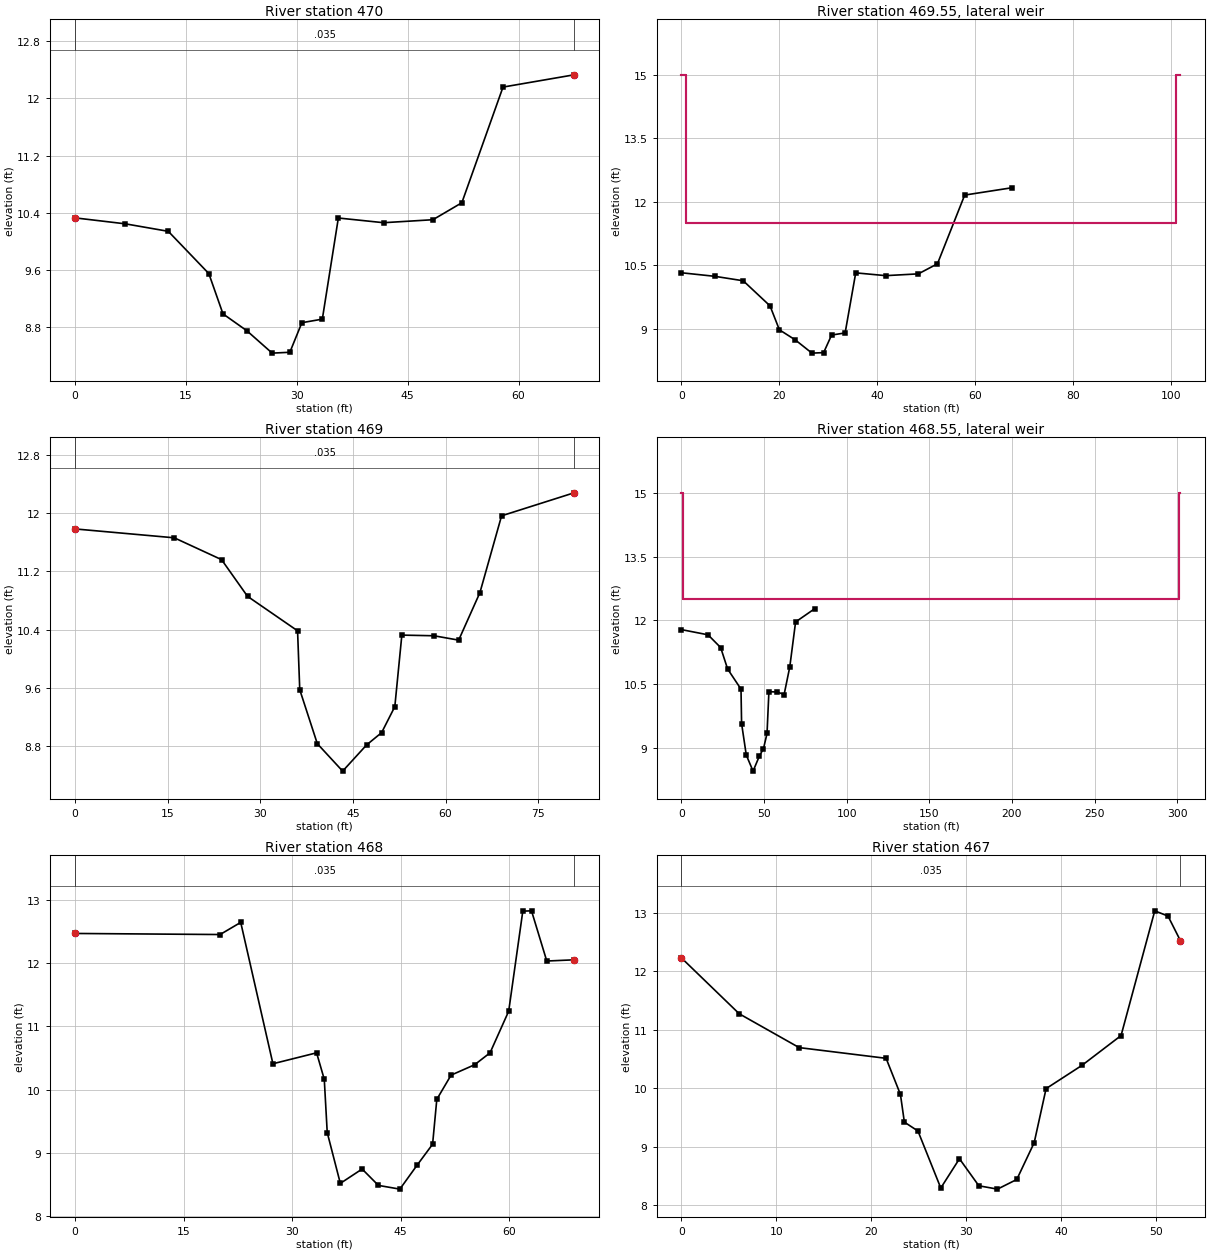
Type RM Length L Ch R = 1 ,470     ,37.63,37.63,37.63
XS GIS Cut Line= 2
      1617036.92      4854355.84 1617052.5190528  4854421.486014
#Sta/Elev= 16
       0  10.325   6.823  10.241  12.622  10.136  18.103   9.543  20.017   8.978
  23.259    8.74  26.671   8.427  29.063   8.439  30.687   8.854  33.455   8.904
  35.621  10.323  41.743  10.257  48.418  10.299  52.326  10.537  57.893   12.16
  67.496  12.332
#Mann= 3 , 0 , 0
       0    .035       0       0    .035       0  67.496    .035       0
Bank Sta=0,67.496
XS Rating Curve= 0
Exp/Cntr=.3,.1

Type RM Length L Ch R = 6 ,469.55  ,,,
Lateral Weir Pos= 3
Lateral Weir End=                ,                ,        ,c01
Lateral Weir Distance=1
Lateral Weir WD=3.0001
Lateral Weir Coef=1.66
Lateral Weir Is Ogee= 0
Lateral Weir WSCriteria=-1
Lateral Weir SE= 6
       0 15.0001       1 15.0001       1 11.5001     101 11.5001     101 15.0001
102.0001 15.0001

Type RM Length L Ch R = 1 ,469     ,68.65,68.65,68.65
XS GIS Cut Line= 2
       1616999.1      4854348.32 1617014.2692476 4854427.6360659
#Sta/Elev= 17
       0  11.783  16.072  11.661   23.73  11.361  27.933  10.857  36.038  10.383
  36.392   9.574  39.235   8.832  43.338   8.455  47.215   8.815  49.648   8.984
  51.784   9.341  52.922  10.324  58.119  10.315  62.123  10.255  65.564  10.908
  69.069  11.963  80.796  12.279
#Mann= 3 , 0 , 0
       0    .035       0       0    .035       0  80.796    .035       0
Bank Sta=0,80.796
XS Rating Curve= 0
Exp/Cntr=.3,.1

Type RM Length L Ch R = 6 ,468.55  ,,,
Lateral Weir Pos= 0
Lateral Weir End=                ,                ,        ,c02
Lateral Weir Distance=1
Lateral Weir WD=3.0001
Lateral Weir Coef=1.66
Lateral Weir Is Ogee= 0
Lateral Weir WSCriteria=-1
Lateral Weir SE= 6
       0 15.0001       1 15.0001       1 12.4998301.0001 12.4998301.0001 15.0001
302.0001 15.0001

Type RM Length L Ch R = 1 ,468     ,26.77,26.77,26.77
XS GIS Cut Line= 3
      1616930.16      4854367.99      1616947.38      4854434.63
 1616947.3807501  4854434.632903
#Sta/Elev= 22
       0  12.471  20.049  12.454  22.897  12.646  27.346   10.41   33.38  10.583
  34.441  10.164  34.849   9.322  36.659   8.518  39.669   8.745   41.92   8.486
  44.884   8.427   47.26   8.805  49.406   9.137  49.989   9.847  51.958   10.23
  55.209  10.394  57.344  10.583  59.921  11.242   61.87  12.824  63.073  12.829
  65.182  12.035  68.943  12.054
#Mann= 3 , 0 , 0
       0    .035       0       0    .035       0  68.943    .035       0
Bank Sta=0,68.943
XS Rating Curve= 0
Exp/Cntr=.3,.1

Type RM Length L Ch R = 1 ,467     ,25.46,25.46,25.46
XS GIS Cut Line= 3
      1616909.08      4854386.31      1616919.11      4854437.84
  1616919.110172 4854437.8408837
#Sta/Elev= 19
       0  12.229   6.088  11.275  12.404  10.697  21.564  10.514  23.075   9.896
  23.488   9.424  24.919   9.272  27.325   8.298  29.292   8.798  31.337   8.336
    33.3   8.279  35.333   8.444  37.166   9.072  38.421   9.996  42.205  10.394
  46.322  10.903  49.873  13.034   51.27  12.944  52.581  12.522
#Mann= 3 , 0 , 0
       0    .035       0       0    .035       0  52.581    .035       0
Bank Sta=0,52.581
XS Rating Curve= 0
Exp/Cntr=.3,.1

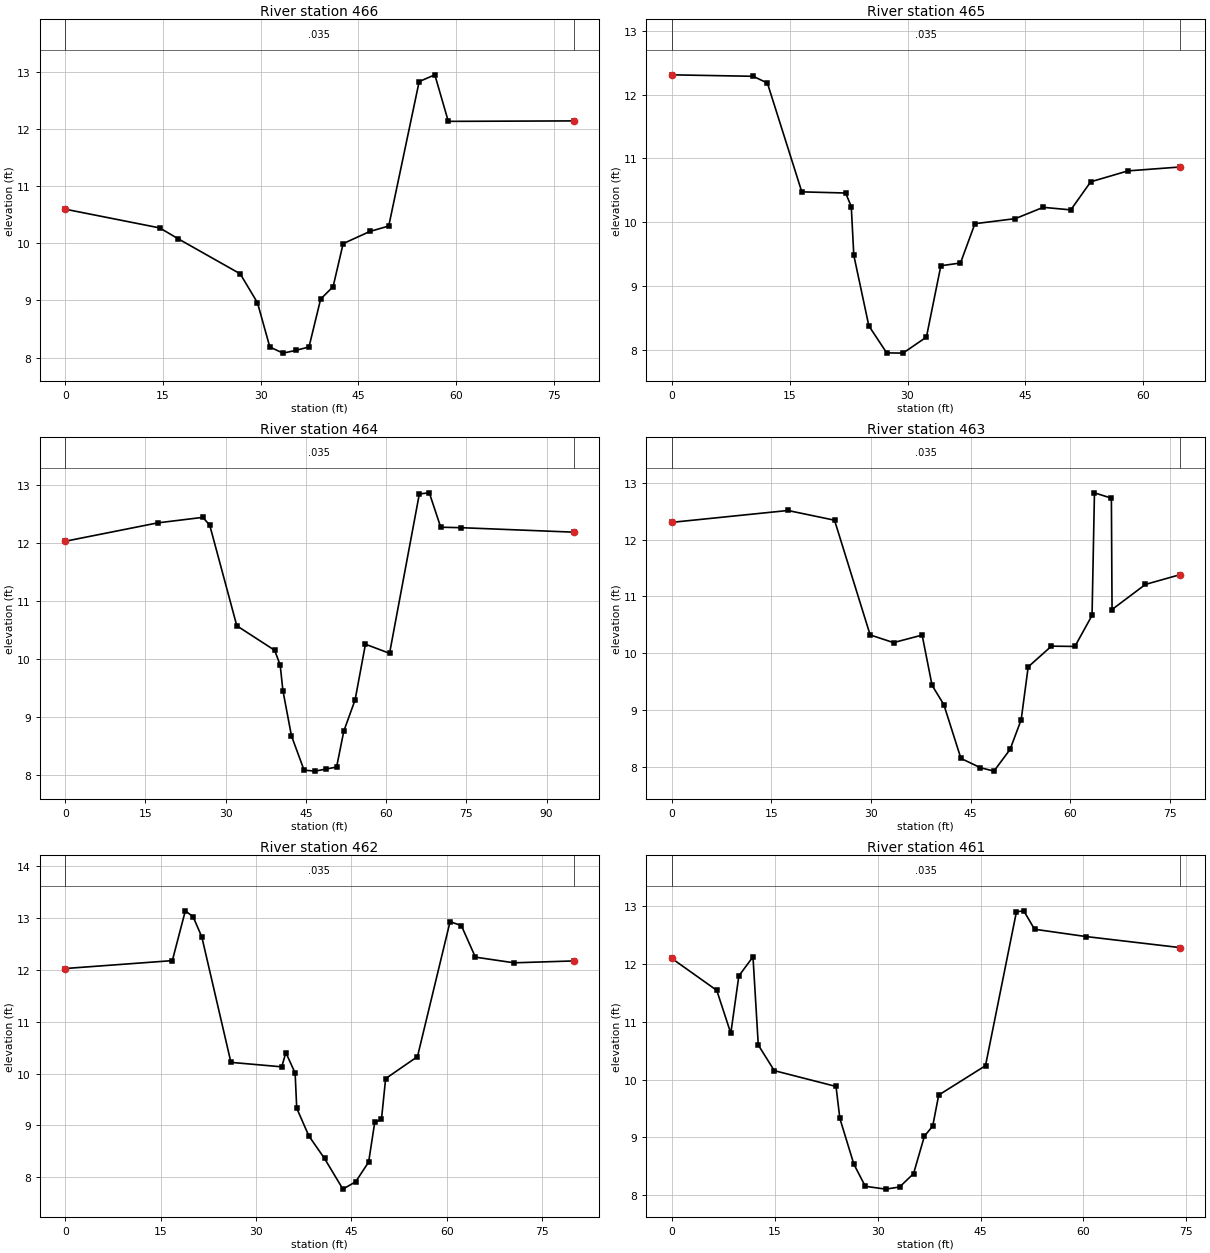
Type RM Length L Ch R = 1 ,466     ,41.11,41.11,41.11
XS GIS Cut Line= 2
      1616884.09      4854388.75 1616901.7497276 4854464.3588336
#Sta/Elev= 18
       0  10.598    14.5   10.27  17.331   10.08  26.849   9.466  29.501    8.96
  31.395   8.184  33.426   8.077  35.417   8.126  37.408   8.185  39.197   9.024
  41.107   9.241  42.649   9.995  46.755  10.208  49.643  10.303  54.312  12.833
  56.716  12.951  58.784  12.136  77.999  12.144
#Mann= 3 , 0 , 0
       0    .035       0       0    .035       0  77.999    .035       0
Bank Sta=0,77.999
XS Rating Curve= 0
Exp/Cntr=.3,.1

Type RM Length L Ch R = 1 ,465     ,66.09,66.09,66.09
XS GIS Cut Line= 2
      1616840.47       4854406.8 1616863.7596367 4854467.0190607
#Sta/Elev= 20
       0  12.309  10.368  12.286  12.176   12.18  16.552  10.478  22.126   10.46
  22.844  10.248  23.167   9.486  25.079   8.382  27.351   7.959  29.426   7.955
  32.404   8.206  34.239   9.322  36.736   9.365  38.571    9.98  43.709  10.059
   47.26  10.236  50.768  10.196  53.299  10.635  58.029  10.806  64.659  10.867
#Mann= 3 , 0 , 0
       0    .035       0       0    .035       0  64.659    .035       0
Bank Sta=0,64.659
XS Rating Curve= 0
Exp/Cntr=.3,.1

Type RM Length L Ch R = 1 ,464     ,58.21,58.21,58.21
XS GIS Cut Line= 3
      1616772.81      4854417.35      1616807.99       4854505.6
 1616807.9900367 4854505.6000921
#Sta/Elev= 22
       0  12.025  17.293  12.342  25.732  12.437   27.02  12.302  32.079  10.568
  39.161  10.145  40.193   9.889  40.696   9.452  42.295   8.671  44.652   8.079
  46.729   8.062  48.673   8.097  50.734   8.132   52.09   8.754  54.191   9.289
  56.128   10.25  60.636  10.093  66.205  12.841  68.068   12.86  70.197  12.267
  74.015  12.259   95.03  12.182
#Mann= 3 , 0 , 0
       0    .035       0       0    .035       0   95.03    .035       0
Bank Sta=0,95.03
XS Rating Curve= 0
Exp/Cntr=.3,.1

Type RM Length L Ch R = 1 ,463     ,56.84,56.84,56.84
XS GIS Cut Line= 3
      1616719.01      4854441.33      1616747.09      4854512.36
 1616747.0906984 4854512.3617667
#Sta/Elev= 22
       0  12.304  17.504  12.513  24.519  12.342  29.879  10.323  33.402  10.187
  37.709   10.32  39.201   9.436  40.975   9.096  43.548   8.149  46.475   7.986
  48.517   7.925  50.944   8.306  52.618   8.829  53.676    9.76  57.176  10.125
  60.708   10.12   63.29  10.666  63.653  12.824  66.202   12.73  66.302   10.77
  71.333  11.212  76.532  11.383
#Mann= 3 , 0 , 0
       0    .035       0       0    .035       0  76.532    .035       0
Bank Sta=0,76.532
XS Rating Curve= 0
Exp/Cntr=.3,.1

Type RM Length L Ch R = 1 ,462     ,50.05,50.05,50.05
XS GIS Cut Line= 2
      1616666.82      4854465.44 1616698.3499608 4854538.8199089
#Sta/Elev= 24
       0  12.022  16.845  12.174  18.887  13.133  20.117  13.018  21.483  12.629
  26.057  10.215  34.051  10.129  34.694  10.404  36.153  10.008  36.405   9.332
  38.313   8.798  40.777   8.364  43.666   7.774  45.673   7.916  47.709   8.294
  48.667   9.057  49.728   9.117  50.385   9.902  55.391  10.326  60.512  12.923
  62.286   12.85  64.497  12.241  70.564  12.132   79.93  12.168
#Mann= 3 , 0 , 0
       0    .035       0       0    .035       0   79.93    .035       0
Bank Sta=0,79.93
XS Rating Curve= 0
Exp/Cntr=.3,.1

Type RM Length L Ch R = 1 ,461     ,32.54,32.54,32.54
XS GIS Cut Line= 2
      1616626.76       4854495.1 1616653.9688562 4854563.5771214
#Sta/Elev= 23
       0  12.102   6.571  11.547   8.615  10.803   9.788  11.797  11.848  12.128
  12.619    10.6  14.952  10.156  23.946   9.882  24.504   9.329  26.546   8.535
  28.212   8.152  31.194   8.103   33.21    8.14  35.242   8.371  36.823    9.02
  38.035   9.196   38.91   9.733  45.727  10.242  50.234  12.908    51.3  12.925
  52.872  12.606  60.318   12.48  74.067  12.288
#Mann= 3 , 0 , 0
       0    .035       0       0    .035       0  74.067    .035       0
Bank Sta=0,74.067
XS Rating Curve= 0
Exp/Cntr=.3,.1

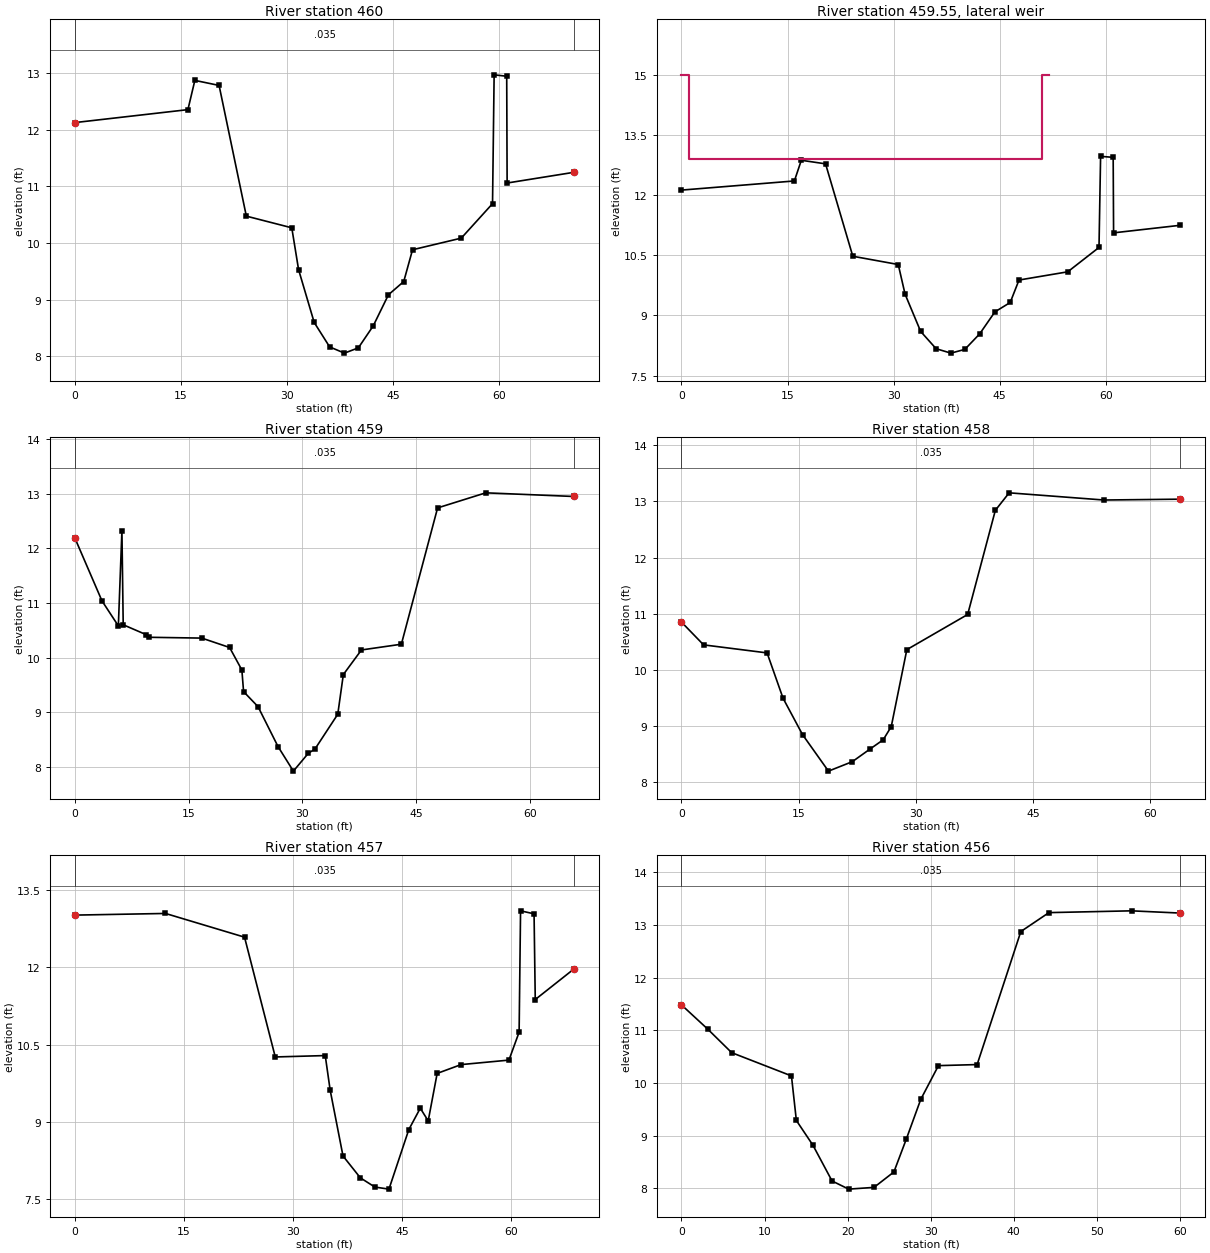
Type RM Length L Ch R = 1 ,460     ,65.78,65.78,65.78
XS GIS Cut Line= 3
       1616589.2      4854504.09      1616621.65      4854566.34
  1616621.650462 4854566.3408863
#Sta/Elev= 21
       0  12.125  15.969  12.353  16.951  12.869  20.379   12.78  24.233  10.475
   30.66  10.269  31.621   9.531  33.828     8.6  36.014   8.169  38.105   8.059
  40.073   8.152  42.175   8.539  44.328   9.088  46.493   9.322  47.736   9.882
  54.629  10.087   59.05  10.695  59.276  12.967  61.055  12.942  61.113  11.059
  70.571  11.248
#Mann= 3 , 0 , 0
       0    .035       0       0    .035       0  70.571    .035       0
Bank Sta=0,70.571
XS Rating Curve= 0
Exp/Cntr=.3,.1

Type RM Length L Ch R = 6 ,459.55  ,,,
Lateral Weir Pos= 0
Lateral Weir End=                ,                ,        ,c02
Lateral Weir Distance=1
Lateral Weir WD=3.0001
Lateral Weir Coef=1.66
Lateral Weir Is Ogee= 0
Lateral Weir WSCriteria=-1
Lateral Weir SE= 6
       0 15.0001       1 15.0001       1 12.9001      51 12.9001      51 15.0001
 52.0001 15.0001

Type RM Length L Ch R = 1 ,459     ,40.5,40.5,40.5
XS GIS Cut Line= 2
      1616539.58      4854542.91 1616564.3088607 4854603.1072266
#Sta/Elev= 23
       0  12.184   3.556   11.04   5.719  10.581    6.19  12.323    6.36  10.602
   9.422  10.419   9.711  10.373  16.726  10.358  20.394  10.186  22.011   9.774
  22.236   9.379  24.139   9.104  26.777   8.374  28.805   7.924  30.778   8.251
  31.651   8.328   34.66   8.965  35.393   9.691  37.781  10.141  43.048  10.246
  47.826   12.74  54.179  13.016  65.817  12.949
#Mann= 3 , 0 , 0
       0    .035       0       0    .035       0  65.817    .035       0
Bank Sta=0,65.817
XS Rating Curve= 0
Exp/Cntr=.3,.1

Type RM Length L Ch R = 1 ,458     ,45.74,45.74,45.74
XS GIS Cut Line= 2
      1616504.76        4854572. 1616536.4179647 4854627.3764399
#Sta/Elev= 16
       0  10.852   2.833  10.446  10.964  10.303  13.006   9.497  15.503   8.849
  18.823   8.199  21.887   8.368  24.112   8.589  25.829   8.756  26.863   8.991
  28.858  10.361  36.648  10.987  40.193  12.841   41.96  13.152  54.087  13.024
  63.896  13.039
#Mann= 3 , 0 , 0
       0    .035       0       0    .035       0  63.896    .035       0
Bank Sta=0,63.896
XS Rating Curve= 0
Exp/Cntr=.3,.1

Type RM Length L Ch R = 1 ,457     ,33.2,33.2,33.2
XS GIS Cut Line= 2
      1616453.66      4854579.44 1616492.1089352 4854636.2484268
#Sta/Elev= 21
       0  13.014  12.449  13.046  23.328  12.586  27.556  10.262  34.431  10.289
  35.107    9.62  36.875   8.341  39.263   7.917  41.264   7.738  43.199   7.698
  45.929   8.853  47.507   9.268  48.598   9.022   49.83   9.943  53.128  10.114
  59.706  10.201  61.106  10.743  61.305  13.097  63.163  13.039  63.327  11.376
  68.658   11.97
#Mann= 3 , 0 , 0
       0    .035       0       0    .035       0  68.658    .035       0
Bank Sta=0,68.658
XS Rating Curve= 0
Exp/Cntr=.3,.1

Type RM Length L Ch R = 1 ,456     ,41.98,41.98,41.98
XS GIS Cut Line= 3
      1616436.59      4854616.37       1616468.7      4854666.28
 1616468.7000557 4854666.2800866
#Sta/Elev= 18
       0  11.484   3.155  11.025   6.045  10.577  13.238  10.136   13.83    9.29
  15.826    8.82  18.124   8.142  20.126   7.987  23.175    8.02   25.57   8.313
  27.085   8.946  28.797   9.689   30.93  10.331  35.586  10.351  40.847  12.876
  44.229  13.235  54.168  13.269   60.06  13.226
#Mann= 3 , 0 , 0
       0    .035       0       0    .035       0   60.06    .035       0
Bank Sta=0,60.06
XS Rating Curve= 0
Exp/Cntr=.3,.1

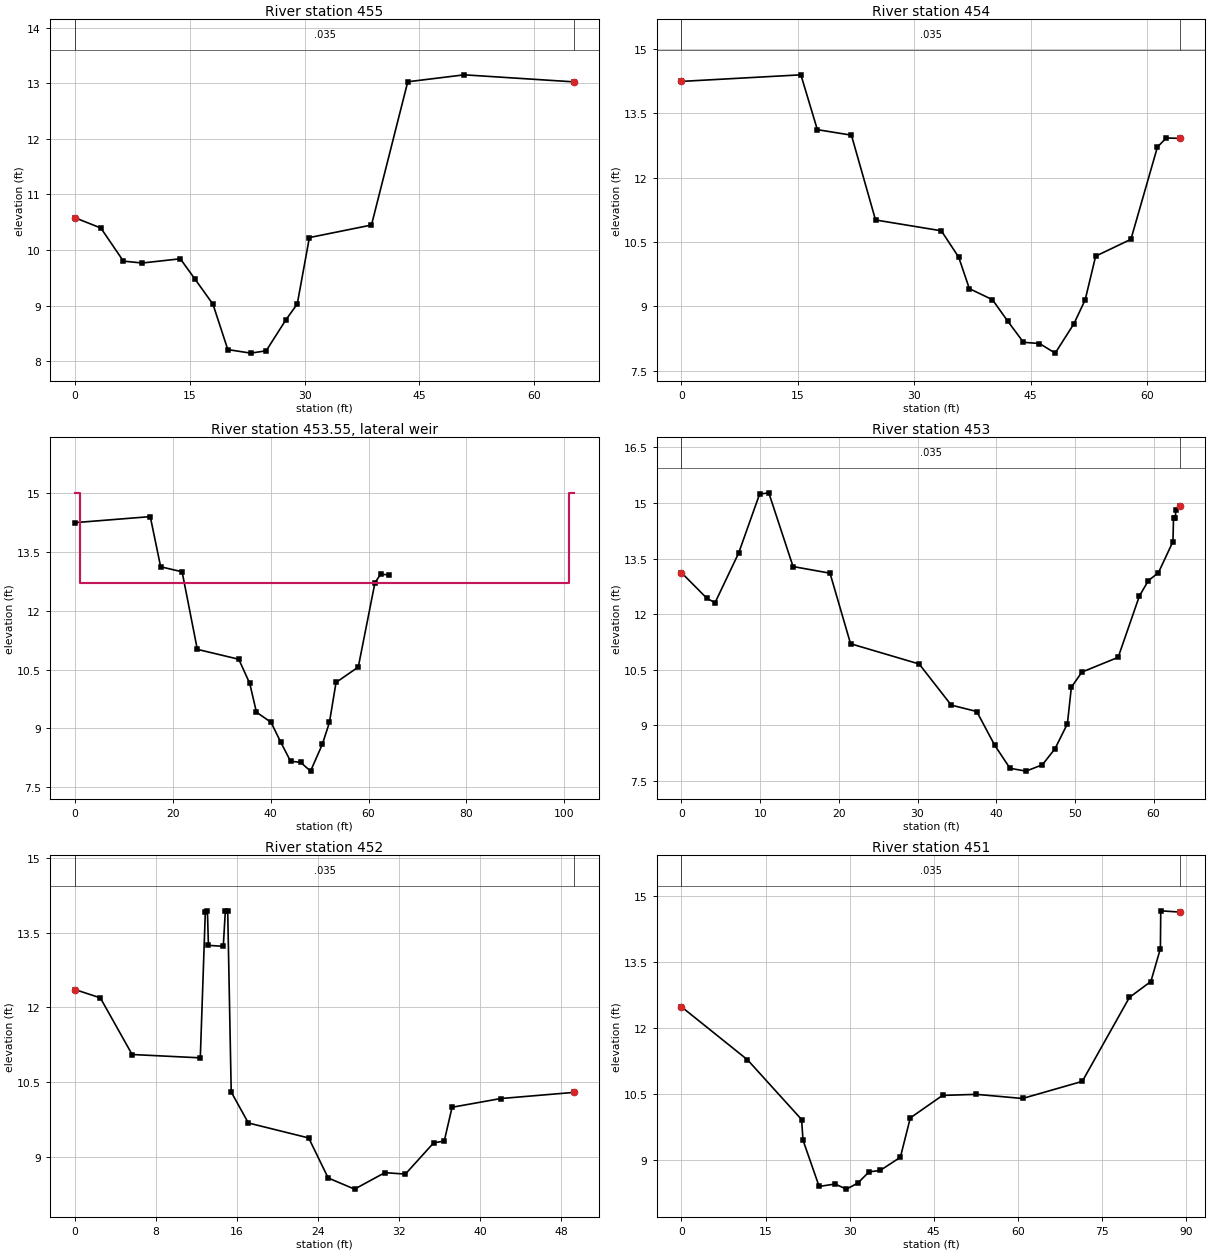
Type RM Length L Ch R = 1 ,455     ,79.96,79.96,79.96
XS GIS Cut Line= 3
      1616400.42      4854640.62      1616442.73      4854689.92
 1616442.7312372 4854689.9214416
#Sta/Elev= 17
       0  10.581   3.378  10.396   6.322     9.8   8.785   9.766  13.763   9.842
  15.646   9.482  18.026   9.024  19.968   8.207  22.958   8.143  24.978   8.185
  27.571   8.745  29.042   9.028  30.626  10.224  38.741   10.45   43.48   13.03
  50.869  13.155  65.202  13.028
#Mann= 3 , 0 , 0
       0    .035       0       0    .035       0  65.202    .035       0
Bank Sta=0,65.202
XS Rating Curve= 0
Exp/Cntr=.3,.1

Type RM Length L Ch R = 1 ,454     ,60.57,60.57,60.57
XS GIS Cut Line= 2
      1616333.75      4854666.77  1616361.228331 4854724.7764767
#Sta/Elev= 20
       0  14.241  15.387  14.394  17.506  13.117  21.896  12.989  25.002  11.014
  33.478  10.762  35.721  10.146  37.086   9.415  40.065   9.157   42.04   8.656
  44.059   8.165  46.124   8.137  48.148   7.913   50.56   8.597  52.012   9.155
  53.359  10.171  57.905  10.564  61.319  12.713  62.454  12.923  64.286  12.914
#Mann= 3 , 0 , 0
       0    .035       0       0    .035       0  64.286    .035       0
Bank Sta=0,64.286
XS Rating Curve= 0
Exp/Cntr=.3,.1

Type RM Length L Ch R = 6 ,453.55  ,,,
Lateral Weir Pos= 3
Lateral Weir End=                ,                ,        ,c01
Lateral Weir Distance=1
Lateral Weir WD=3.0001
Lateral Weir Coef=1.66
Lateral Weir Is Ogee= 0
Lateral Weir WSCriteria=-1
Lateral Weir SE= 6
       0 15.0001       1 15.0001       1 12.7001     101 12.7001     101 15.0001
102.0001 15.0001

Type RM Length L Ch R = 1 ,453     ,48.74,48.74,48.74
XS GIS Cut Line= 2
       1616285.6      4854682.38 1616297.5792384 4854744.1060754
#Sta/Elev= 29
       0  13.119   3.251  12.423   4.274   12.31   7.264  13.647    9.93   15.24
  11.098  15.275  14.183  13.284  18.879  13.105   21.49    11.2  30.208  10.653
  34.284   9.543  37.526    9.37  39.819   8.455  41.756   7.836  43.802    7.76
  45.866   7.932  47.467   8.363  49.045   9.037  49.551  10.025  50.887  10.434
  55.497  10.833  58.192  12.486   59.34  12.905  60.607  13.115  62.462  13.959
  62.535  14.608   62.78  14.606  62.819  14.821  63.416  14.928
#Mann= 3 , 0 , 0
       0    .035       0       0    .035       0  63.416    .035       0
Bank Sta=0,63.416
XS Rating Curve= 0
Exp/Cntr=.3,.1

Type RM Length L Ch R = 1 ,452     ,2.21,2.21,2.21
XS GIS Cut Line= 2
      1616236.27      4854701.75 1616254.8992227 4854745.8881584
#Sta/Elev= 22
       0  12.358   2.502  12.191    5.64  11.053  12.372  10.986  12.868  13.922
  13.077  13.929  13.173  13.246  14.642  13.227  14.842  13.932  15.077   13.94
  15.425    10.3  17.116   9.677  23.075   9.376  24.997   8.572  27.601   8.348
  30.594   8.679  32.618    8.65  35.414   9.278  36.457   9.313   37.23   9.993
   42.03  10.168  49.268  10.292
#Mann= 3 , 0 , 0
       0    .035       0       0    .035       0  49.268    .035       0
Bank Sta=0,49.268
XS Rating Curve= 0
Exp/Cntr=.3,.1

Type RM Length L Ch R = 1 ,451     ,4.8,4.8,4.8
XS GIS Cut Line= 2
      1616214.72      4854721.49 1616300.7404245 4854744.1774745
#Sta/Elev= 21
       0  12.483  11.775   11.28  21.446    9.92  21.689   9.453  24.572   8.399
  27.419   8.454  29.438   8.338  31.464   8.474  33.476   8.731  35.457   8.762
  39.068   9.062  40.843   9.958  46.599  10.469  52.652  10.493  60.869  10.399
  71.538  10.788  79.951  12.698   83.78  13.059   85.48  13.808   85.54  14.666
   89.06  14.637
#Mann= 3 , 0 , 0
       0    .035       0       0    .035       0   89.06    .035       0
Bank Sta=0,89.06
XS Rating Curve= 0
Exp/Cntr=.3,.1

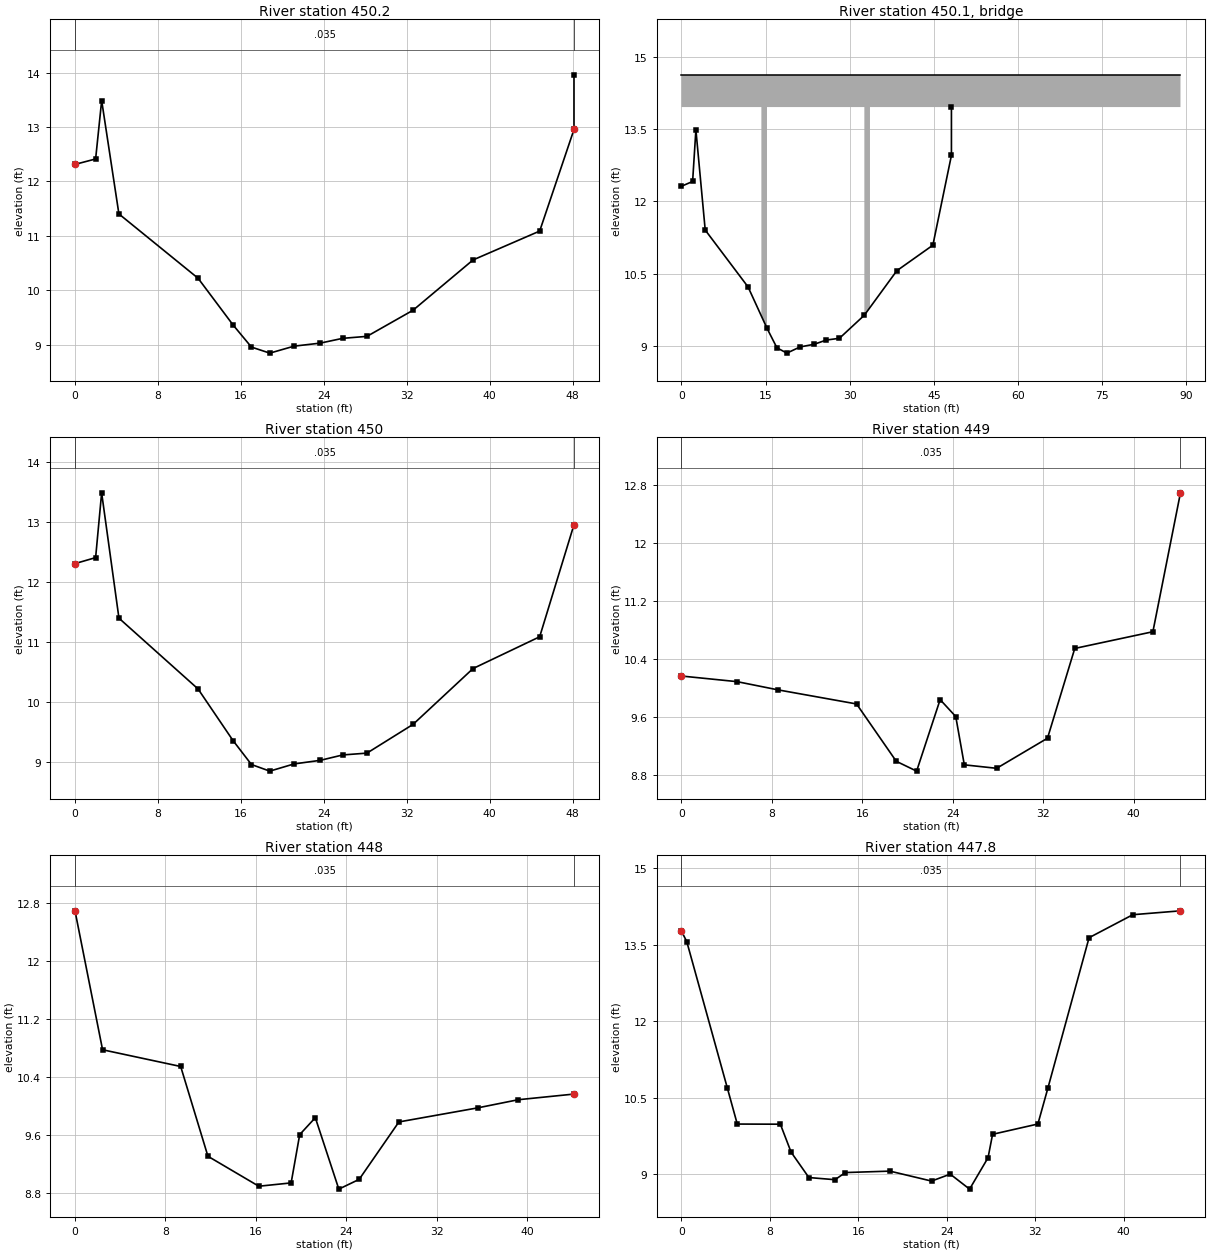
Type RM Length L Ch R = 1 ,450.2   ,20,20,20
XS GIS Cut Line= 3
      1616209.08      4854743.91      1616255.47      4854756.57
 1616255.4737611 4854756.5710264
#Sta/Elev= 17
       0  12.314  1.9897  12.414  2.5733  13.487  4.2354  11.404  11.872  10.222
  15.245  9.3639   17.02  8.9569  18.792  8.8459  21.127  8.9739  23.657  9.0299
  25.828  9.1179  28.164   9.154  32.607  9.6339  38.394  10.558  44.824  11.089
  48.134  12.956  48.134   13.96
#Mann= 3 , 0 , 0
       0    .035       0       0    .035       0  48.134    .035       0
Bank Sta=0,48.134
XS Rating Curve= 0
Exp/Cntr=.3,.1

Type RM Length L Ch R = 3 ,450.1   ,,,
BEGIN DESCRIPTION:
A11
END DESCRIPTION:
Bridge Culvert--1,0,-1,-1, 0
Deck Dist Width WeirC Skew NumUp NumDn MinLoCord MaxHiCord MaxSubmerge Is_Ogee
.5,19,1.44,0, 27, 27, , , .95, 0, 0,0,,
       0   11.77   14.25   14.25   15.25   15.25   21.44   21.65   24.52   27.36
   29.38   32.61   32.61   33.61   33.61   35.39      39   40.77   46.53   52.58
    60.8   71.46   79.87   83.69   85.39   85.44   88.97
   14.63   14.63   14.63   14.63   14.63   14.63   14.63   14.63   14.63   14.63
   14.63   14.63   14.63   14.63   14.63   14.63   14.63   14.63   14.63   14.63
   14.63   14.63   14.63   14.63   14.63   14.63   14.63
   13.96   13.96   13.96     9.4    9.36   13.96   13.96   13.96   13.96   13.96
   13.96   13.96    9.63     9.7   13.96   13.96   13.96   13.96   13.96   13.96
   13.96   13.96   13.96   13.96   13.96   13.96   13.96
       0   11.77   14.25   14.25   15.25   15.25   21.44   21.65   24.52   27.36
   29.38   32.61   32.61   33.61   33.61   35.39      39   40.77   46.53   52.58
    60.8   71.46   79.87   83.69   85.39   85.44   88.97
   14.63   14.63   14.63   14.63   14.63   14.63   14.63   14.63   14.63   14.63
   14.63   14.63   14.63   14.63   14.63   14.63   14.63   14.63   14.63   14.63
   14.63   14.63   14.63   14.63   14.63   14.63   14.63
   13.96   13.96   13.96     9.4    9.36   13.96   13.96   13.96   13.96   13.96
   13.96   13.96    9.63     9.7   13.96   13.96   13.96   13.96   13.96   13.96
   13.96   13.96   13.96   13.96   13.96   13.96   13.96
BR Coef=-1 , 0 , 0 ,1.25, 0 ,,,.8,-1,2,0,
WSPro=,,,, 1 ,,,, 0 ,,,, 0 ,,,,-1 ,-1 ,-1 , 0 , 0 , 0 , 0 , 0
BC Design=,, 0 ,, 0 ,,,,,,
BC HTab Sub Flow Pts= 40

Type RM Length L Ch R = 1 ,450     ,1.6,1.6,1.6
XS GIS Cut Line= 2
      1616209.08      4854743.91      1616255.47      4854756.57
#Sta/Elev= 16
       0   12.31    1.99 12.4099  2.5701 13.4901  4.2401 11.4001 11.8701 10.2199
   15.24  9.3601   17.02  8.9599   18.79  8.8499   21.13    8.97 23.6601    9.03
   25.83  9.1199 28.1599  9.1501 32.6099  9.6299 38.3899 10.5601 44.8199 11.0901
 48.1301 12.9601
#Mann= 3 , 0 , 0
       0    .035       0       0    .035       0 48.1301    .035       0
Bank Sta=0,48.1301
XS Rating Curve= 0
Exp/Cntr=.3,.1

Type RM Length L Ch R = 1 ,449     ,12.65,12.65,12.65
XS GIS Cut Line= 2
      1616252.01      4854761.65 1616210.9346107 4854746.8216645
#Sta/Elev= 14
       0  10.161   4.929  10.083   8.529    9.97  15.487   9.775  18.999   8.983
  20.799   8.847  22.879   9.835  24.261   9.601  25.017   8.934  27.876   8.886
  32.376   9.302  34.786  10.542  41.696  10.773  44.135  12.692
#Mann= 3 , 0 , 0
       0    .035       0       0    .035       0  44.135    .035       0
Bank Sta=0,44.135
XS Rating Curve= 0
Exp/Cntr=.3,.1

Type RM Length L Ch R = 1 ,448     ,1.26,1.26,1.26
XS GIS Cut Line= 2
      1616207.54      4854757.42 1616188.1418399 4854750.8567127
#Sta/Elev= 14
       0  12.692   2.439  10.773   9.348  10.542  11.758   9.302  16.259   8.888
  19.117   8.934  19.874   9.601  21.256   9.835  23.335   8.848  25.135   8.983
  28.648   9.776  35.606    9.97  39.206  10.083  44.135  10.161
#Mann= 3 , 0 , 0
       0    .035       0       0    .035       0  44.135    .035       0
Bank Sta=0,44.135
XS Rating Curve= 0
Exp/Cntr=.3,.1

Type RM Length L Ch R = 1 ,447.8   ,7,7,7
#Sta/Elev= 20
       0  13.768     .48  13.563    4.16  10.685    5.05   9.985    8.95   9.982
    9.92   9.434   11.53   8.936   13.89   8.894   14.83   9.034   18.86   9.062
   22.63   8.867   24.32   9.003   26.07   8.709   27.74   9.325   28.15   9.784
   32.25   9.986   33.16  10.694   36.88  13.639   40.84   14.09   45.15  14.166
#Mann= 3 , 0 , 0
       0    .035       0       0    .035       0   45.15    .035       0
Bank Sta=0,45.15
XS Rating Curve= 0
Exp/Cntr=.3,.1