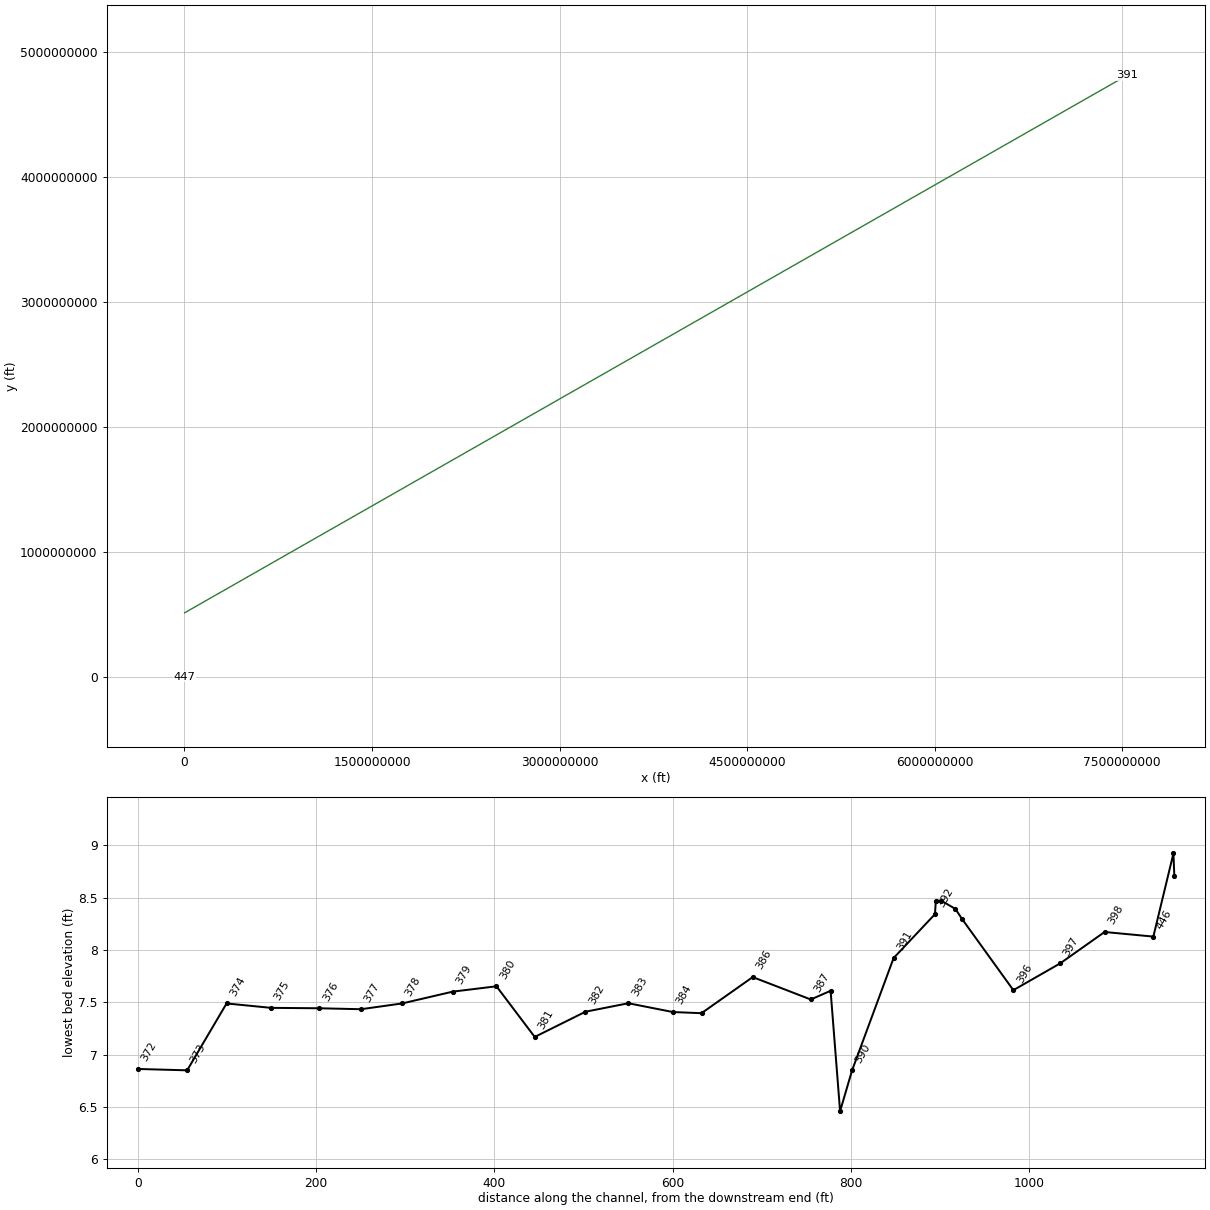
HEC-RAS study ozz_def.prj: ozzeri

--- ozz_def.g02 (geometry) --- (continued)

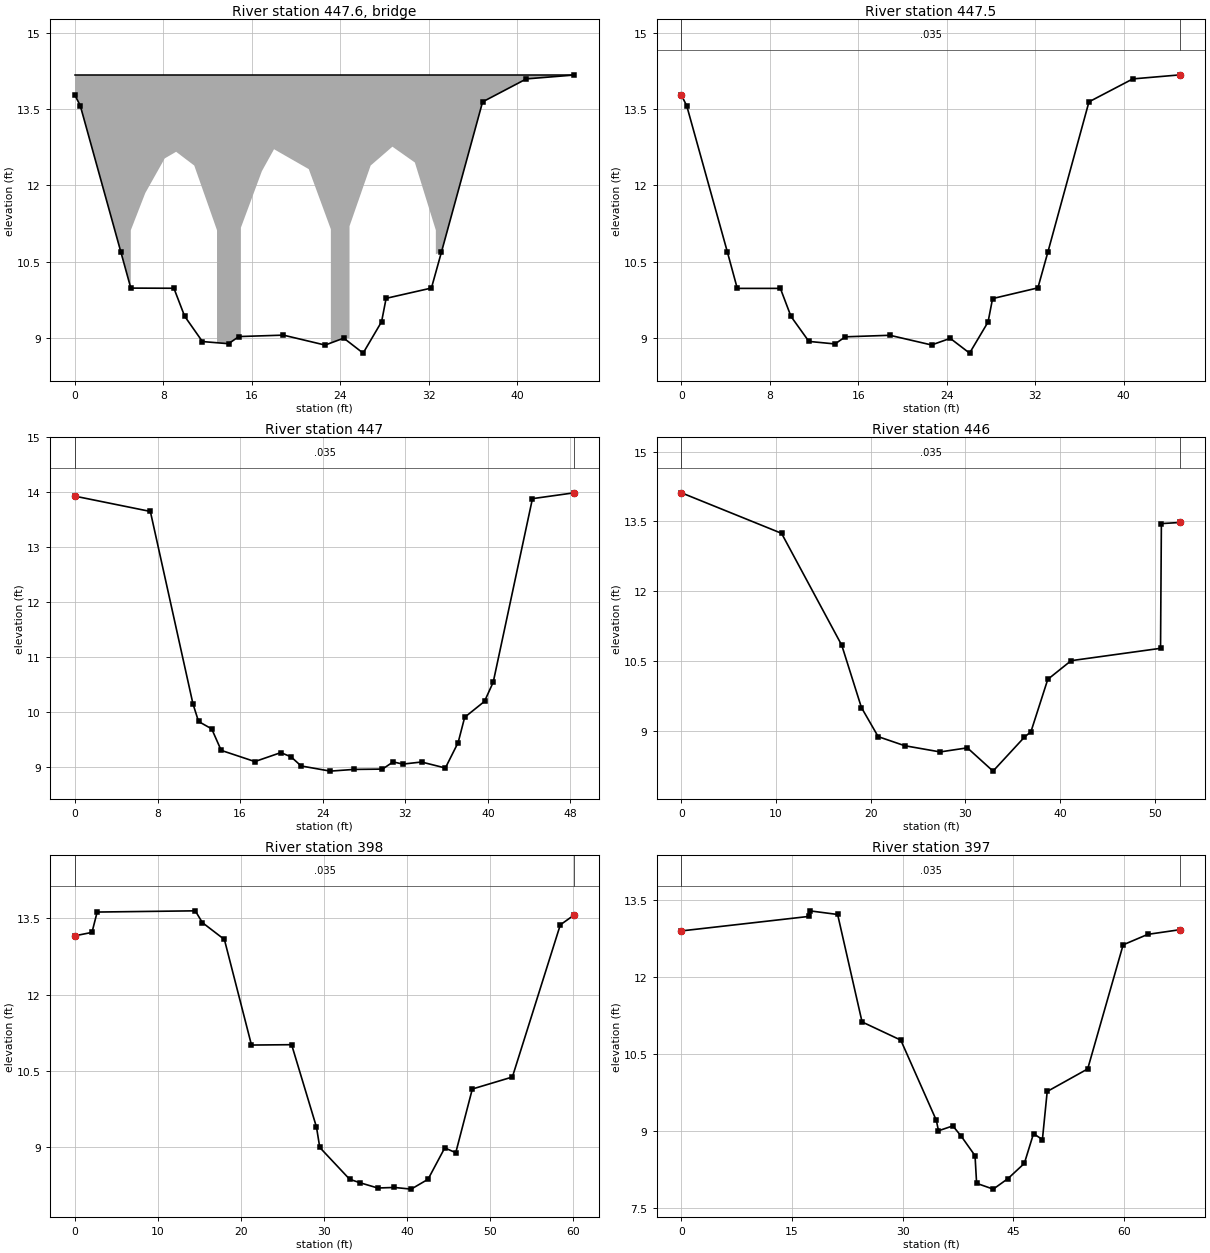
Type RM Length L Ch R = 3 ,447.6   ,,,
BEGIN DESCRIPTION:
Ponte FFSS
END DESCRIPTION:
Bridge Culvert--1,0,-1,-1, 0
Deck Dist Width WeirC Skew NumUp NumDn MinLoCord MaxHiCord MaxSubmerge Is_Ogee
.5,6,1.44,0, 30, 30, , , .95, 0, 0,0,,
       0     .48    4.16    5.05    5.05    6.36    8.12    9.15   10.79   12.85
   12.85   13.89   15.01   15.01   16.91   18.01   21.15   23.15   23.15   24.84
   24.84   26.75   28.72   30.75   32.65   32.65   33.15   36.87   40.84   45.15
   14.17   14.17   14.17   14.17   14.17   14.17   14.17   14.17   14.17   14.17
   14.17   14.17   14.17   14.17   14.17   14.17   14.17   14.17   14.17   14.17
   14.17   14.17   14.17   14.17   14.17   14.17   14.17   14.17   14.17   14.17
   13.77   13.56   10.69    9.98   11.12   11.85   12.53   12.66   12.39   11.12
     8.9    8.89    9.03   11.17   12.28   12.71   12.32   11.14     8.9       9
    11.2   12.39   12.76   12.45   11.12   10.65   10.69   13.64   14.09    14.1
       0     .48    4.16    5.05    5.05    6.36    8.12    9.15   10.79   12.85
   12.85   13.89   15.01   15.01   16.91   18.01   21.15   23.15   23.15   24.84
   24.84   26.75   28.72   30.75   32.65   32.65   33.15   36.87   40.84   45.15
   14.17   14.17   14.17   14.17   14.17   14.17   14.17   14.17   14.17   14.17
   14.17   14.17   14.17   14.17   14.17   14.17   14.17   14.17   14.17   14.17
   14.17   14.17   14.17   14.17   14.17   14.17   14.17   14.17   14.17   14.17
   13.77   13.56   10.69    9.98   11.12   11.85   12.53   12.66   12.39   11.12
     8.9    8.89    9.03   11.17   12.28   12.71   12.32   11.14     8.9       9
    11.2   12.39   12.76   12.45   11.12   10.65   10.69   13.64   14.09    14.1
BR Coef=-1 , 0 , 0 ,1.25, 0 ,,,.8,-1,2,0,
WSPro=,,,, 1 ,,,, 0 ,,,, 0 ,,,,-1 ,-1 ,-1 , 0 , 0 , 0 , 0 , 0
BC Design=,, 0 ,, 0 ,,,,,,

Type RM Length L Ch R = 1 ,447.5   ,1,1,1
#Sta/Elev= 20
       0   13.77     .48   13.56    4.16   10.69    5.05    9.98    8.95    9.98
    9.91    9.43   11.53    8.94   13.89    8.89   14.83    9.03   18.86    9.06
   22.63    8.87   24.32       9   26.07    8.71   27.74    9.32   28.15    9.78
   32.25    9.99   33.15   10.69   36.87   13.64   40.84   14.09   45.15   14.17
#Mann= 3 , 0 , 0
       0    .035       0       0    .035       0   45.15    .035       0
Bank Sta=0,45.15
XS Rating Curve= 0
Exp/Cntr=.3,.1

Type RM Length L Ch R = 1 ,447     ,22.52,22.52,22.52
XS GIS Cut Line= 2
      1616197.96      4854765.35   1616243.41606 4854778.4688629
#Sta/Elev= 23
       0   13.93   7.301  13.652  11.424  10.153   11.97   9.828  13.246   9.693
  14.164   9.302  17.427   9.098  19.939   9.261  20.926   9.185   21.91   9.018
  24.736   8.924  27.007   8.955  29.792   8.961  30.821   9.092  31.763   9.052
  33.575    9.09  35.883   8.981  37.122   9.445  37.754   9.904  39.675  10.194
  40.519  10.543   44.32  13.885  48.346  13.991
#Mann= 3 , 0 , 0
       0    .035       0       0    .035       0  48.346    .035       0
Bank Sta=0,48.346
XS Rating Curve= 0
Exp/Cntr=.3,.1

Type RM Length L Ch R = 1 ,446     ,54.71,54.71,54.71
XS GIS Cut Line= 2
      1616187.05      4854782.53 1616236.6142526  4854800.147957
#Sta/Elev= 16
       0  14.116  10.574  13.245  16.939  10.836  19.015   9.497  20.785   8.871
  23.585   8.676   27.33   8.542  30.208    8.63  32.921   8.129  36.218   8.856
  36.928   8.978  38.704  10.103  41.168  10.505  50.619  10.771  50.707  13.454
  52.724  13.479
#Mann= 3 , 0 , 0
       0    .035       0       0    .035       0  52.724    .035       0
Bank Sta=0,52.724
XS Rating Curve= 0
Exp/Cntr=.3,.1

Type RM Length L Ch R = 1 ,398     ,49.84,49.84,49.84
XS GIS Cut Line= 2
      1616157.98      4854821.61 1616208.1291475 4854852.2994783
#Sta/Elev= 22
       0  13.158   2.047  13.225    2.67  13.625  14.493  13.649  15.346  13.417
  17.999  13.085  21.263  11.008    26.1  11.015  29.094   9.393   29.49   8.993
  33.091   8.367  34.309     8.3  36.477   8.195  38.486   8.206  40.501   8.173
  42.534   8.367  44.547   8.984  45.875    8.89   47.87  10.143  52.695  10.379
  58.469  13.373  60.119  13.565
#Mann= 3 , 0 , 0
       0    .035       0       0    .035       0  60.119    .035       0
Bank Sta=0,60.119
XS Rating Curve= 0
Exp/Cntr=.3,.1

Type RM Length L Ch R = 1 ,397     ,52.53,52.53,52.53
XS GIS Cut Line= 2
      1616126.49      4854852.05 1616177.6984868 4854896.2486939
#Sta/Elev= 22
       0    12.9  17.274  13.182  17.384  13.291  21.184   13.22  24.498  11.128
  29.751  10.774  34.576   9.211  34.863   9.009  36.813   9.104  37.956   8.902
  39.822   8.524  40.036   7.986  42.295   7.873  44.299   8.079   46.51   8.374
  47.753   8.953  48.961   8.838  49.611   9.774  55.102  10.213  59.912  12.629
  63.259  12.833  67.688  12.925
#Mann= 3 , 0 , 0
       0    .035       0       0    .035       0  67.688    .035       0
Bank Sta=0,67.688
XS Rating Curve= 0
Exp/Cntr=.3,.1

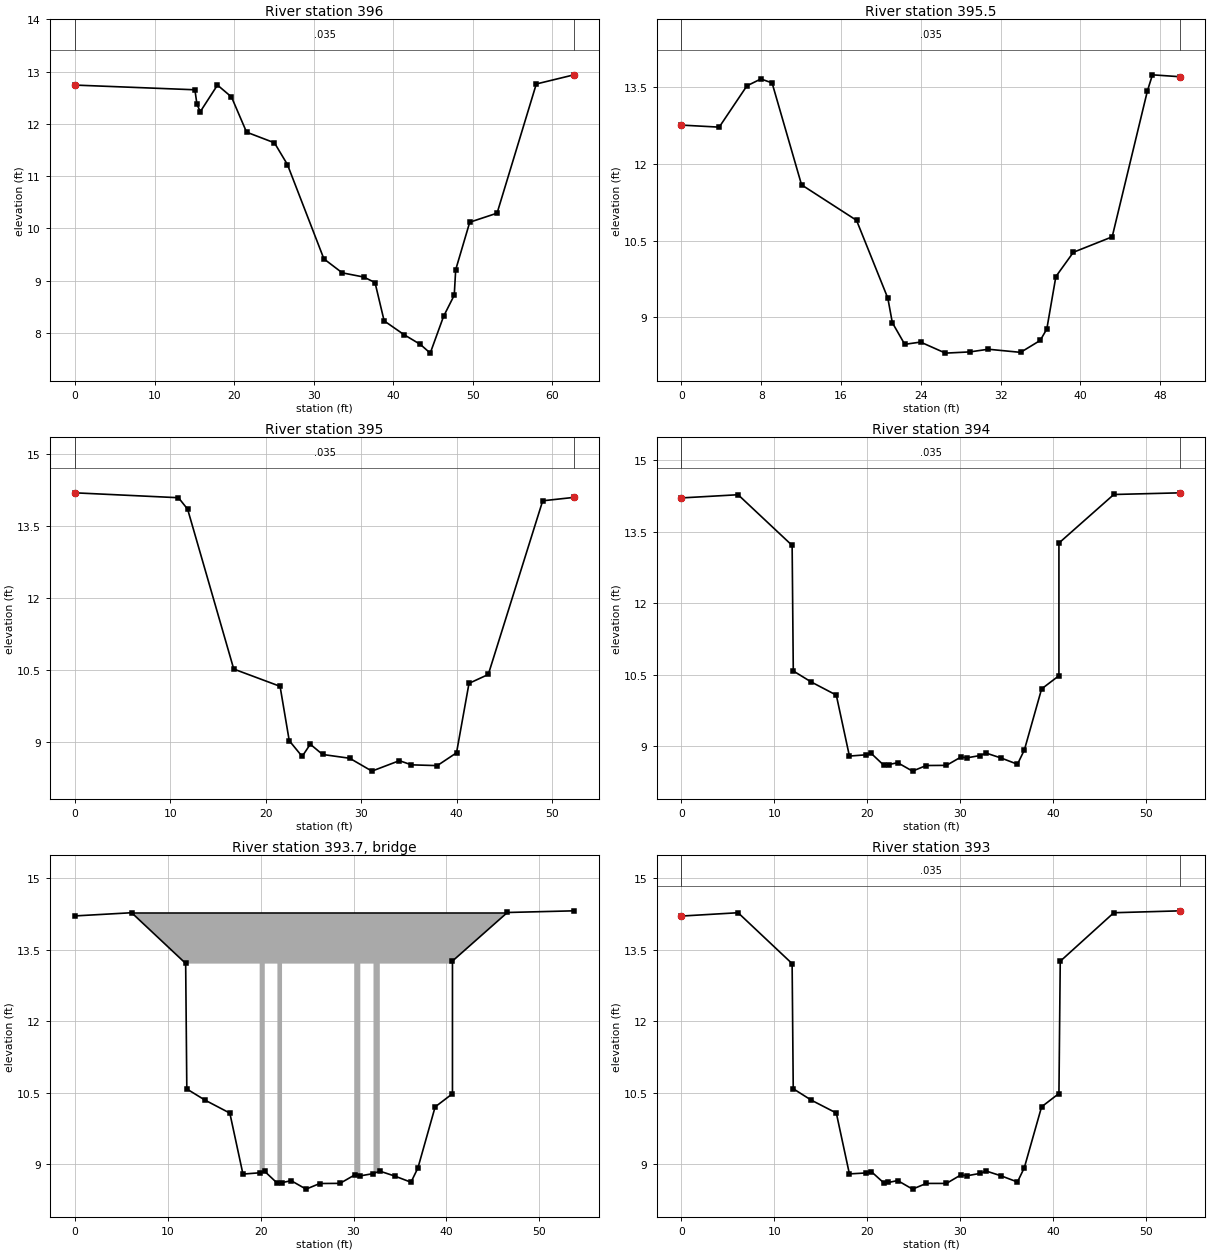
Type RM Length L Ch R = 1 ,396     ,57.63,57.63,57.63
XS GIS Cut Line= 2
      1616096.41      4854876.71      1616129.67      4854929.81
#Sta/Elev= 24
       0  12.742  15.078  12.652  15.335  12.373  15.753  12.233  17.913  12.742
  19.674  12.515  21.572  11.842  25.076  11.638  26.708  11.223  31.296   9.419
  33.602   9.152    36.3   9.072  37.723   8.966  38.869   8.234  41.369    7.97
   43.42   7.784  44.665   7.617  46.342    8.32  47.684   8.725  47.865   9.211
  49.631   10.12  53.068  10.293      58  12.763   62.74  12.938
#Mann= 3 , 0 , 0
       0    .035       0       0    .035       0   62.74    .035       0
Bank Sta=0,62.74
XS Rating Curve= 0
Exp/Cntr=.3,.1

Type RM Length L Ch R = 1 ,395.5   ,7.34,7.34,7.34
XS GIS Cut Line= 2
      1616055.12      4854905.96 1616072.0293567 4854952.9482125
#Sta/Elev= 23
       0  12.757   3.784  12.717   6.564  13.525   7.962  13.659   9.085  13.582
   12.04  11.589  17.552  10.895  20.691   9.372   21.14   8.894  22.385    8.47
  23.972   8.514  26.467   8.298  28.917   8.322  30.762   8.374  34.001   8.313
  35.965   8.546  36.628   8.769  37.537   9.795   39.29   10.27  43.183  10.572
  46.712  13.424  47.219   13.74  50.028  13.702
#Mann= 3 , 0 , 0
       0    .035       0       0    .035       0  50.028    .035       0
Bank Sta=0,50.028
XS Rating Curve= 0
Exp/Cntr=.3,.1

Type RM Length L Ch R = 1 ,395     ,16.01,16.01,16.01
XS GIS Cut Line= 3
      1616047.58      4854906.69      1616065.94      4854955.36
 1616065.9410946 4854955.3629018
#Sta/Elev= 19
       0  14.195  10.841  14.093  11.801  13.854  16.634  10.521  21.487  10.161
  22.447   9.028    23.8   8.699  24.652   8.954  25.944    8.74  28.788   8.661
   31.11   8.393  33.988   8.611  35.249   8.524  37.958   8.508  39.975   8.775
  41.282  10.223  43.303  10.408  49.004  14.029  52.283    14.1
#Mann= 3 , 0 , 0
       0    .035       0       0    .035       0  52.283    .035       0
Bank Sta=0,52.283
XS Rating Curve= 0
Exp/Cntr=.3,.1

Type RM Length L Ch R = 1 ,394     ,6,6,6
XS GIS Cut Line= 3
      1616042.47      4854904.37      1616066.52      4854969.77
 1616067.1464286 4854971.4734691
#Sta/Elev= 27
       0  14.212   6.101  14.279   11.92  13.214  12.044  10.577  13.993  10.344
  16.677   10.07   18.09   8.789  19.886   8.816  20.439   8.845  21.799   8.595
  22.304    8.61  23.287    8.65  24.885   8.473  26.366   8.591   28.54   8.594
  30.113    8.77  30.734   8.752  32.147     8.8  32.828   8.851  34.419   8.749
  36.188   8.618  36.934   8.918  38.789    10.2  40.655  10.477  40.655  13.264
  46.566  14.284  53.745  14.319
#Mann= 3 , 0 , 0
       0    .035       0       0    .035       0  53.745    .035       0
Bank Sta=0,53.745
XS Rating Curve= 0
Exp/Cntr=.3,.1

Type RM Length L Ch R = 3 ,393.7   ,,,
BEGIN DESCRIPTION:
Ponte di Montuolo
END DESCRIPTION:
Bridge Culvert--1,0,-1,-1, 0
Deck Dist Width WeirC Skew NumUp NumDn MinLoCord MaxHiCord MaxSubmerge Is_Ogee
.5,5,1.44,0, 20, 20, , , .95, 0, 0,0,,
     6.1   11.92   19.89   19.89   20.44   20.44    21.8    21.8    22.3    22.3
   30.11   30.11   30.73   30.73   32.15   32.15   32.83   32.83   40.66   46.57
   14.28   14.28   14.28   14.28   14.28   14.28   14.28   14.28   14.28   14.28
   14.28   14.28   14.28   14.28   14.28   14.28   14.28   14.28   14.28   14.28
   14.28   13.21   13.21    8.81    8.84   13.21   13.21     8.6    8.61   13.21
   13.21    8.77    8.75   13.21   13.21     8.8    8.85   13.21   13.21   14.28
     6.1   11.92   19.89   19.89   20.44   20.44    21.8    21.8    22.3    22.3
   30.11   30.11   30.73   30.73   32.15   32.15   32.83   32.83   40.66   46.57
   14.28   14.28   14.28   14.28   14.28   14.28   14.28   14.28   14.28   14.28
   14.28   14.28   14.28   14.28   14.28   14.28   14.28   14.28   14.28   14.28
   14.28   13.21   13.21    8.81    8.84   13.21   13.21     8.6    8.61   13.21
   13.21    8.77    8.75   13.21   13.21     8.8    8.85   13.21   13.21   14.28
BR Coef=-1 , 0 , 0 ,1.25, 0 ,,,.8,-1,2,0,
WSPro=,,,, 1 ,,,, 0 ,,,, 0 ,,,,-1 ,-1 ,-1 , 0 , 0 , 0 , 0 , 0
BC Design=,, 0 ,, 0 ,,,,,,
BC HTab Sub Flow Pts= 40

Type RM Length L Ch R = 1 ,393     ,1,1,1
XS GIS Cut Line= 3
      1616040.42      4854911.21      1616061.21      4854967.87
 1616061.8369332 4854969.5786116
#Sta/Elev= 27
       0   14.21     6.1   14.28   11.92   13.21   12.04   10.58   13.99   10.34
   16.68   10.07   18.09    8.79   19.89    8.81   20.44    8.84    21.8     8.6
    22.3    8.61   23.29    8.65   24.89    8.47   26.37    8.59   28.54    8.59
   30.11    8.77   30.73    8.75   32.15     8.8   32.83    8.85   34.42    8.75
   36.19    8.62   36.93    8.92   38.79    10.2   40.66   10.48    40.8   13.26
   46.57   14.28   53.75   14.32
#Mann= 3 , 0 , 0
       0    .035       0       0    .035       0   53.75    .035       0
Bank Sta=0,53.75
XS Rating Curve= 0
Exp/Cntr=.3,.1

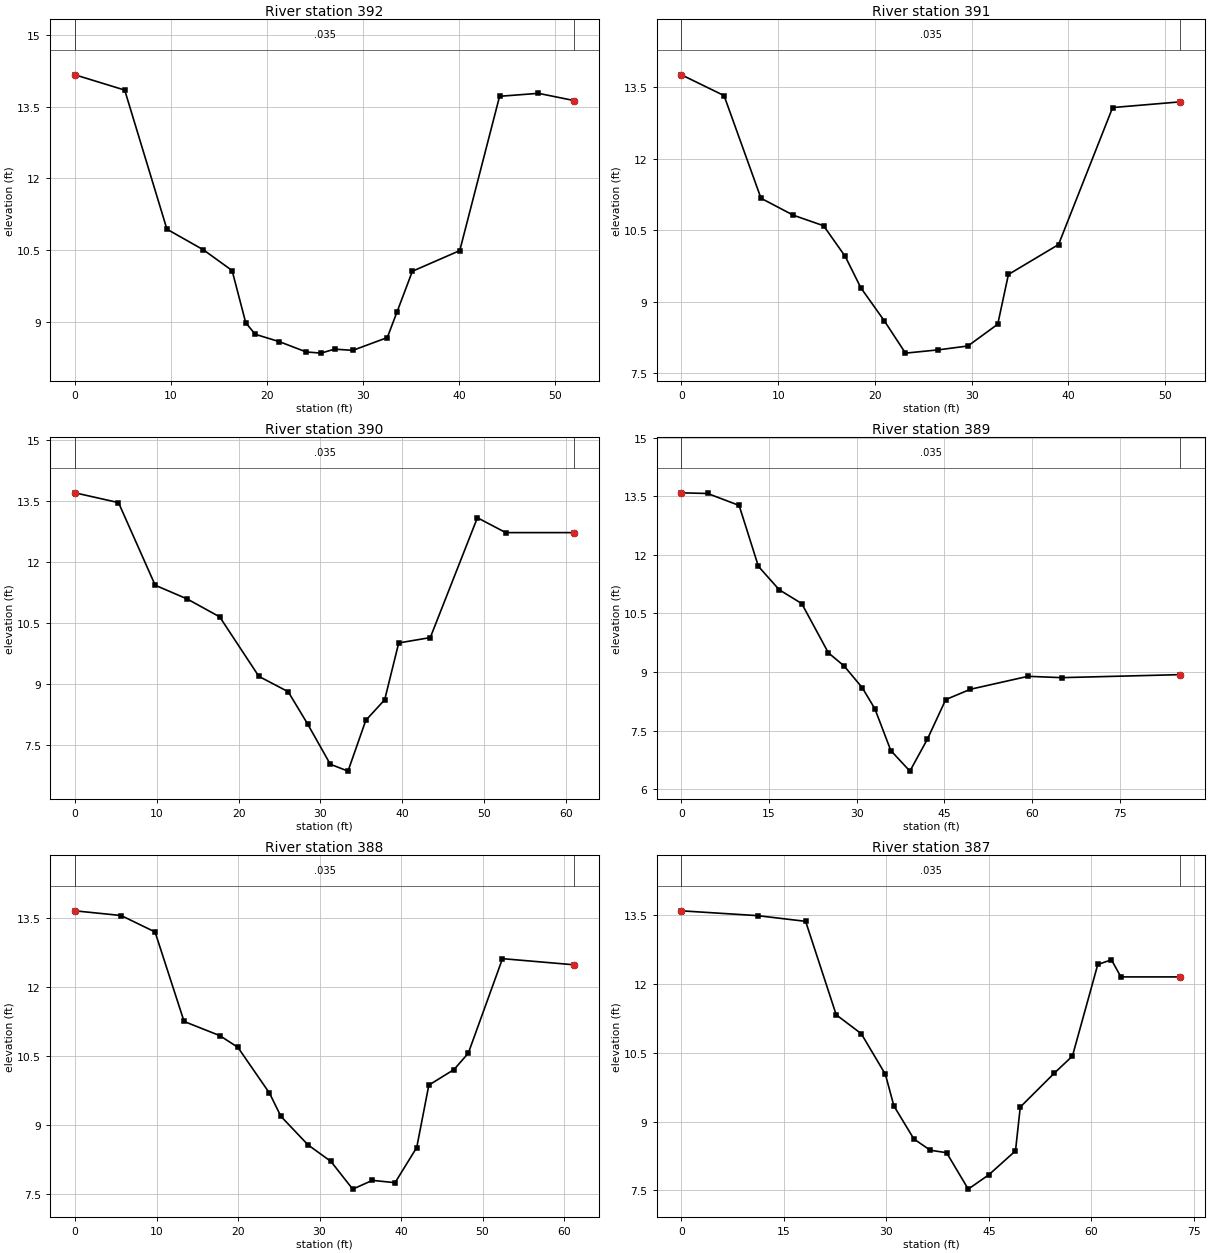
Type RM Length L Ch R = 1 ,392     ,46.38,46.38,46.38
XS GIS Cut Line= 3
      1616036.33       4854916.3 1616047.2194381 4854958.0943823
 1616047.2204461  4854958.098251
#Sta/Elev= 19
       0  14.163   5.174  13.844   9.567  10.935   13.35  10.505  16.352   10.07
   17.77   8.978  18.757   8.737  21.263   8.583  24.061   8.368  25.599   8.343
  27.013   8.426  28.915   8.401  32.501   8.668  33.524   9.209  35.112  10.055
  40.044  10.487  44.189  13.714  48.231  13.776  51.934  13.625
#Mann= 3 , 0 , 0
       0    .035       0       0    .035       0  51.934    .035       0
Bank Sta=0,51.934
XS Rating Curve= 0
Exp/Cntr=.3,.1

Type RM Length L Ch R = 1 ,391     ,46.59,46.59,46.59
XS GIS Cut Line= 2
       1616003.3      514854920.7541616005.998184814854970.99896
#Sta/Elev= 16
       0  13.766   4.404   13.33   8.222  11.175  11.566  10.819  14.692  10.598
  16.927   9.955  18.549   9.294  20.968   8.603  23.159   7.924  26.569   7.993
  29.615   8.074  32.698   8.531  33.801   9.575  38.983  10.203  44.575  13.079
  51.588  13.199
#Mann= 3 , 0 , 0
       0    .035       0       0    .035       0  51.588    .035       0
Bank Sta=0,51.588
XS Rating Curve= 0
Exp/Cntr=.3,.1

Type RM Length L Ch R = 1 ,390     ,13.47,13.47,13.47
XS GIS Cut Line= 2
      1615971.55      4854906.07 1615973.0885039 4854902.3636043
#Sta/Elev= 17
       0  13.699   5.318  13.458   9.804  11.425  13.697  11.089  17.686  10.647
  22.475   9.183  26.058   8.805  28.435   8.011  31.204   7.021  33.372   6.851
  35.548   8.101  37.856   8.607  39.569  10.005   43.43  10.137  49.188  13.086
  52.654   12.72  60.996   12.72
#Mann= 3 , 0 , 0
       0    .035       0       0    .035       0  60.996    .035       0
Bank Sta=0,60.996
XS Rating Curve= 0
Exp/Cntr=.3,.1

Type RM Length L Ch R = 1 ,389     ,10.63,10.63,10.63
XS GIS Cut Line= 2
      1615963.77      4854897.38      1615926.72      4854974.21
#Sta/Elev= 18
       0  13.587   4.482   13.57   9.869  13.264  13.164  11.704  16.724  11.105
  20.579  10.751   25.14   9.489  27.816   9.155  30.916     8.6  33.097   8.056
  35.819   6.987  39.087    6.46  42.084    7.28  45.218   8.292  49.427   8.556
  59.294   8.888  65.077   8.854   85.38   8.931
#Mann= 3 , 0 , 0
       0    .035       0       0    .035       0   85.38    .035       0
Bank Sta=0,85.38
XS Rating Curve= 0
Exp/Cntr=.3,.1

Type RM Length L Ch R = 1 ,388     ,22.24,22.24,22.24
XS GIS Cut Line= 2
      1615960.46      4854895.78 1615946.5352488 4854914.6378724
#Sta/Elev= 19
       0   13.65   5.662  13.548   9.824  13.191  13.384  11.249  17.777  10.941
  19.983  10.688  23.862   9.694   25.26   9.191  28.585   8.572  31.405   8.211
  34.073   7.611  36.489   7.801  39.268   7.751  41.926   8.514  43.411   9.868
  46.495  10.205   48.25  10.559  52.449  12.612  61.222  12.479
#Mann= 3 , 0 , 0
       0    .035       0       0    .035       0  61.222    .035       0
Bank Sta=0,61.222
XS Rating Curve= 0
Exp/Cntr=.3,.1

Type RM Length L Ch R = 1 ,387     ,65.15,65.15,65.15
XS GIS Cut Line= 2
      1615944.29      4854875.38 1615904.3505468 4854936.4891634
#Sta/Elev= 20
       0  13.588  11.151  13.483  18.179  13.359  22.657  11.324  26.323  10.913
   29.86  10.027  31.097   9.341  34.027    8.62   36.43   8.375  38.817   8.321
  41.988   7.528  45.007   7.841  48.904   8.361  49.607   9.315  54.598  10.055
  57.242  10.425  60.953   12.42  62.954  12.521  64.339  12.149  73.059  12.149
#Mann= 3 , 0 , 0
       0    .035       0       0    .035       0  73.059    .035       0
Bank Sta=0,73.059
XS Rating Curve= 0
Exp/Cntr=.3,.1

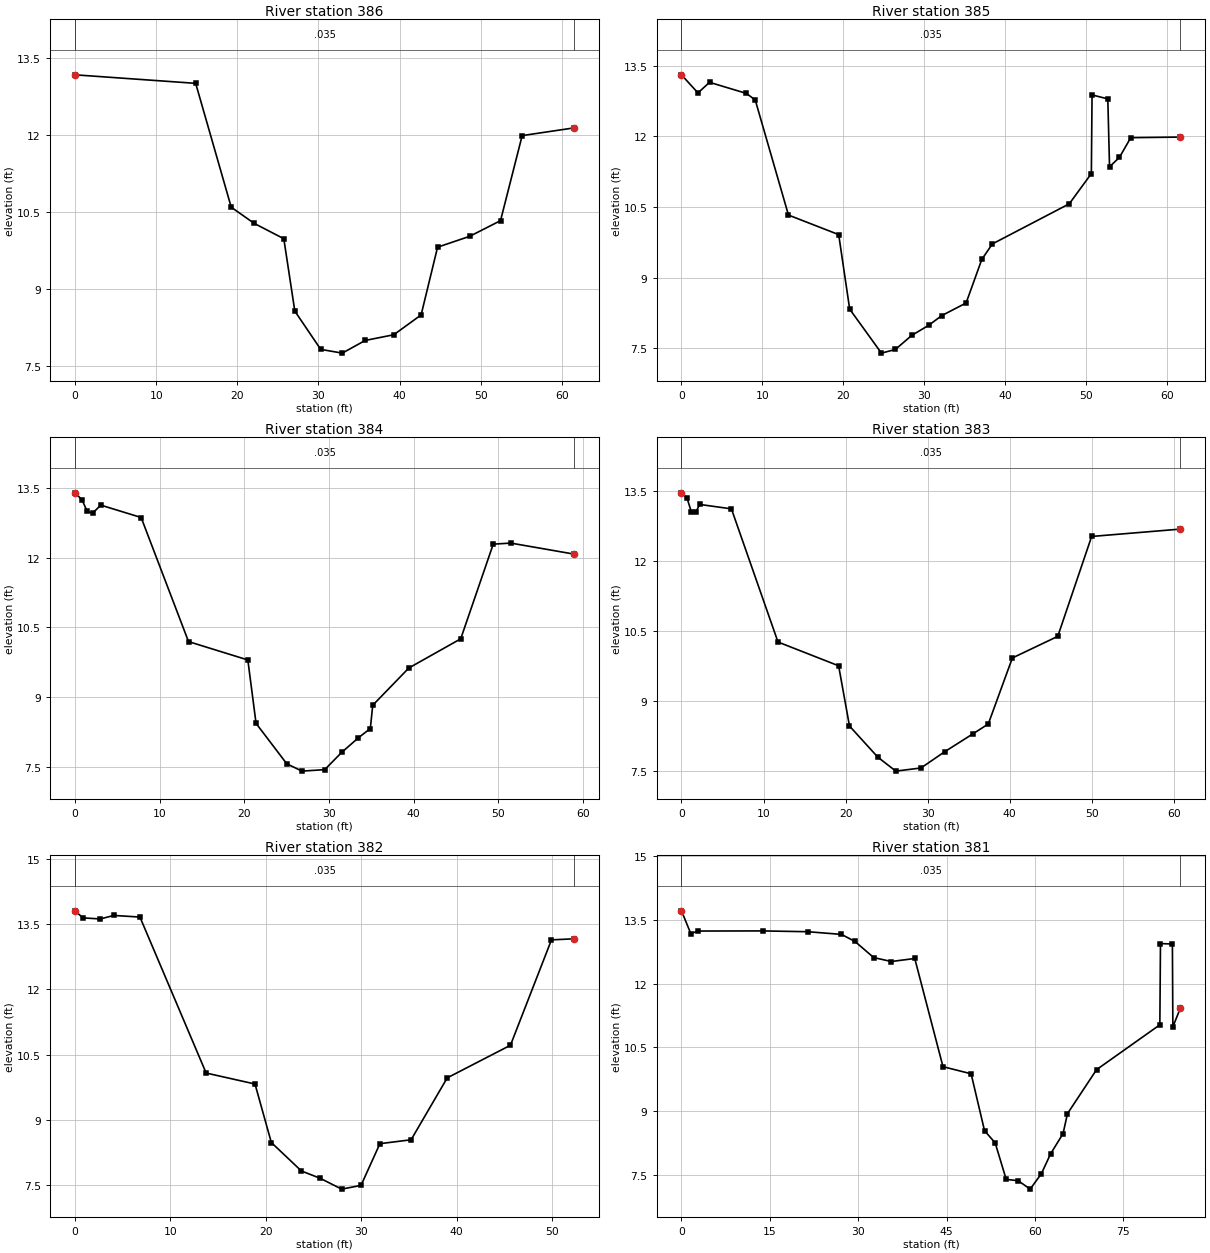
Type RM Length L Ch R = 1 ,386     ,57.45,57.45,57.45
XS GIS Cut Line= 2
      1615879.77      4854846.42      1615853.62      4854902.06
#Sta/Elev= 16
       0  13.164  14.872  12.998  19.251  10.585   22.08   10.27  25.732   9.971
  27.088   8.561  30.278   7.815  32.936   7.742   35.76   7.989  39.281     8.1
  42.651   8.486  44.679   9.806  48.641  10.018  52.437  10.323  55.102   11.98
   61.49   12.13
#Mann= 3 , 0 , 0
       0    .035       0       0    .035       0   61.49    .035       0
Bank Sta=0,61.49
XS Rating Curve= 0
Exp/Cntr=.3,.1

Type RM Length L Ch R = 1 ,385     ,32.12,32.12,32.12
XS GIS Cut Line= 3
      1615819.24      4854831.16      1615801.41      4854889.98
 1615801.4097388 4854889.9808616
#Sta/Elev= 24
       0  13.303   2.039  12.919   3.466  13.144   8.009  12.909   9.108   12.77
  13.211  10.327  19.414   9.912  20.771    8.33  24.693   7.397   26.41   7.475
  28.445   7.775  30.502   7.985  32.148   8.194  35.144   8.461  37.083   9.386
  38.385   9.714  47.885  10.566  50.609  11.207  50.694  12.877  52.641  12.792
  52.853  11.352  54.073   11.55  55.472  11.969  61.611  11.982
#Mann= 3 , 0 , 0
       0    .035       0       0    .035       0  61.611    .035       0
Bank Sta=0,61.611
XS Rating Curve= 0
Exp/Cntr=.3,.1

Type RM Length L Ch R = 1 ,384     ,49.95,49.95,49.95
XS GIS Cut Line= 2
      1615789.14      4854821.39 1615771.4127451  4854877.431322
#Sta/Elev= 21
       0  13.394.8329999  13.242   1.446  12.993   2.087  12.955    3.04   13.13
   7.813  12.863  13.408  10.194  20.413   9.799  21.383   8.435   25.01   7.566
  26.811   7.408   29.49    7.44  31.496   7.811  33.476   8.126  34.878   8.324
  35.162   8.825  39.432   9.627  45.554  10.254  49.393   12.29  51.464  12.313
  58.931  12.076
#Mann= 3 , 0 , 0
       0    .035       0       0    .035       0  58.931    .035       0
Bank Sta=0,58.931
XS Rating Curve= 0
Exp/Cntr=.3,.1

Type RM Length L Ch R = 1 ,383     ,48.12,48.12,48.12
XS GIS Cut Line= 2
      1615741.66      4854806.35   1615722.23096 4854863.9171555
#Sta/Elev= 19
       0  13.463    .666  13.358   1.223  13.043   1.785  13.061   2.221  13.214
   6.089  13.119  11.764  10.262  19.152   9.752  20.474    8.46  23.927   7.792
  26.122   7.492  29.191    7.56  32.102   7.911  35.544   8.295  37.387   8.503
  40.323    9.92  45.856  10.384  49.983  12.527  60.807  12.685
#Mann= 3 , 0 , 0
       0    .035       0       0    .035       0  60.807    .035       0
Bank Sta=0,60.807
XS Rating Curve= 0
Exp/Cntr=.3,.1

Type RM Length L Ch R = 1 ,382     ,56.96,56.96,56.96
XS GIS Cut Line= 2
      1615697.89      4854790.78 1615678.8018268 4854839.4253445
#Sta/Elev= 18
       0  13.805    .842  13.643   2.658  13.618   4.058  13.699   6.805  13.662
  13.741  10.078  18.862   9.826  20.571   8.482  23.724   7.828   25.71   7.658
  27.942   7.411   29.97   7.497  31.947   8.455  35.216   8.545  39.002   9.967
  45.629  10.717  49.924  13.138  52.285  13.162
#Mann= 3 , 0 , 0
       0    .035       0       0    .035       0  52.285    .035       0
Bank Sta=0,52.285
XS Rating Curve= 0
Exp/Cntr=.3,.1

Type RM Length L Ch R = 1 ,381     ,42.92,42.92,42.92
XS GIS Cut Line= 2
      1615655.02      4854742.67 1615624.8100354 4854821.6399074
#Sta/Elev= 27
       0  13.709   1.587  13.174   2.783  13.234  13.804  13.237  21.478  13.218
  27.165  13.155  29.452   12.99  32.636  12.611  35.627  12.518  39.609  12.589
  44.402  10.047  49.177    9.88  51.457   8.542  53.261   8.257  55.133   7.399
  57.161   7.368  59.206    7.17  61.106   7.533  62.677       8  64.788   8.475
  65.534   8.943  70.474   9.977   81.22  11.031  81.326   12.94   83.35  12.929
   83.43  10.983   84.72  11.429
#Mann= 3 , 0 , 0
       0    .035       0       0    .035       0   84.72    .035       0
Bank Sta=0,84.72
XS Rating Curve= 0
Exp/Cntr=.3,.1

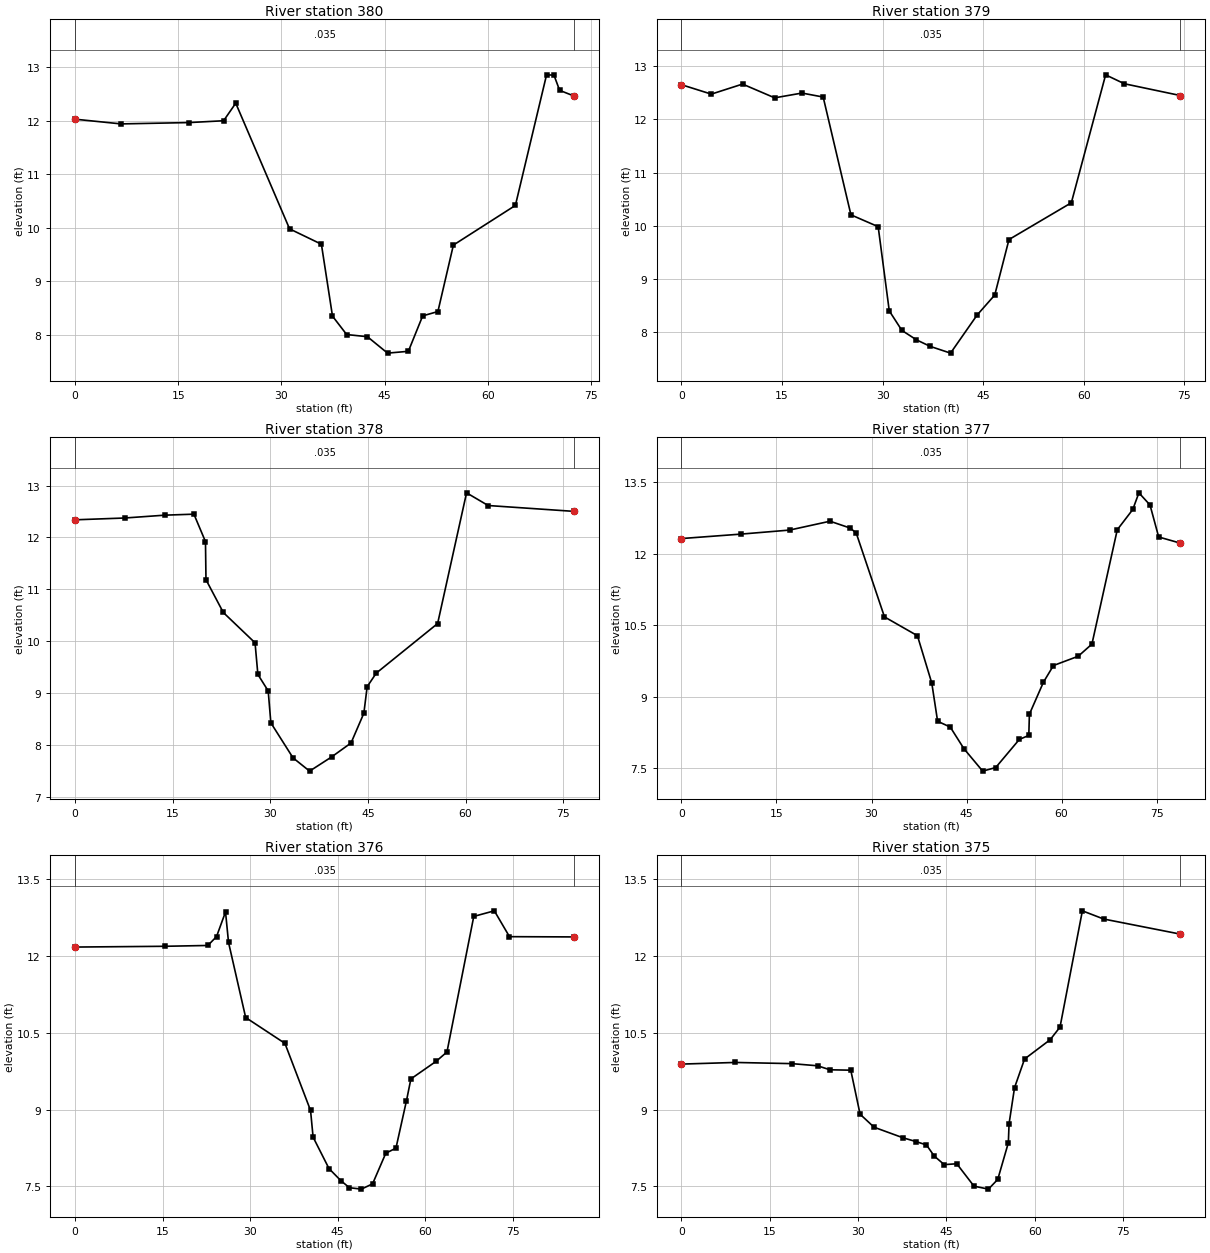
Type RM Length L Ch R = 1 ,380     ,49.04,49.04,49.04
XS GIS Cut Line= 2
      1615609.32      4854740.86 1615583.6502837 4854808.6592508
#Sta/Elev= 20
       0  12.025   6.702  11.937  16.603  11.962  21.596  11.996  23.362  12.324
  31.184   9.976  35.809   9.689  37.422   8.345  39.484   8.001  42.495   7.961
  45.424   7.654  48.447   7.688  50.528    8.35   52.74   8.431   54.99   9.673
  64.002  10.414  68.532  12.854  69.608  12.848  70.431  12.564  72.519  12.458
#Mann= 3 , 0 , 0
       0    .035       0       0    .035       0  72.519    .035       0
Bank Sta=0,72.519
XS Rating Curve= 0
Exp/Cntr=.3,.1

Type RM Length L Ch R = 1 ,379     ,56.91,56.91,56.91
XS GIS Cut Line= 3
      1615559.37      4854729.63      1615536.39      4854800.39
 1615536.3884565 4854800.3947529
#Sta/Elev= 20
       0  12.653   4.455  12.476   9.112  12.665  13.905  12.406  17.974  12.496
   21.14  12.421  25.279  10.205  29.344   9.982  30.998   8.398  32.877   8.031
  35.052   7.853  37.106    7.73  40.138   7.603  44.103    8.32  46.732   8.696
  48.855    9.74  58.157  10.432  63.272  12.839  66.066  12.671  74.435  12.449
#Mann= 3 , 0 , 0
       0    .035       0       0    .035       0  74.435    .035       0
Bank Sta=0,74.435
XS Rating Curve= 0
Exp/Cntr=.3,.1

Type RM Length L Ch R = 1 ,378     ,46.06,46.06,46.06
XS GIS Cut Line= 2
      1615506.83      4854713.79      1615479.65      4854785.38
#Sta/Elev= 22
       0  12.341   7.642  12.376   13.83  12.431  18.273   12.45  20.049   11.92
  20.126  11.185  22.788  10.552  27.664   9.967  28.099   9.356  29.685   9.038
  30.093   8.422  33.503   7.746  36.047    7.49  39.415   7.763   42.41   8.033
  44.381   8.607  44.891    9.12   46.29   9.382  55.717  10.339  60.161  12.862
  63.479  12.617   76.67  12.504
#Mann= 3 , 0 , 0
       0    .035       0       0    .035       0   76.67    .035       0
Bank Sta=0,76.67
XS Rating Curve= 0
Exp/Cntr=.3,.1

Type RM Length L Ch R = 1 ,377     ,46.66,46.66,46.66
XS GIS Cut Line= 2
      1615470.24      4854689.14 1615459.2208456 4854713.4166805
#Sta/Elev= 27
       0  12.318   9.459  12.412  17.069  12.496   23.45  12.682   26.66  12.537
   27.59  12.431  32.043  10.673  37.246  10.278  39.514   9.281  40.429   8.482
  42.425    8.36   44.59   7.905  47.546   7.435  49.597    7.51  53.331   8.101
  54.824   8.185  54.918    8.63  57.133   9.302  58.714   9.652  62.622   9.847
  64.786  10.102  68.787  12.503  71.234  12.928  72.201  13.278  73.956  13.022
  75.322  12.351  78.761  12.221
#Mann= 3 , 0 , 0
       0    .035       0       0    .035       0  78.761    .035       0
Bank Sta=0,78.761
XS Rating Curve= 0
Exp/Cntr=.3,.1

Type RM Length L Ch R = 1 ,376     ,54.28,54.28,54.28
XS GIS Cut Line= 2
      1615428.55      4854671.63    1615417.1289 4854694.7923895
#Sta/Elev= 25
       0  12.175  15.427   12.19  22.777  12.206  24.263   12.38  25.801  12.862
  26.315  12.267  29.253  10.798  35.983  10.293  40.375   8.981  40.811    8.46
   43.54   7.845  45.552   7.612  47.025   7.472  49.089   7.444   51.01   7.548
  53.272   8.146  55.012   8.245  56.811   9.169  57.574   9.598  61.914   9.943
  63.755  10.124  68.351  12.774  71.875  12.883  74.472  12.378   85.53  12.373
#Mann= 3 , 0 , 0
       0    .035       0       0    .035       0   85.53    .035       0
Bank Sta=0,85.53
XS Rating Curve= 0
Exp/Cntr=.3,.1

Type RM Length L Ch R = 1 ,375     ,49.86,49.86,49.86
XS GIS Cut Line= 2
      1615381.73      4854647.97 1615341.8347606 4854722.6310908
#Sta/Elev= 26
       0   9.888   9.135    9.92  18.748   9.897   23.12   9.855  25.223   9.777
  28.761   9.769  30.341    8.91  32.717   8.656   37.63    8.45  39.841   8.376
   41.62    8.31  42.931   8.094  44.635   7.926  46.764   7.943  49.688   7.506
  52.143   7.448  53.726   7.638  55.525   8.353  55.647   8.725  56.576   9.428
  58.279   9.987  62.629  10.364    64.3   10.61  68.099  12.879  71.719  12.719
   84.76  12.424
#Mann= 3 , 0 , 0
       0    .035       0       0    .035       0   84.76    .035       0
Bank Sta=0,84.76
XS Rating Curve= 0
Exp/Cntr=.3,.1

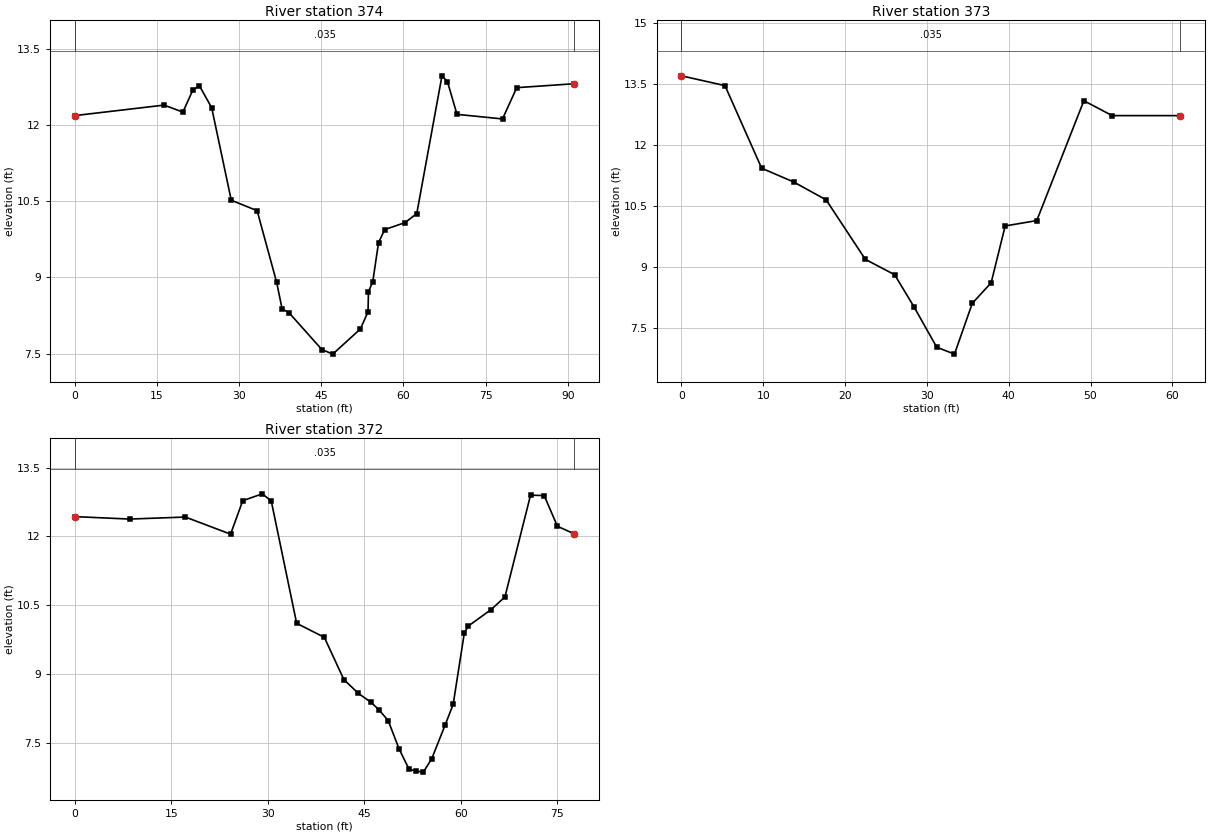
Type RM Length L Ch R = 1 ,374     ,44.24,44.24,44.24
XS GIS Cut Line= 2
      1615340.22      4854625.92 1615328.2537082 4854645.2376911
#Sta/Elev= 27
       0  12.183  16.272  12.389  19.707  12.251  21.545   12.69  22.735  12.767
  24.967  12.338  28.542  10.518   33.27  10.312  36.836   8.902  37.835   8.379
  39.089   8.305  45.086   7.581  47.084    7.49  52.123   7.984  53.528   8.323
  53.602   8.717  54.395   8.916  55.446   9.684  56.581   9.941  60.282  10.077
  62.429  10.255  67.034  12.965  68.038   12.85  69.776  12.207  78.095  12.117
  80.689  12.732   91.15  12.809
#Mann= 3 , 0 , 0
       0    .035       0       0    .035       0   91.15    .035       0
Bank Sta=0,91.15
XS Rating Curve= 0
Exp/Cntr=.3,.1

Type RM Length L Ch R = 1 ,373     ,55.42,55.42,55.42
XS GIS Cut Line= 2
      1615303.62      4854597.19 1615301.7812554  4854600.448899
#Sta/Elev= 17
       0  13.699   5.318  13.458   9.804  11.425  13.697  11.089  17.686  10.647
  22.475   9.183  26.058   8.805  28.435   8.011  31.204   7.021  33.372   6.851
  35.548   8.101  37.856   8.607  39.569  10.005   43.43  10.137  49.188  13.086
  52.654   12.72  60.996   12.72
#Mann= 3 , 0 , 0
       0    .035       0       0    .035       0  60.996    .035       0
Bank Sta=0,60.996
XS Rating Curve= 0
Exp/Cntr=.3,.1

Type RM Length L Ch R = 1 ,372     ,51.99,51.99,51.99
XS GIS Cut Line= 2
      1615257.42      4854572.62 1615241.7185745 4854597.1638073
#Sta/Elev= 29
       0  12.432   8.482  12.379  17.164  12.423  24.198   12.05  26.087  12.779
  29.137  12.929  30.527  12.772  34.475  10.107  38.782   9.801  41.815   8.882
  44.074    8.58  46.018   8.388  47.314   8.217  48.718   7.985    50.4   7.372
  51.952   6.928  53.023   6.888  54.184   6.864  55.476   7.154  57.554   7.886
  58.822   8.343  60.561   9.906   61.19  10.049  64.718  10.407  66.869  10.682
   70.85    12.9  72.978  12.891  75.025  12.223   77.61  12.059
#Mann= 3 , 0 , 0
       0    .035       0       0    .035       0   77.61    .035       0
Bank Sta=0,77.61
XS Rating Curve= 0
Exp/Cntr=.3,.1