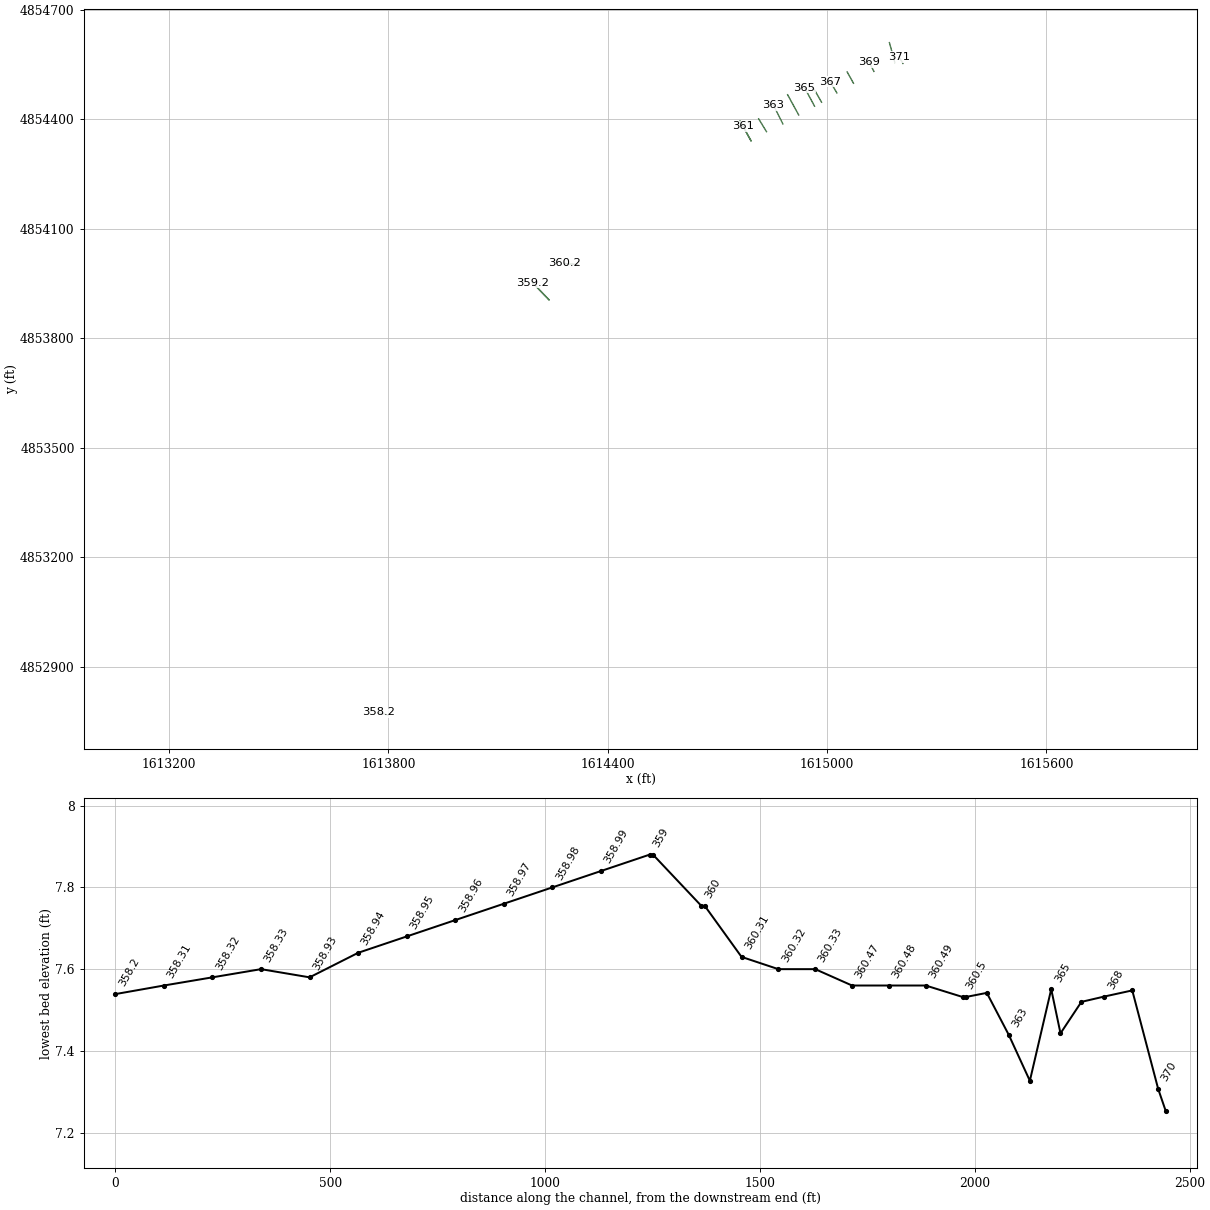
HEC-RAS study ozz_def.prj: ozzeri

--- ozz_def.g02 (geometry) --- (continued)

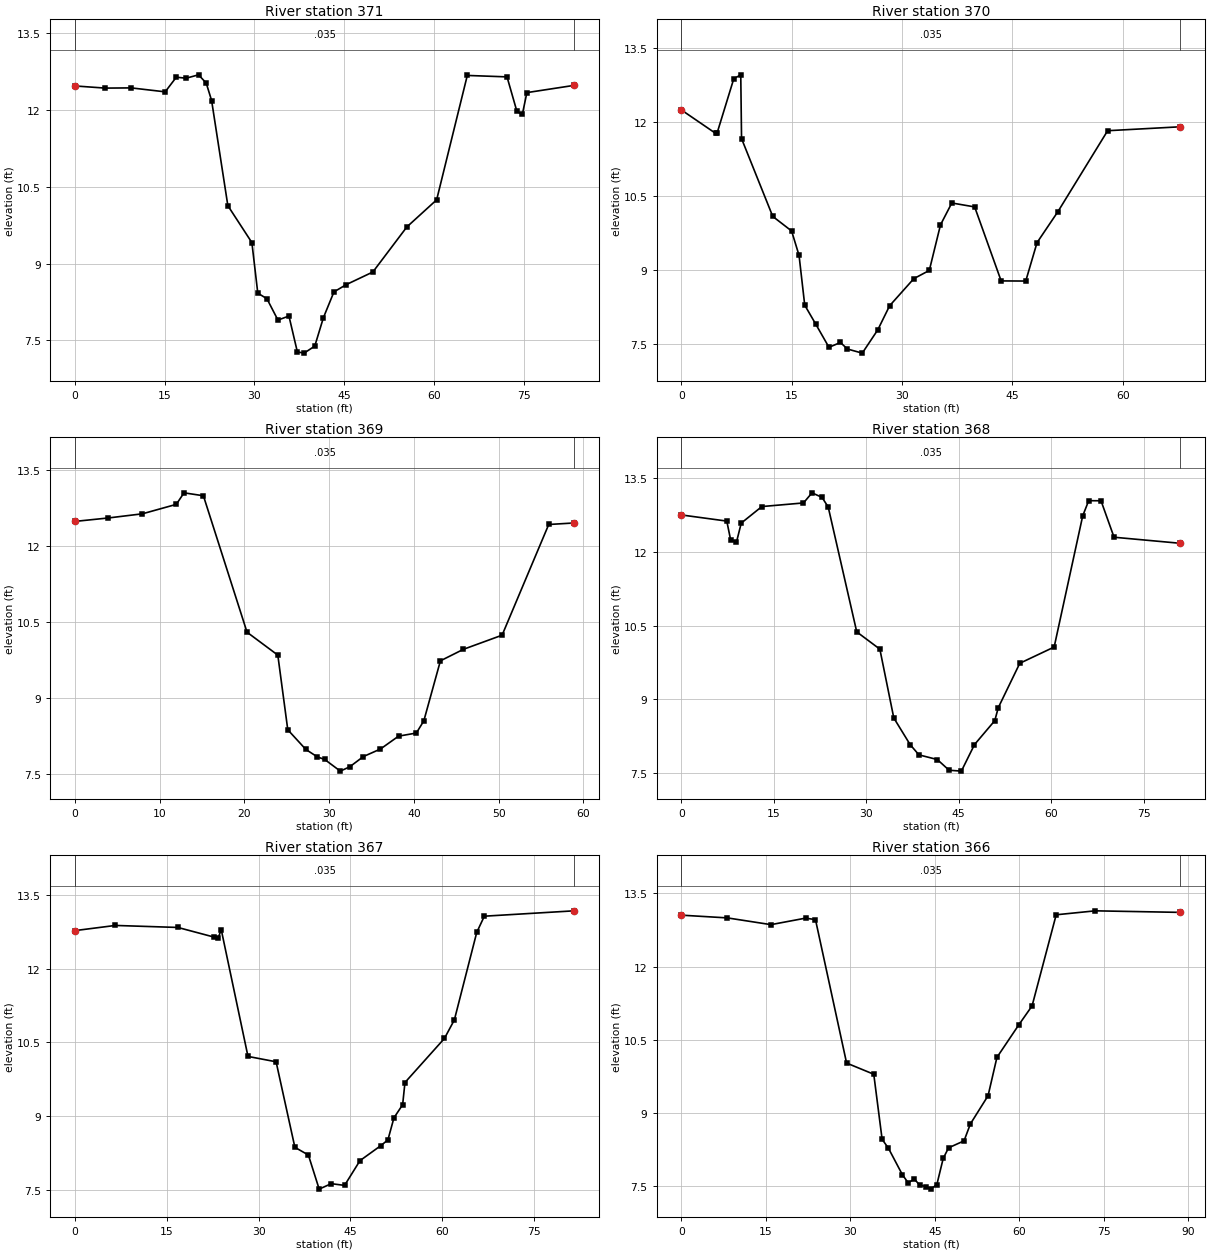
Type RM Length L Ch R = 1 ,371     ,17.89,17.89,17.89
XS GIS Cut Line= 2
      1615207.61      4854552.44 1615196.8036779  4854570.030938
#Sta/Elev= 30
       0  12.465    5.05  12.423   9.402  12.427  15.077   12.35  16.941  12.636
  18.582  12.616  20.651  12.682  21.938  12.522   22.84  12.181  25.557  10.129
  29.574   9.409  30.562   8.423  32.091   8.313  33.931   7.897  35.771   7.976
  37.177   7.276  38.305   7.252  40.089   7.389  41.534   7.944  43.297   8.447
  45.358   8.589  49.802   8.835  55.486   9.714  60.466  10.243   65.59   12.67
  72.233  12.642  73.886  11.968  74.789  11.908  75.552  12.335   83.43  12.476
#Mann= 3 , 0 , 0
       0    .035       0       0    .035       0   83.43    .035       0
Bank Sta=0,83.43
XS Rating Curve= 0
Exp/Cntr=.3,.1

Type RM Length L Ch R = 1 ,370     ,60.33,60.33,60.33
XS GIS Cut Line= 2
      1615185.26      4854555.26 1615170.4708777 4854609.5164788
#Sta/Elev= 28
       0  12.249   4.657  11.773   4.833  11.775   7.111  12.884   8.062  12.964
   8.168  11.668  12.411  10.086  14.972    9.79  15.985   9.294  16.757   8.282
  18.229   7.903  20.054   7.425  21.615   7.524  22.548   7.391  24.579   7.307
   26.69   7.781  28.302   8.271   31.59   8.821  33.692   8.988  35.212   9.914
  36.751  10.359  39.858  10.279  43.458   8.775  46.802   8.772  48.336   9.553
  51.183  10.185  57.934  11.828  67.834  11.908
#Mann= 3 , 0 , 0
       0    .035       0       0    .035       0  67.834    .035       0
Bank Sta=0,67.834
XS Rating Curve= 0
Exp/Cntr=.3,.1

Type RM Length L Ch R = 1 ,369     ,65.2,65.2,65.2
XS GIS Cut Line= 2
      1615128.12      4854530.68 1615114.9685989 4854555.9771837
#Sta/Elev= 24
       0  12.486    3.94  12.554    7.95  12.636  11.956  12.823  12.865  13.051
  15.153  12.993  20.302  10.295  23.936   9.842  25.111   8.366  27.236   7.978
  28.593    7.83  29.473   7.778  31.311   7.548  32.428   7.634  34.032   7.836
  36.048   7.985  38.188    8.24  40.282   8.301  41.164   8.541  43.123   9.729
  45.843   9.957  50.403  10.236  55.907  12.425  58.889  12.455
#Mann= 3 , 0 , 0
       0    .035       0       0    .035       0  58.889    .035       0
Bank Sta=0,58.889
XS Rating Curve= 0
Exp/Cntr=.3,.1

Type RM Length L Ch R = 1 ,368     ,53.14,53.14,53.14
XS GIS Cut Line= 2
      1615072.19      4854498.25 1615055.0015884 4854529.1198523
#Sta/Elev= 28
       0  12.754   7.356  12.629   7.976   12.25   8.922  12.196   9.703  12.588
  13.046  12.925  19.807  12.999   21.19  13.205  22.816  13.112   23.82  12.915
  28.449  10.371  32.201  10.019  34.462   8.617  37.113   8.074  38.536   7.865
  41.525   7.769   43.44   7.551   45.43   7.533  47.561   8.074  50.853   8.562
   51.42   8.826  54.911   9.731  60.489  10.062  65.121  12.734  66.094  13.045
  68.096  13.043   70.21    12.3   80.99  12.176
#Mann= 3 , 0 , 0
       0    .035       0       0    .035       0   80.99    .035       0
Bank Sta=0,80.99
XS Rating Curve= 0
Exp/Cntr=.3,.1

Type RM Length L Ch R = 1 ,367     ,48.63,48.63,48.63
XS GIS Cut Line= 2
      1615026.74      4854471.92 1615008.2743772 4854502.9560019
#Sta/Elev= 24
       0  12.774   6.592  12.879  16.813  12.838  22.699  12.643  23.399  12.624
    23.9  12.793  28.269  10.217  32.863  10.108  35.932    8.37  38.139   8.213
  39.903    7.52  41.873   7.631  44.053   7.596  46.571   8.099  49.988   8.405
  51.137   8.521   52.12   8.969  53.543   9.236  53.921   9.687  60.375  10.583
  61.996   10.96  65.653  12.738  66.892  13.067  81.545  13.176
#Mann= 3 , 0 , 0
       0    .035       0       0    .035       0  81.545    .035       0
Bank Sta=0,81.545
XS Rating Curve= 0
Exp/Cntr=.3,.1

Type RM Length L Ch R = 1 ,366     ,21.57,21.57,21.57
XS GIS Cut Line= 2
      1614984.75      4854446.39 1614962.8336055 4854485.1250196
#Sta/Elev= 27
       0  13.054    8.16  12.998  15.891   12.86   22.02  12.993   23.79  12.963
  29.314  10.025  34.138   9.796   35.62   8.463  36.734   8.282  39.202   7.742
  40.238   7.573   41.35   7.649  42.263   7.528  43.341   7.495  44.244   7.443
  45.334   7.536  46.468   8.074   47.42   8.289  50.163   8.432  51.287   8.778
  54.426   9.356      56  10.141  59.907  10.812  62.239  11.196  66.519  13.062
  73.459  13.143   88.58  13.111
#Mann= 3 , 0 , 0
       0    .035       0       0    .035       0   88.58    .035       0
Bank Sta=0,88.58
XS Rating Curve= 0
Exp/Cntr=.3,.1

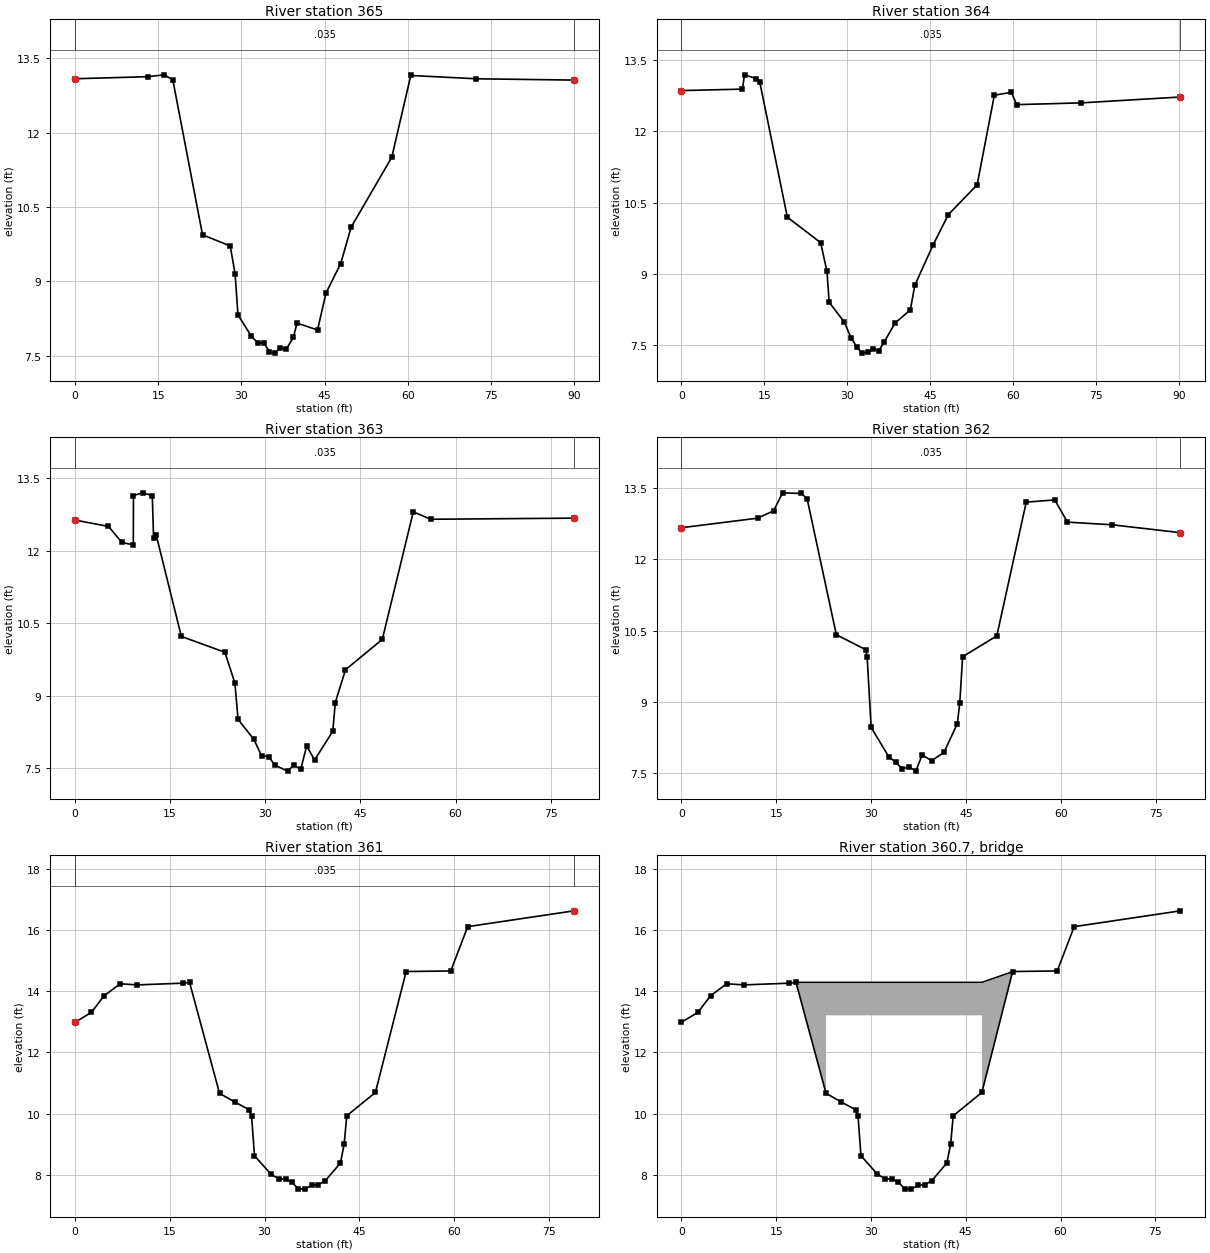
Type RM Length L Ch R = 1 ,365     ,49.7,49.7,49.7
XS GIS Cut Line= 2
      1614965.65      4854435.54 1614938.2188562 4854486.3963705
#Sta/Elev= 25
       0  13.091    13.1  13.132   16.07   13.17  17.629  13.068  22.979    9.94
  27.976   9.714   28.86   9.143  29.365   8.323  31.794   7.891  32.904   7.762
  34.079   7.751  35.027   7.582      36   7.551  36.951   7.655  38.062   7.629
  39.358    7.87  40.008   8.158  43.705   8.018  45.228   8.765  47.879   9.358
  49.765  10.095  57.079  11.504   60.51  13.157   72.34   13.09   89.92  13.064
#Mann= 3 , 0 , 0
       0    .035       0       0    .035       0   89.92    .035       0
Bank Sta=0,89.92
XS Rating Curve= 0
Exp/Cntr=.3,.1

Type RM Length L Ch R = 1 ,364     ,48.93,48.93,48.93
XS GIS Cut Line= 2
      1614922.33      4854411.45 1614891.9900247 4854466.8290976
#Sta/Elev= 28
       0  12.858  11.026  12.889  11.409   13.19  13.568  13.109  14.165  13.039
  19.157   10.19  25.177   9.655   26.33   9.047  26.723   8.399  29.476   7.978
   30.69   7.649   31.75   7.454  32.662   7.327  33.793   7.341  34.699   7.421
  35.676   7.373   36.71   7.568   38.63    7.96  41.407   8.237  42.221   8.757
  45.518   9.605  48.291  10.246  53.495  10.873  56.607   12.76  59.686  12.822
  60.645  12.562  72.315  12.599   90.28  12.723
#Mann= 3 , 0 , 0
       0    .035       0       0    .035       0   90.28    .035       0
Bank Sta=0,90.28
XS Rating Curve= 0
Exp/Cntr=.3,.1

Type RM Length L Ch R = 1 ,363     ,51.25,51.25,51.25
XS GIS Cut Line= 2
      1614879.02      4854387.01  1614853.356875 4854438.2856656
#Sta/Elev= 29
       0  12.635   5.283  12.504   7.392  12.172   9.194  12.121   9.218  13.143
  10.669  13.199  12.188  13.142  12.389  12.267  12.814   12.32  16.767  10.227
  23.635   9.899  25.215    9.26  25.708   8.511  28.209   8.094   29.42   7.757
  30.521   7.739  31.521   7.563  33.511   7.439  34.517   7.565  35.589   7.474
  36.526   7.959  37.777    7.67  40.647   8.264  41.041   8.859  42.648   9.537
  48.453  10.166  53.337  12.805  56.086  12.652  78.677  12.675
#Mann= 3 , 0 , 0
       0    .035       0       0    .035       0  78.677    .035       0
Bank Sta=0,78.677
XS Rating Curve= 0
Exp/Cntr=.3,.1

Type RM Length L Ch R = 1 ,362     ,48.44,48.44,48.44
XS GIS Cut Line= 2
      1614834.18      4854365.77 1614812.8437818 4854400.7515535
#Sta/Elev= 27
       0  12.668  12.026  12.869  14.562  13.022  15.985  13.403  18.955  13.389
  19.866  13.279  24.489  10.415  29.152  10.099  29.358   9.954  29.991   8.462
  32.758   7.849  33.862   7.728  34.923   7.591  35.985   7.632  37.049   7.542
  38.053   7.881  39.558   7.763  41.506   7.937   43.62   8.541  44.009   8.986
  44.453   9.952  49.858   10.39  54.515  13.207  59.015  13.254  61.031  12.786
   68.08   12.73  78.898  12.564
#Mann= 3 , 0 , 0
       0    .035       0       0    .035       0  78.898    .035       0
Bank Sta=0,78.898
XS Rating Curve= 0
Exp/Cntr=.3,.1

Type RM Length L Ch R = 1 ,361     ,8,8,8
XS GIS Cut Line= 2
      1614791.85      4854340.76 1614770.0944112 4854379.9820472
#Sta/Elev= 29
       0  12.984    2.59  13.305     4.6  13.847    7.14  14.241    9.85  14.205
   17.06  14.261   18.13  14.287   22.88  10.662   25.27  10.381   27.58  10.124
   27.95   9.918   28.41   8.624  31.027   8.017   32.23   7.872  33.391   7.853
  34.307   7.766  35.373   7.532  36.404   7.537  37.486   7.656  38.537   7.679
  39.624   7.808 42.0052   8.385  42.614   9.013 43.0083   9.927 47.5495   10.69
  52.415  14.642  59.475   14.66  62.158  16.108  78.981  16.625
#Mann= 3 , 0 , 0
       0    .035       0       0    .035       0  78.981    .035       0
Bank Sta=0,78.981
XS Rating Curve= 0
Exp/Cntr=.3,.1

Type RM Length L Ch R = 3 ,360.7   ,,,
BEGIN DESCRIPTION:
ponte di cerasomma
END DESCRIPTION:
Bridge Culvert--1,0,-1,-1, 0
Deck Dist Width WeirC Skew NumUp NumDn MinLoCord MaxHiCord MaxSubmerge Is_Ogee
.5,7,1.44,0, 6, 6, , , .95, 0, 0,0,,
 18.1301 22.8801 22.8801 47.5601 47.5601 52.4201
 14.2899 14.2899 14.2899 14.2899 14.2899 14.6398
 14.2899 10.6601   13.21   13.21 10.6899 14.6398
 18.1301 22.8801 22.8801 47.5601 47.5601 52.4201
 14.2899 14.2899 14.2899 14.2899 14.2899 14.6398
 14.2899 10.6601   13.21   13.21 10.6899 14.6398
BR Coef=-1 , 0 , 0 ,1.25, 0 ,,,.8,-1,2,0,
WSPro=,,,, 1 ,,,, 0 ,,,, 0 ,,,,-1 ,-1 ,-1 , 0 , 0 , 0 , 0 , 0
BC Design=,, 0 ,, 0 ,,,,,,
BC HTab Sub Flow Pts= 40

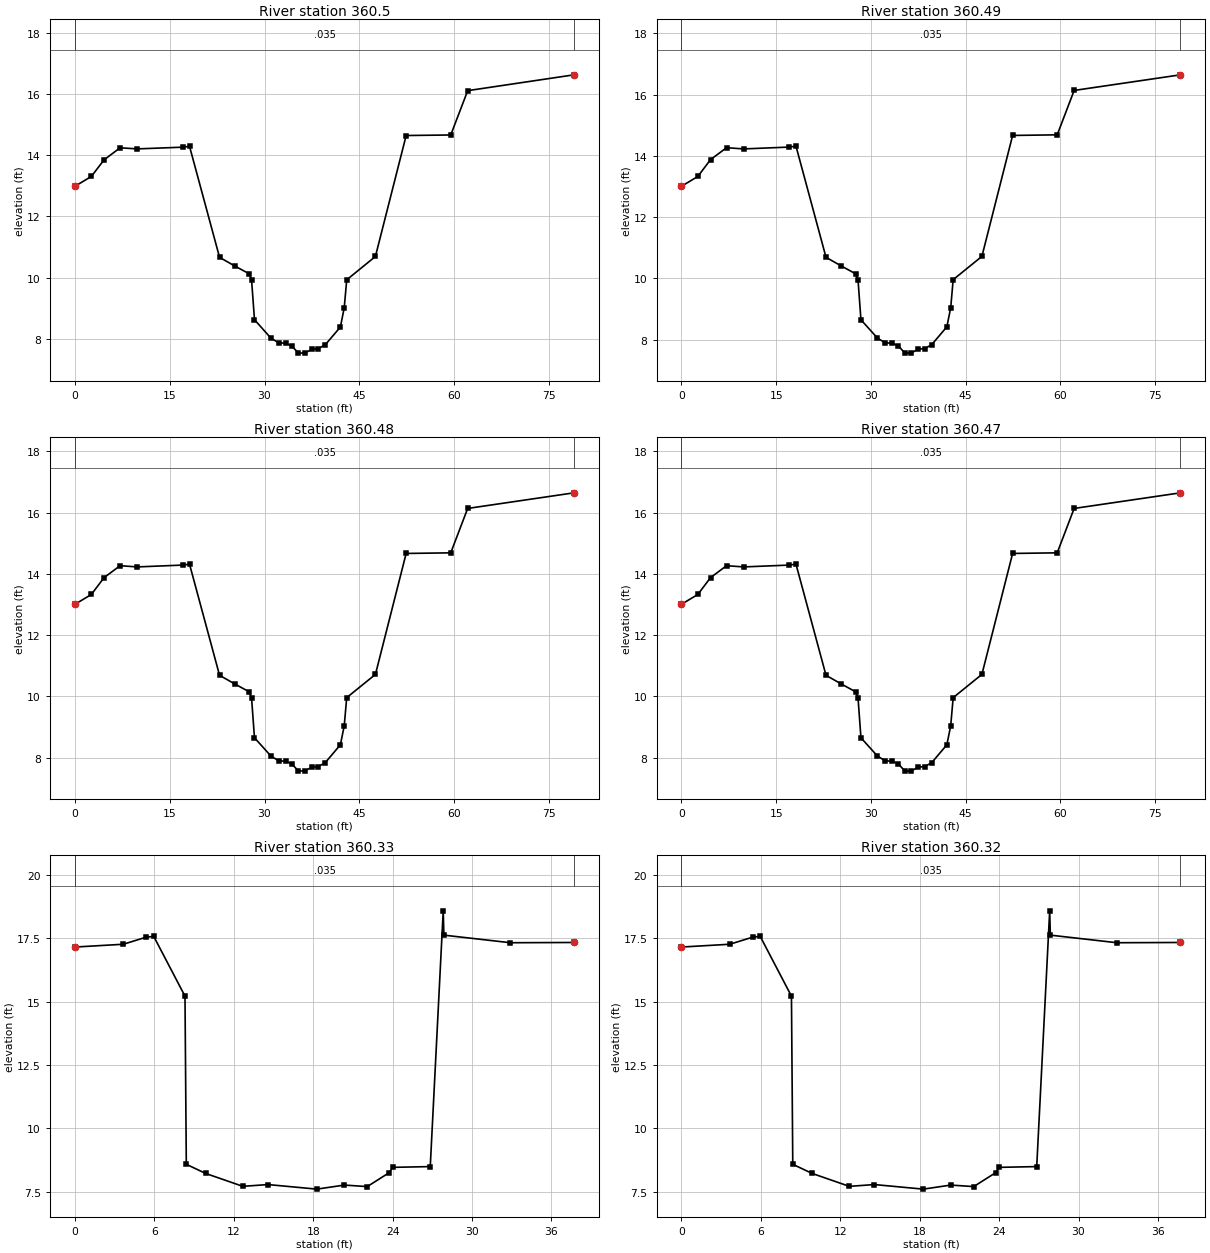
Type RM Length L Ch R = 1 ,360.5   ,85.7,85.7,85.7
XS GIS Cut Line= 2
      1614791.85      4854340.76 1614761.8144117 4854394.9020475
#Sta/Elev= 29
       0  12.984    2.59  13.305     4.6  13.847    7.14  14.241    9.85  14.205
   17.06  14.261   18.13  14.287   22.88  10.662   25.27  10.381   27.58  10.124
   27.95   9.918   28.41   8.624  31.027   8.017   32.23   7.872  33.391   7.853
  34.307   7.766  35.373   7.532  36.404   7.537  37.486   7.656  38.537   7.679
  39.624   7.808 42.0052   8.385  42.614   9.013 43.0083   9.927 47.5495   10.69
  52.415  14.642  59.475   14.66  62.158  16.108  78.981  16.625
#Mann= 3 , 0 , 0
       0    .035       0       0    .035       0  78.981    .035       0
Bank Sta=0,78.981
XS Rating Curve= 0
Exp/Cntr=.3,.1

Type RM Length L Ch R = 1 ,360.49  ,85.7,85.7,85.7
BEGIN DESCRIPTION:
come 360.5 z=z+0.03
END DESCRIPTION:
#Sta/Elev= 29
       0   13.01  2.5899   13.33     4.6   13.88  7.1399   14.27  9.8499   14.23
   17.06   14.29 18.1301   14.32 22.8801   10.69 25.2701   10.41 27.5801   10.15
 27.9499    9.95 28.4101    8.65 31.0299    8.05 32.2299     7.9    33.4    7.88
 34.3101     7.8   35.38    7.56 36.4099    7.57 37.4901    7.69 38.5401    7.71
 39.6301    7.84   42.01    8.42 42.6199    9.04   43.01    9.96 47.5601   10.72
 52.4201   14.67 59.4799   14.69   62.16   16.14 78.9901   16.65
#Mann= 3 , 0 , 0
       0    .035       0       0    .035       0 78.9901    .035       0
Bank Sta=0,78.9901
XS Rating Curve= 0
Exp/Cntr=.3,.1

Type RM Length L Ch R = 1 ,360.48  ,85.7,85.7,85.7
BEGIN DESCRIPTION:
come 360.49 z=z+0.03
END DESCRIPTION:
#Sta/Elev= 29
       0   13.01  2.5899   13.33     4.6   13.88  7.1399   14.27  9.8499   14.23
   17.06   14.29 18.1301   14.32 22.8801   10.69 25.2701   10.41 27.5801   10.15
 27.9499    9.95 28.4101    8.65 31.0299    8.05 32.2299     7.9    33.4    7.88
 34.3101     7.8   35.38    7.56 36.4099    7.57 37.4901    7.69 38.5401    7.71
 39.6301    7.84   42.01    8.42 42.6199    9.04   43.01    9.96 47.5601   10.72
 52.4201   14.67 59.4799   14.69   62.16   16.14 78.9901   16.65
#Mann= 3 , 0 , 0
       0    .035       0       0    .035       0 78.9901    .035       0
Bank Sta=0,78.9901
XS Rating Curve= 0
Exp/Cntr=.3,.1

Type RM Length L Ch R = 1 ,360.47  ,85.7,85.7,85.7
BEGIN DESCRIPTION:
come 360.48 z=z+0.03
END DESCRIPTION:
#Sta/Elev= 29
       0   13.01  2.5899   13.33     4.6   13.88  7.1399   14.27  9.8499   14.23
   17.06   14.29 18.1301   14.32 22.8801   10.69 25.2701   10.41 27.5801   10.15
 27.9499    9.95 28.4101    8.65 31.0299    8.05 32.2299     7.9    33.4    7.88
 34.3101     7.8   35.38    7.56 36.4099    7.57 37.4901    7.69 38.5401    7.71
 39.6301    7.84   42.01    8.42 42.6199    9.04   43.01    9.96 47.5601   10.72
 52.4201   14.67 59.4799   14.69   62.16   16.14 78.9901   16.65
#Mann= 3 , 0 , 0
       0    .035       0       0    .035       0 78.9901    .035       0
Bank Sta=0,78.9901
XS Rating Curve= 0
Exp/Cntr=.3,.1

Type RM Length L Ch R = 1 ,360.33  ,85.7,85.7,85.7
BEGIN DESCRIPTION:
come 360.32 z=z-0.03
END DESCRIPTION:
#Sta/Elev= 19
       0   17.16    3.65   17.27    5.38   17.55    5.95   17.58  8.3101   15.22
    8.41    8.58    9.87    8.22   12.68    7.71 14.5801    7.78   18.27     7.6
   20.35    7.76   22.08     7.7   23.74    8.25   24.01    8.46 26.8401    8.49
   27.82   18.59   27.87   17.63 32.9001   17.33 37.7001   17.34
#Mann= 3 , 0 , 0
       0    .035       0       0    .035       0 37.7001    .035       0
Bank Sta=0,37.7001
XS Rating Curve= 0
Exp/Cntr=.3,.1

Type RM Length L Ch R = 1 ,360.32  ,85.7,85.7,85.7
BEGIN DESCRIPTION:
come 360.31 z=z-0.03
END DESCRIPTION:
#Sta/Elev= 19
       0   17.16    3.65   17.27    5.38   17.55    5.95   17.58  8.3101   15.22
    8.41    8.58    9.87    8.22   12.68    7.71 14.5801    7.78   18.27     7.6
   20.35    7.76   22.08     7.7   23.74    8.25   24.01    8.46 26.8401    8.49
   27.82   18.59   27.87   17.63 32.9001   17.33 37.7001   17.34
#Mann= 3 , 0 , 0
       0    .035       0       0    .035       0 37.7001    .035       0
Bank Sta=0,37.7001
XS Rating Curve= 0
Exp/Cntr=.3,.1

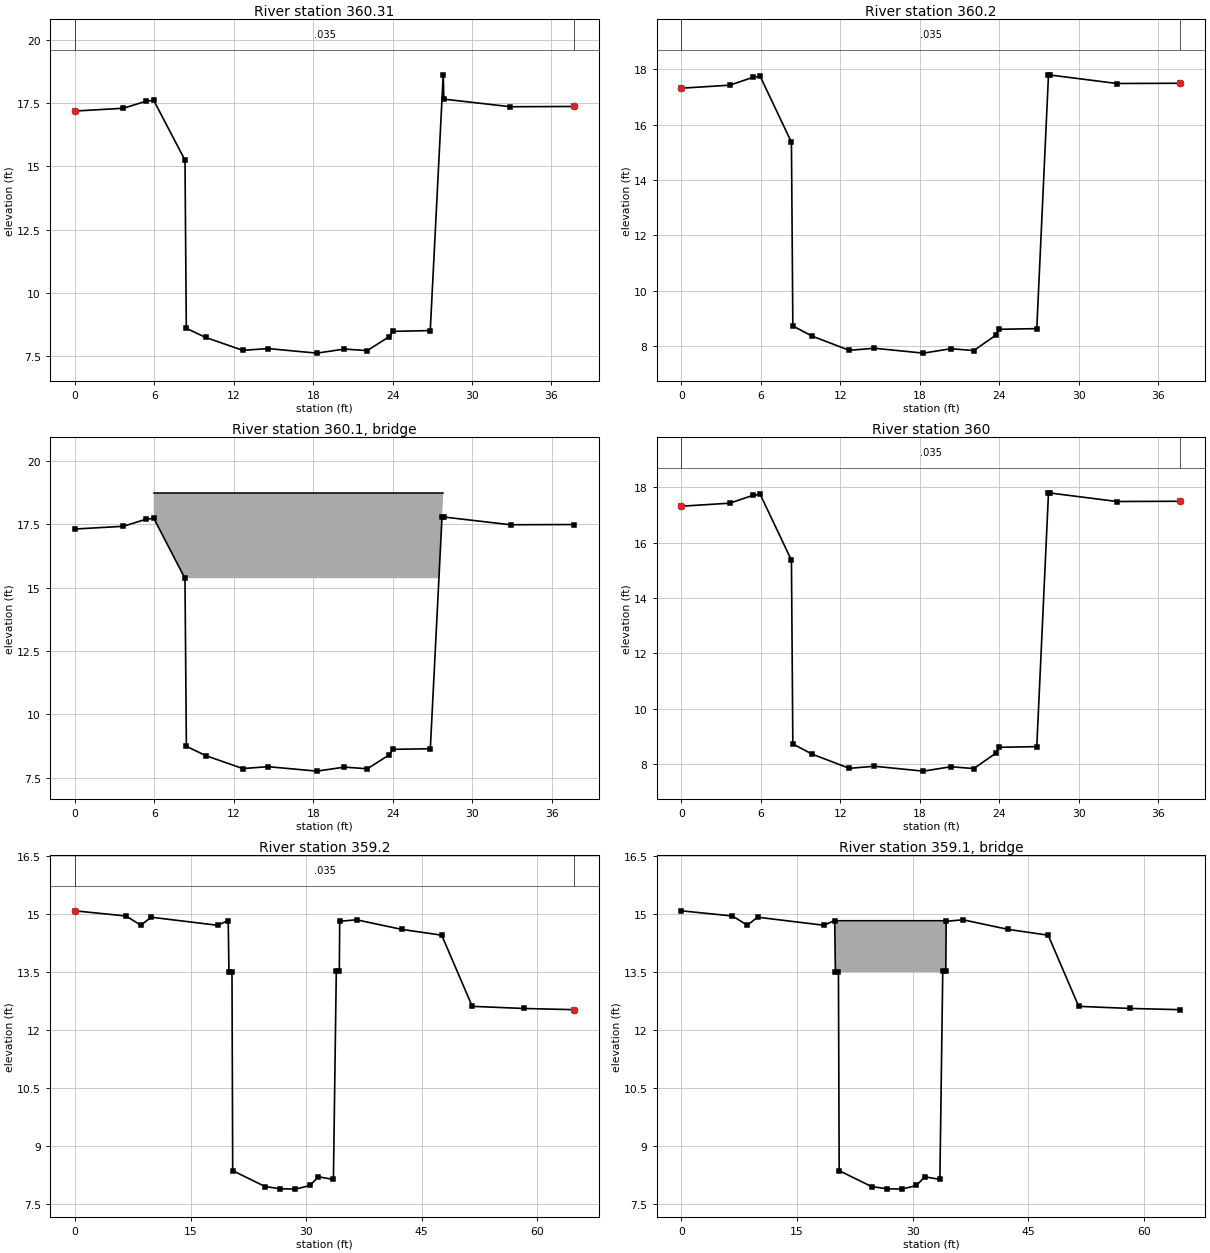
Type RM Length L Ch R = 1 ,360.31  ,85.7,85.7,85.7
BEGIN DESCRIPTION:
come 360.2 z=z-0.03
END DESCRIPTION:
#Sta/Elev= 19
       0   17.19    3.65    17.3    5.38   17.58    5.95   17.61  8.3101   15.25
    8.41    8.61    9.87    8.25   12.68    7.74 14.5801    7.81   18.27    7.63
   20.35    7.79   22.08    7.73   23.74    8.28   24.01    8.49 26.8401    8.52
   27.82   18.62   27.87   17.66 32.9001   17.36 37.7001   17.37
#Mann= 3 , 0 , 0
       0    .035       0       0    .035       0 37.7001    .035       0
Bank Sta=0,37.7001
XS Rating Curve= 0
Exp/Cntr=.3,.1

Type RM Length L Ch R = 1 ,360.2   ,8,8,8
XS GIS Cut Line= 2
      1614318.81      4854001.33  1614281.665078 4854004.8095243
#Sta/Elev= 19
       0  17.311   3.649  17.419   5.382    17.7   5.953  17.733   8.308  15.361
   8.414   8.735   9.874   8.368  12.677   7.856  14.578   7.931  18.274   7.755
  20.351   7.913  22.084   7.848  23.742     8.4  24.011   8.615  26.841   8.638
  27.726  17.793  27.868  17.785    32.9   17.48  37.695  17.489
#Mann= 3 , 0 , 0
       0    .035       0       0    .035       0  37.695    .035       0
Bank Sta=0,37.695
XS Rating Curve= 0
Exp/Cntr=.3,.1

Type RM Length L Ch R = 3 ,360.1   ,,,
BEGIN DESCRIPTION:
FFSS Lu-Viareggio
END DESCRIPTION:
Bridge Culvert--1,0,-1,-1, 0
Deck Dist Width WeirC Skew NumUp NumDn MinLoCord MaxHiCord MaxSubmerge Is_Ogee
.5,7,1.44,0, 6, 6, , , .95, 0, 0,0,,
    5.95    5.95  8.3101 26.8401 27.4899   27.82
   18.74   18.74   18.74   18.74   18.74   18.74
   18.74 17.7299 15.3701 15.3701 15.3701   18.74
    5.95    5.95  8.3101 26.8401 27.4899   27.82
   18.74   18.74   18.74   18.74   18.74   18.74
   18.74 17.7299 15.3701 15.3701 15.3701   18.74
BR Coef=-1 , 0 , 0 ,1.25, 0 ,,,.8,-1,2,0,
WSPro=,,,, 1 ,,,, 0 ,,,, 0 ,,,,-1 ,-1 ,-1 , 0 , 0 , 0 , 0 , 0
BC Design=,, 0 ,, 0 ,,,,,,
BC HTab Sub Flow Pts= 40

Type RM Length L Ch R = 1 ,360     ,112.27,112.27,112.27
XS GIS Cut Line= 2
      1614318.81      4854001.33  1614281.665078 4854004.8095243
#Sta/Elev= 19
       0  17.311   3.649  17.419   5.382    17.7   5.953  17.733   8.308  15.361
   8.414   8.735   9.874   8.368  12.677   7.856  14.578   7.931  18.274   7.755
  20.351   7.913  22.084   7.848  23.742     8.4  24.011   8.615  26.841   8.638
  27.726  17.793  27.868  17.785    32.9   17.48  37.695  17.489
#Mann= 3 , 0 , 0
       0    .035       0       0    .035       0  37.695    .035       0
Bank Sta=0,37.695
XS Rating Curve= 0
Exp/Cntr=.3,.1

Type RM Length L Ch R = 1 ,359.2   ,8,8,8
XS GIS Cut Line= 3
      1614239.18      4853905.41      1614194.34      4853951.98
 1614194.3399312 4853951.9800715
#Sta/Elev= 24
       0  15.085    6.62  14.951   8.553  14.712   9.879   14.92  18.497  14.711
  19.886  14.834  19.979  13.502  20.374  13.503  20.467   8.358  24.667   7.947
  26.634    7.89  28.598    7.88  30.501   7.974  31.575   8.199  33.538   8.132
  33.912  13.522  34.304  13.519  34.354  14.814  36.534  14.853  42.382  14.605
  47.593  14.454  51.551  12.612  58.251  12.557   64.76  12.526
#Mann= 3 , 0 , 0
       0    .035       0       0    .035       0   64.76    .035       0
Bank Sta=0,64.76
XS Rating Curve= 0
Exp/Cntr=.3,.1

Type RM Length L Ch R = 3 ,359.1   ,,,
BEGIN DESCRIPTION:
ponte dismesso
END DESCRIPTION:
Bridge Culvert--1,0,-1,-1, 0
Deck Dist Width WeirC Skew NumUp NumDn MinLoCord MaxHiCord MaxSubmerge Is_Ogee
.5,7,1.44,0, 6, 6, , , .95, 0, 0,0,,
   19.89 19.9799 20.3701 33.9099 34.3001   34.35
   14.83   14.83   14.83   14.83   14.83 14.8099
   14.83 13.4999 13.4999 13.4999   13.52 14.8099
   19.89 19.9799 20.3701 33.9099 34.3001   34.35
   14.83   14.83   14.83   14.83   14.83 14.8099
   14.83 13.4999 13.4999 13.4999   13.52 14.8099
BR Coef=-1 , 0 , 0 ,1.25, 0 ,,,.8,-1,2,0,
WSPro=,,,, 1 ,,,, 0 ,,,, 0 ,,,,-1 ,-1 ,-1 , 0 , 0 , 0 , 0 , 0
BC Design=,, 0 ,, 0 ,,,,,,
BC HTab Sub Flow Pts= 40

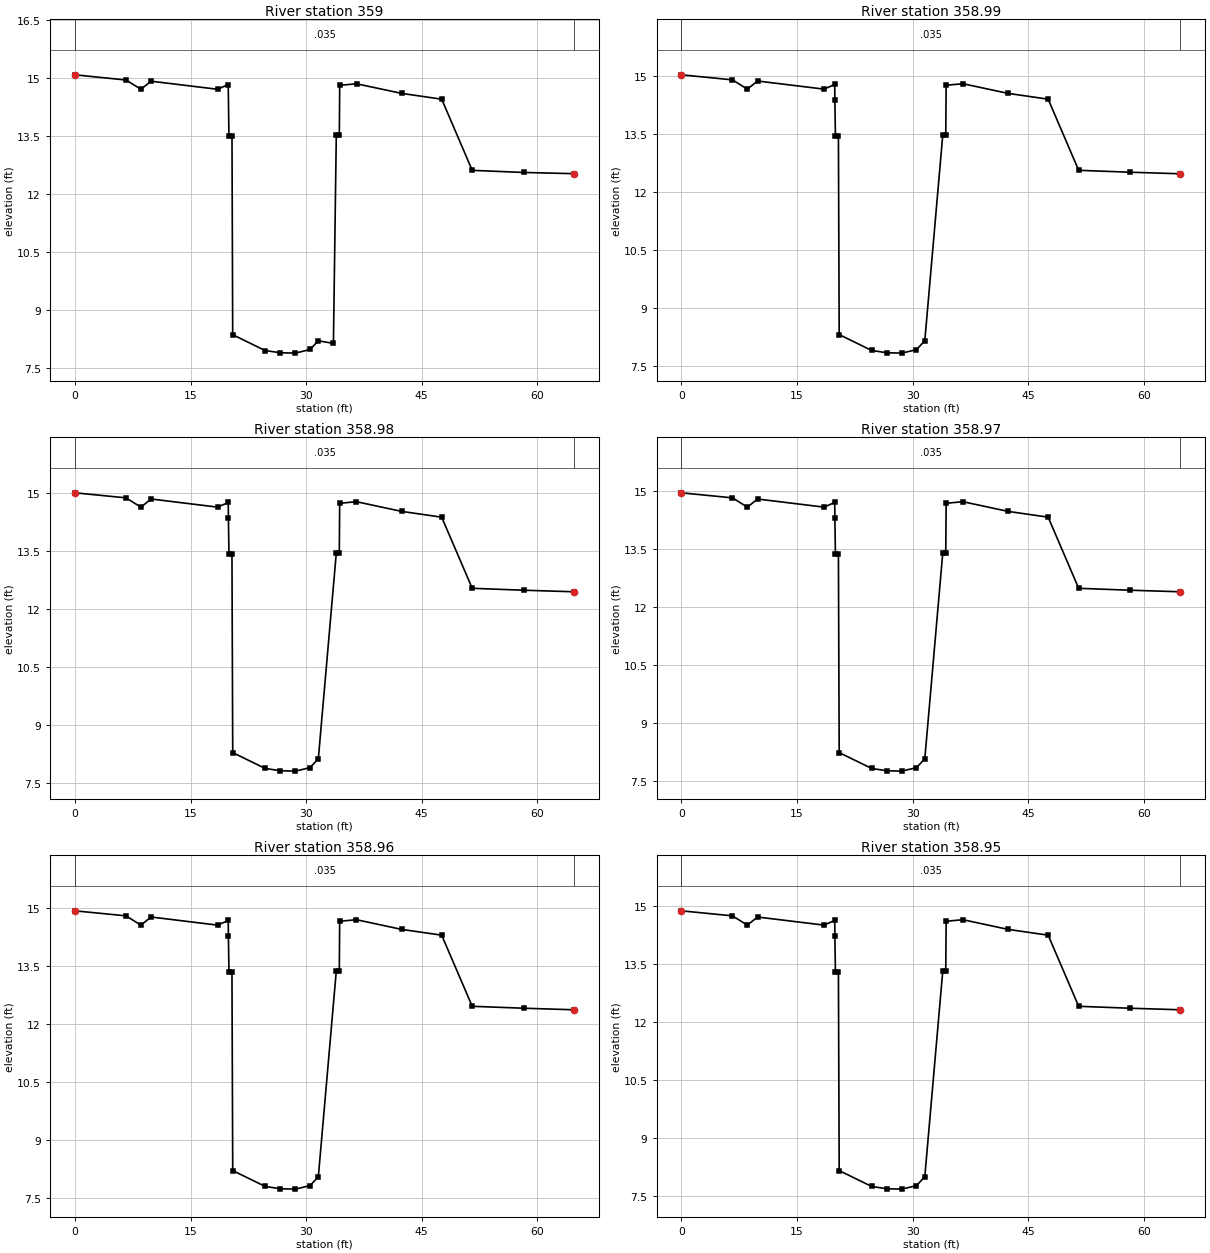
Type RM Length L Ch R = 1 ,359     ,113,113,113
XS GIS Cut Line= 3
      1614239.18      4853905.41      1614194.34      4853951.98
 1614194.3399312 4853951.9800715
#Sta/Elev= 24
       0  15.085    6.62  14.951   8.553  14.712   9.879   14.92  18.497  14.711
  19.886  14.834  19.979  13.502  20.374  13.503  20.467   8.358  24.667   7.947
  26.634    7.89  28.598    7.88  30.501   7.974  31.575   8.199  33.538   8.132
  33.912  13.522  34.304  13.519  34.354  14.814  36.534  14.853  42.382  14.605
  47.593  14.454  51.551  12.612  58.251  12.557   64.76  12.526
#Mann= 3 , 0 , 0
       0    .035       0       0    .035       0   64.76    .035       0
Bank Sta=0,64.76
XS Rating Curve= 0
Exp/Cntr=.3,.1

Type RM Length L Ch R = 1 ,358.99  ,113,113,113
BEGIN DESCRIPTION:
come 359 con z=z-0.04
END DESCRIPTION:
#Sta/Elev= 24
       0   15.04    6.62   14.91  8.5499   14.67  9.8801   14.88 18.5001   14.67
   19.89   14.79 19.9101   14.39 19.9799   13.46 20.3701   13.46 20.4701    8.32
 24.6699    7.91 26.6301    7.85    28.6    7.84 30.5001    7.93   31.58    8.16
 33.9099   13.48 34.3001   13.48   34.35   14.77   36.53   14.81   42.38   14.56
 47.5899   14.41 51.5499   12.57   58.25   12.52 64.7599   12.48
#Mann= 3 , 0 , 0
       0    .035       0       0    .035       0 64.7599    .035       0
Bank Sta=0,64.7599
XS Rating Curve= 0
Exp/Cntr=.3,.1

Type RM Length L Ch R = 1 ,358.98  ,113,113,113
BEGIN DESCRIPTION:
come 358.99 con z=z-0.04
END DESCRIPTION:
#Sta/Elev= 24
       0      15    6.62   14.87  8.5499   14.63  9.8801   14.84 18.5001   14.63
   19.89   14.75 19.9101   14.35 19.9799   13.42 20.3701   13.42 20.4701    8.28
 24.6699    7.87 26.6301    7.81    28.6     7.8 30.5001    7.89   31.58    8.12
 33.9099   13.44 34.3001   13.44   34.35   14.73   36.53   14.77   42.38   14.52
 47.5899   14.37 51.5499   12.53   58.25   12.48 64.7599   12.44
#Mann= 3 , 0 , 0
       0    .035       0       0    .035       0 64.7599    .035       0
Bank Sta=0,64.7599
XS Rating Curve= 0
Exp/Cntr=.3,.1

Type RM Length L Ch R = 1 ,358.97  ,113,113,113
BEGIN DESCRIPTION:
come 358.98 con z=z-0.04
END DESCRIPTION:
#Sta/Elev= 24
       0   14.96    6.62   14.83  8.5499   14.59  9.8801    14.8 18.5001   14.59
   19.89   14.71 19.9101   14.31 19.9799   13.38 20.3701   13.38 20.4701    8.24
 24.6699    7.83 26.6301    7.77    28.6    7.76 30.5001    7.85   31.58    8.08
 33.9099    13.4 34.3001    13.4   34.35   14.69   36.53   14.73   42.38   14.48
 47.5899   14.33 51.5499   12.49   58.25   12.44 64.7599    12.4
#Mann= 3 , 0 , 0
       0    .035       0       0    .035       0 64.7599    .035       0
Bank Sta=0,64.7599
XS Rating Curve= 0
Exp/Cntr=.3,.1

Type RM Length L Ch R = 1 ,358.96  ,113,113,113
BEGIN DESCRIPTION:
come 358.97 con z=z-0.04
END DESCRIPTION:
#Sta/Elev= 24
       0   14.92    6.62   14.79  8.5499   14.55  9.8801   14.76 18.5001   14.55
   19.89   14.67 19.9101   14.27 19.9799   13.34 20.3701   13.34 20.4701     8.2
 24.6699    7.79 26.6301    7.73    28.6    7.72 30.5001    7.81   31.58    8.04
 33.9099   13.36 34.3001   13.36   34.35   14.65   36.53   14.69   42.38   14.44
 47.5899   14.29 51.5499   12.45   58.25    12.4 64.7599   12.36
#Mann= 3 , 0 , 0
       0    .035       0       0    .035       0 64.7599    .035       0
Bank Sta=0,64.7599
XS Rating Curve= 0
Exp/Cntr=.3,.1

Type RM Length L Ch R = 1 ,358.95  ,113,113,113
BEGIN DESCRIPTION:
come 358.96 con z=z-0.02
END DESCRIPTION:
#Sta/Elev= 24
       0   14.88    6.62   14.75  8.5499   14.51  9.8801   14.72 18.5001   14.51
   19.89   14.63 19.9101   14.23 19.9799    13.3 20.3701    13.3 20.4701    8.16
 24.6699    7.75 26.6301    7.69    28.6    7.68 30.5001    7.77   31.58       8
 33.9099   13.32 34.3001   13.32   34.35   14.61   36.53   14.65   42.38    14.4
 47.5899   14.25 51.5499   12.41   58.25   12.36 64.7599   12.32
#Mann= 3 , 0 , 0
       0    .035       0       0    .035       0 64.7599    .035       0
Bank Sta=0,64.7599
XS Rating Curve= 0
Exp/Cntr=.3,.1

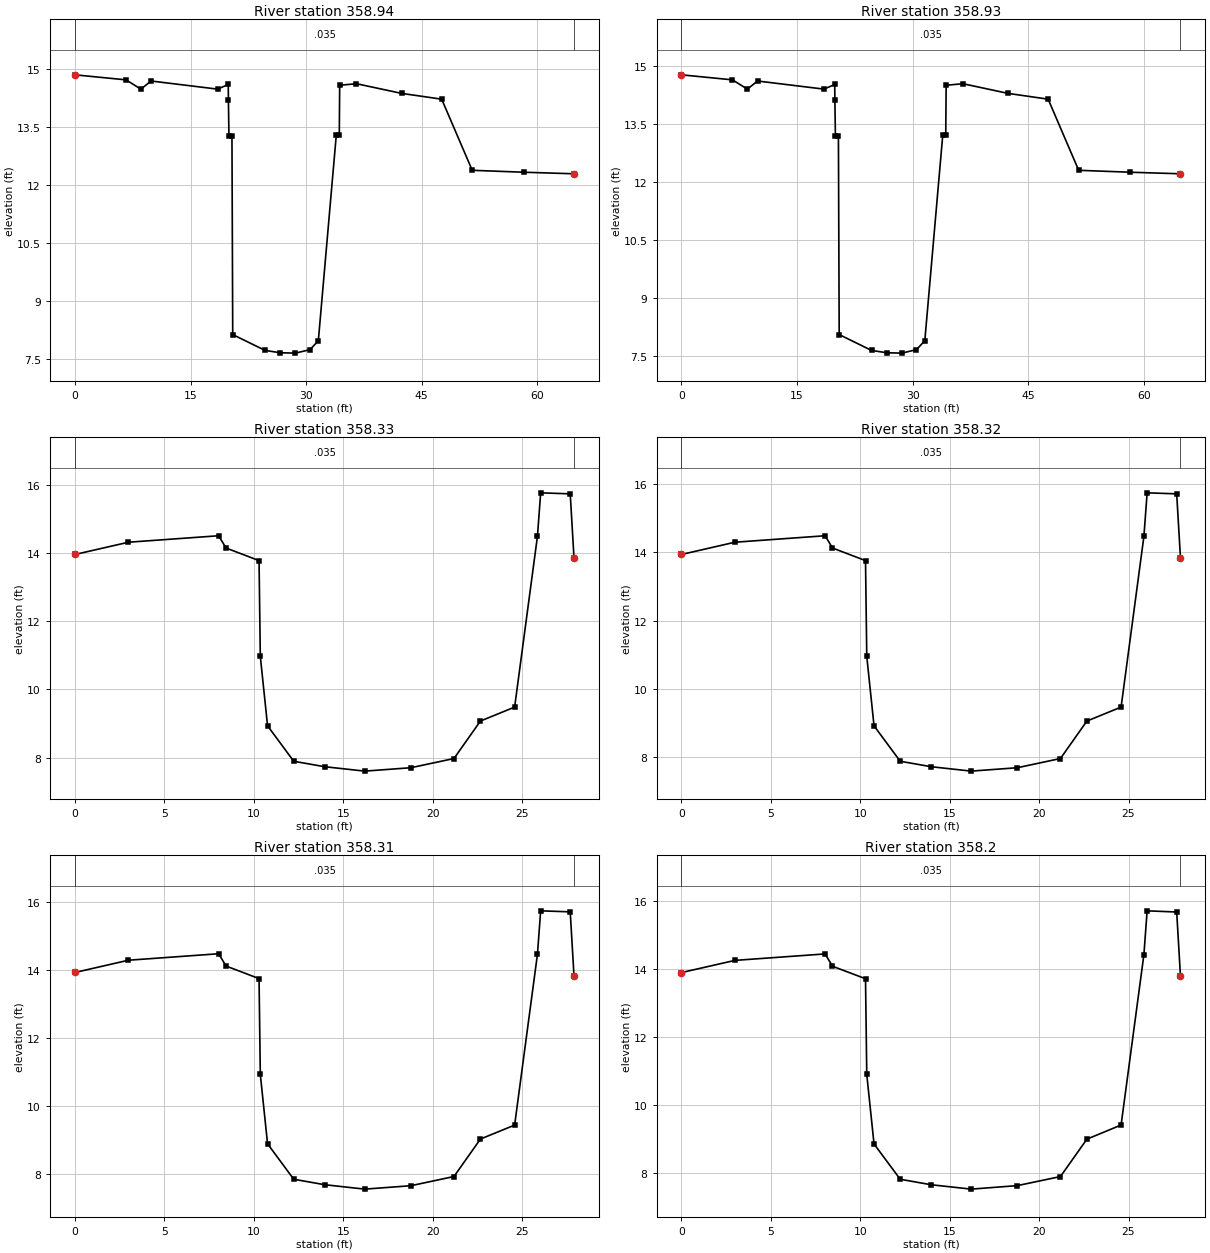
Type RM Length L Ch R = 1 ,358.94  ,113,113,113
BEGIN DESCRIPTION:
come 358.95 con z=z-0.02
END DESCRIPTION:
#Sta/Elev= 24
       0   14.84    6.62   14.71  8.5499   14.47  9.8801   14.68 18.5001   14.47
   19.89   14.59 19.9101   14.19 19.9799   13.26 20.3701   13.26 20.4701    8.12
 24.6699    7.71 26.6301    7.65    28.6    7.64 30.5001    7.73   31.58    7.96
 33.9099   13.28 34.3001   13.28   34.35   14.57   36.53   14.61   42.38   14.36
 47.5899   14.21 51.5499   12.37   58.25   12.32 64.7599   12.28
#Mann= 3 , 0 , 0
       0    .035       0       0    .035       0 64.7599    .035       0
Bank Sta=0,64.7599
XS Rating Curve= 0
Exp/Cntr=.3,.1

Type RM Length L Ch R = 1 ,358.93  ,113,113,113
BEGIN DESCRIPTION:
come 358.94 con z=z-0.02
END DESCRIPTION:
#Sta/Elev= 24
       0   14.78    6.62   14.65  8.5499   14.41  9.8801   14.62 18.5001   14.41
   19.89   14.53 19.9101   14.13 19.9799    13.2 20.3701    13.2 20.4701    8.06
 24.6699    7.65 26.6301    7.59    28.6    7.58 30.5001    7.67   31.58     7.9
 33.9099   13.22 34.3001   13.22   34.35   14.51   36.53   14.55   42.38    14.3
 47.5899   14.15 51.5499   12.31   58.25   12.26 64.7599   12.22
#Mann= 3 , 0 , 0
       0    .035       0       0    .035       0 64.7599    .035       0
Bank Sta=0,64.7599
XS Rating Curve= 0
Exp/Cntr=.3,.1

Type RM Length L Ch R = 1 ,358.33  ,113,113,113
#Sta/Elev= 18
       0   13.96   2.988   14.32   8.034   14.51   8.446   14.15  10.293   13.78
  10.363   10.97  10.769    8.93  12.233    7.89  13.957    7.73  16.203     7.6
  18.783     7.7  21.194    7.97  22.673    9.07  24.586    9.48  25.861   14.49
  26.042   15.77  27.695   15.74  27.906   13.86
#Mann= 3 , 0 , 0
       0    .035       0       0    .035       0  27.906    .035       0
Bank Sta=0,27.906
XS Rating Curve= 0
Exp/Cntr=.3,.1

Type RM Length L Ch R = 1 ,358.32  ,113,113,113
#Sta/Elev= 18
       0   13.94   2.988    14.3   8.034   14.49   8.446   14.13  10.293   13.76
  10.363   10.95  10.769    8.91  12.233    7.87  13.957    7.71  16.203    7.58
  18.783    7.68  21.194    7.95  22.673    9.05  24.586    9.46  25.861   14.47
  26.042   15.75  27.695   15.72  27.906   13.84
#Mann= 3 , 0 , 0
       0    .035       0       0    .035       0  27.906    .035       0
Bank Sta=0,27.906
XS Rating Curve= 0
Exp/Cntr=.3,.1

Type RM Length L Ch R = 1 ,358.31  ,113,113,113
#Sta/Elev= 18
       0   13.92   2.988   14.28   8.034   14.47   8.446   14.11  10.293   13.74
  10.363   10.93  10.769    8.89  12.233    7.85  13.957    7.69  16.203    7.56
  18.783    7.66  21.194    7.93  22.673    9.03  24.586    9.44  25.861   14.45
  26.042   15.73  27.695    15.7  27.906   13.82
#Mann= 3 , 0 , 0
       0    .035       0       0    .035       0  27.906    .035       0
Bank Sta=0,27.906
XS Rating Curve= 0
Exp/Cntr=.3,.1

Type RM Length L Ch R = 1 ,358.2   ,8,8,8
XS GIS Cut Line= 2
       1613798.7      4852768.51  1613772.023778   4852775.35903
#Sta/Elev= 18
       0    13.9   2.988  14.258   8.034  14.448   8.446  14.086  10.293  13.719
  10.363  10.907  10.769   8.866  12.233   7.829  13.957   7.668  16.203   7.539
  18.783   7.642  21.194   7.908  22.673   9.007  24.586   9.422  25.861  14.426
  26.042  15.714  27.695  15.679  27.906  13.796
#Mann= 3 , 0 , 0
       0    .035       0       0    .035       0  27.906    .035       0
Bank Sta=0,27.906
XS Rating Curve= 0
Exp/Cntr=.3,.1