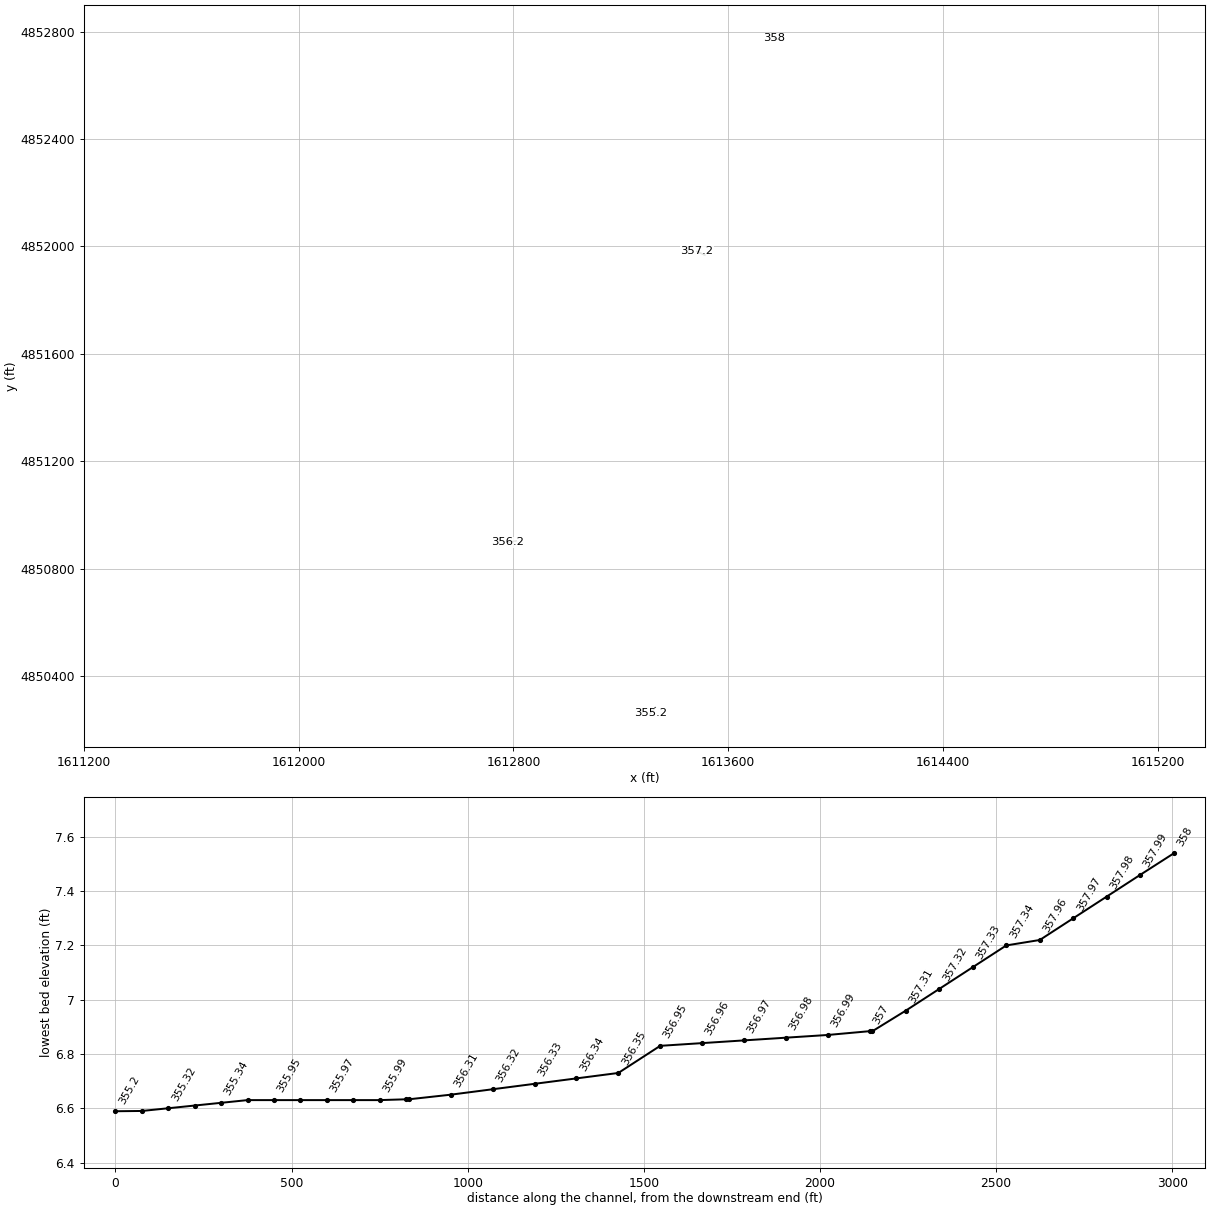
HEC-RAS study ozz_def.prj: ozzeri

--- ozz_def.g02 (geometry) --- (continued)

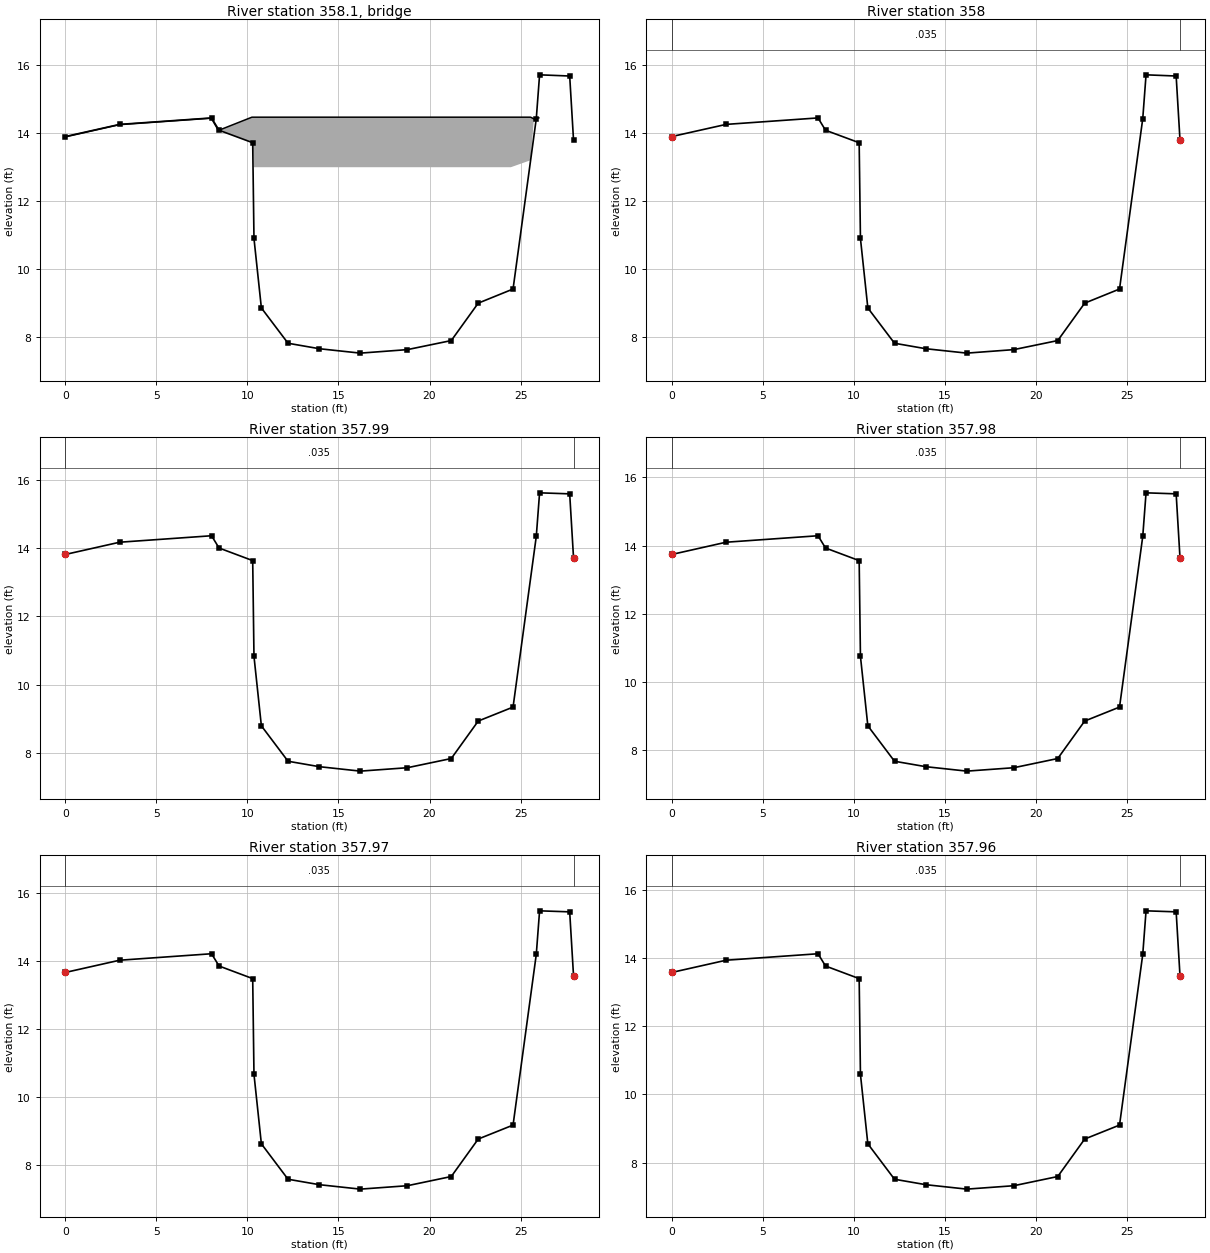
Type RM Length L Ch R = 3 ,358.1   ,,,
BEGIN DESCRIPTION:
Ponte di Ripafratta
END DESCRIPTION:
Bridge Culvert--1,0,-1,-1, 0
Deck Dist Width WeirC Skew NumUp NumDn MinLoCord MaxHiCord MaxSubmerge Is_Ogee
.5,7,1.44,0, 17, 17, , , .95, 0, 0,0,,
       0    2.98    8.02    8.41   10.25   10.29   10.67   12.13   13.84   16.09
   18.67   21.08   22.55   24.46   25.55   25.73      26
   13.89   14.25   14.44   14.08   14.47   14.47   14.47   14.47   14.47   14.47
   14.47   14.47   14.47   14.47   14.47   14.42   14.45
   13.89   14.25   14.44   14.08      13      13      13      13      13      13
      13      13      13      13    13.2   14.42   14.45
       0    2.98    8.02    8.41   10.25   10.29   10.67   12.13   13.84   16.09
   18.67   21.08   22.55   24.46   25.55   25.73      26
   13.89   14.25   14.44   14.08   14.47   14.47   14.47   14.47   14.47   14.47
   14.47   14.47   14.47   14.47   14.47   14.42   14.45
   13.89   14.25   14.44   14.08      13      13      13      13      13      13
      13      13      13      13    13.2   14.42   14.45
BR Coef=-1 , 0 , 0 ,1.25, 0 ,,,.8,-1,2,0,
WSPro=,,,, 1 ,,,, 0 ,,,, 0 ,,,,-1 ,-1 ,-1 , 0 , 0 , 0 , 0 , 0
BC Design=,, 0 ,, 0 ,,,,,,
BC HTab Sub Flow Pts= 40

Type RM Length L Ch R = 1 ,358     ,95,95,95
XS GIS Cut Line= 2
       1613798.7      4852768.51  1613772.023778   4852775.35903
#Sta/Elev= 18
       0    13.9   2.988  14.258   8.034  14.448   8.446  14.086  10.293  13.719
  10.363  10.907  10.769   8.866  12.233   7.829  13.957   7.668  16.203   7.539
  18.783   7.642  21.194   7.908  22.673   9.007  24.586   9.422  25.861  14.426
  26.042  15.714  27.695  15.679  27.906  13.796
#Mann= 3 , 0 , 0
       0    .035       0       0    .035       0  27.906    .035       0
Bank Sta=0,27.906
XS Rating Curve= 0
Exp/Cntr=.3,.1

Type RM Length L Ch R = 1 ,357.99  ,95,95,95
#Sta/Elev= 18
       0   13.82   2.988   14.18   8.034   14.37   8.446   14.01  10.293   13.64
  10.363   10.83  10.769    8.79  12.233    7.75  13.957    7.59  16.203    7.46
  18.783    7.56  21.194    7.83  22.673    8.93  24.586    9.34  25.861   14.35
  26.042   15.63  27.695    15.6  27.906   13.72
#Mann= 3 , 0 , 0
       0    .035       0       0    .035       0  27.906    .035       0
Bank Sta=0,27.906
XS Rating Curve= 0
Exp/Cntr=.3,.1

Type RM Length L Ch R = 1 ,357.98  ,95,95,95
#Sta/Elev= 18
       0   13.74   2.988    14.1   8.034   14.29   8.446   13.93  10.293   13.56
  10.363   10.75  10.769    8.71  12.233    7.67  13.957    7.51  16.203    7.38
  18.783    7.48  21.194    7.75  22.673    8.85  24.586    9.26  25.861   14.27
  26.042   15.55  27.695   15.52  27.906   13.64
#Mann= 3 , 0 , 0
       0    .035       0       0    .035       0  27.906    .035       0
Bank Sta=0,27.906
XS Rating Curve= 0
Exp/Cntr=.3,.1

Type RM Length L Ch R = 1 ,357.97  ,95,95,95
#Sta/Elev= 18
       0   13.66   2.988   14.02   8.034   14.21   8.446   13.85  10.293   13.48
  10.363   10.67  10.769    8.63  12.233    7.59  13.957    7.43  16.203     7.3
  18.783     7.4  21.194    7.67  22.673    8.77  24.586    9.18  25.861   14.19
  26.042   15.47  27.695   15.44  27.906   13.56
#Mann= 3 , 0 , 0
       0    .035       0       0    .035       0  27.906    .035       0
Bank Sta=0,27.906
XS Rating Curve= 0
Exp/Cntr=.3,.1

Type RM Length L Ch R = 1 ,357.96  ,95,95,95
#Sta/Elev= 18
       0   13.58   2.988   13.94   8.034   14.13   8.446   13.77  10.293    13.4
  10.363   10.59  10.769    8.55  12.233    7.51  13.957    7.35  16.203    7.22
  18.783    7.32  21.194    7.59  22.673    8.69  24.586     9.1  25.861   14.11
  26.042   15.39  27.695   15.36  27.906   13.48
#Mann= 3 , 0 , 0
       0    .035       0       0    .035       0  27.906    .035       0
Bank Sta=0,27.906
XS Rating Curve= 0
Exp/Cntr=.3,.1

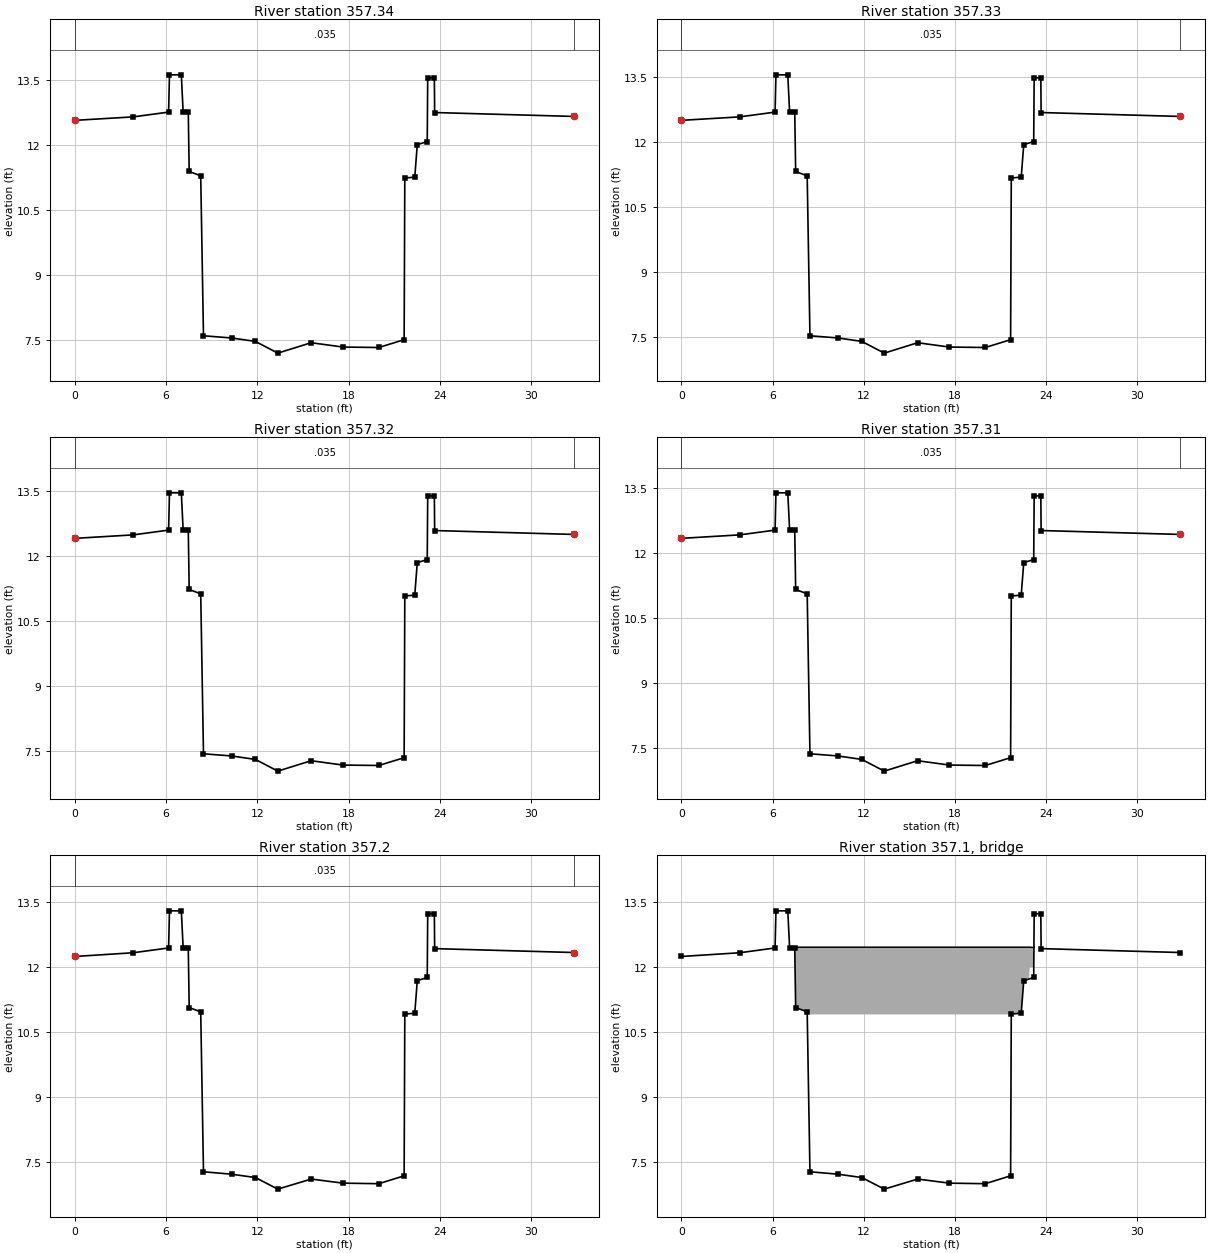
Type RM Length L Ch R = 1 ,357.34  ,95,95,95
#Sta/Elev= 25
       0   12.57   3.834   12.65    6.16   12.76   6.216   13.62   6.996   13.62
   7.116   12.76   7.453   12.76   7.514   11.39   8.272   11.29   8.454     7.6
  10.301    7.55  11.869    7.47  13.344     7.2  15.539    7.44  17.626    7.34
  19.989    7.33  21.656    7.51    21.7   11.24  22.354   11.26  22.521   12.01
  23.176   12.08  23.207   13.55  23.644   13.55  23.664   12.75  32.832   12.66
#Mann= 3 , 0 , 0
       0    .035       0       0    .035       0  32.832    .035       0
Bank Sta=0,32.832
XS Rating Curve= 0
Exp/Cntr=.3,.1

Type RM Length L Ch R = 1 ,357.33  ,95,95,95
#Sta/Elev= 25
       0   12.49   3.834   12.57    6.16   12.68   6.216   13.54   6.996   13.54
   7.116   12.68   7.453   12.68   7.514   11.31   8.272   11.21   8.454    7.52
  10.301    7.47  11.869    7.39  13.344    7.12  15.539    7.36  17.626    7.26
  19.989    7.25  21.656    7.43    21.7   11.16  22.354   11.18  22.521   11.93
  23.176      12  23.207   13.47  23.644   13.47  23.664   12.67  32.832   12.58
#Mann= 3 , 0 , 0
       0    .035       0       0    .035       0  32.832    .035       0
Bank Sta=0,32.832
XS Rating Curve= 0
Exp/Cntr=.3,.1

Type RM Length L Ch R = 1 ,357.32  ,95,95,95
#Sta/Elev= 25
       0   12.41   3.834   12.49    6.16    12.6   6.216   13.46   6.996   13.46
   7.116    12.6   7.453    12.6   7.514   11.23   8.272   11.13   8.454    7.44
  10.301    7.39  11.869    7.31  13.344    7.04  15.539    7.28  17.626    7.18
  19.989    7.17  21.656    7.35    21.7   11.08  22.354    11.1  22.521   11.85
  23.176   11.92  23.207   13.39  23.644   13.39  23.664   12.59  32.832    12.5
#Mann= 3 , 0 , 0
       0    .035       0       0    .035       0  32.832    .035       0
Bank Sta=0,32.832
XS Rating Curve= 0
Exp/Cntr=.3,.1

Type RM Length L Ch R = 1 ,357.31  ,95,95,95
#Sta/Elev= 25
       0   12.33   3.834   12.41    6.16   12.52   6.216   13.38   6.996   13.38
   7.116   12.52   7.453   12.52   7.514   11.15   8.272   11.05   8.454    7.36
  10.301    7.31  11.869    7.23  13.344    6.96  15.539     7.2  17.626     7.1
  19.989    7.09  21.656    7.27    21.7      11  22.354   11.02  22.521   11.77
  23.176   11.84  23.207   13.31  23.644   13.31  23.664   12.51  32.832   12.42
#Mann= 3 , 0 , 0
       0    .035       0       0    .035       0  32.832    .035       0
Bank Sta=0,32.832
XS Rating Curve= 0
Exp/Cntr=.3,.1

Type RM Length L Ch R = 1 ,357.2   ,8,8,8
XS GIS Cut Line= 3
      1613513.06      4851967.74      1613483.72      4851981.75
 1613483.7181962 4851981.7508613
#Sta/Elev= 25
       0  12.246   3.834  12.332    6.16  12.442   6.216  13.298   6.996  13.297
   7.116  12.444   7.453  12.438   7.514  11.067   8.272  10.971   8.454   7.284
  10.301   7.228  11.869   7.151  13.344   6.884  15.539   7.116  17.626   7.022
  19.989   7.009  21.656   7.191    21.7   10.92  22.354  10.937  22.521  11.688
  23.176  11.762  23.207  13.233  23.644  13.229  23.664  12.427  32.832  12.337
#Mann= 3 , 0 , 0
       0    .035       0       0    .035       0  32.832    .035       0
Bank Sta=0,32.832
XS Rating Curve= 0
Exp/Cntr=.3,.1

Type RM Length L Ch R = 3 ,357.1   ,,,
BEGIN DESCRIPTION:
Ponte di Villa Sassine
END DESCRIPTION:
Bridge Culvert--1,0,-1,-1, 0
Deck Dist Width WeirC Skew NumUp NumDn MinLoCord MaxHiCord MaxSubmerge Is_Ogee
.5,7,1.44,0, 18, 18, , , .95, 0, 0,0,,
  7.4499  7.4499  8.0501     8.2 10.0499 11.6199 13.0899 15.2799 17.3699   19.73
 21.3799 21.4201   22.07   22.44 22.8801   22.91 23.2099 23.2099
 12.4599 12.4599 12.4599 12.4599 12.4599 12.4599 12.4599 12.4599 12.4599 12.4599
 12.4599 12.4599 12.4599 12.4599 12.4599 12.4599 12.4499 12.4599
   11.06 10.9701 10.9701   10.91   10.91   10.91   10.91   10.91   10.91   10.91
   10.91   10.91 10.9301 10.8801 11.7601      12      12 12.4599
  7.4499  7.4499  8.0501     8.2 10.0499 11.6199 13.0899 15.2799 17.3699   19.73
 21.3799 21.4201   22.07   22.44 22.8801   22.91 23.2099 23.2099
 12.4599 12.4599 12.4599 12.4599 12.4599 12.4599 12.4599 12.4599 12.4599 12.4599
 12.4599 12.4599 12.4599 12.4599 12.4599 12.4599 12.4499 12.4599
   11.06 10.9701 10.9701   10.91   10.91   10.91   10.91   10.91   10.91   10.91
   10.91   10.91 10.9301 10.8801 11.7601      12      12 12.4599
BR Coef=-1 , 0 , 0 ,1.25, 0 ,,,.8,-1,2,0,
WSPro=,,,, 1 ,,,, 0 ,,,, 0 ,,,,-1 ,-1 ,-1 , 0 , 0 , 0 , 0 , 0
BC Design=,, 0 ,, 0 ,,,,,,
BC HTab Sub Flow Pts= 40

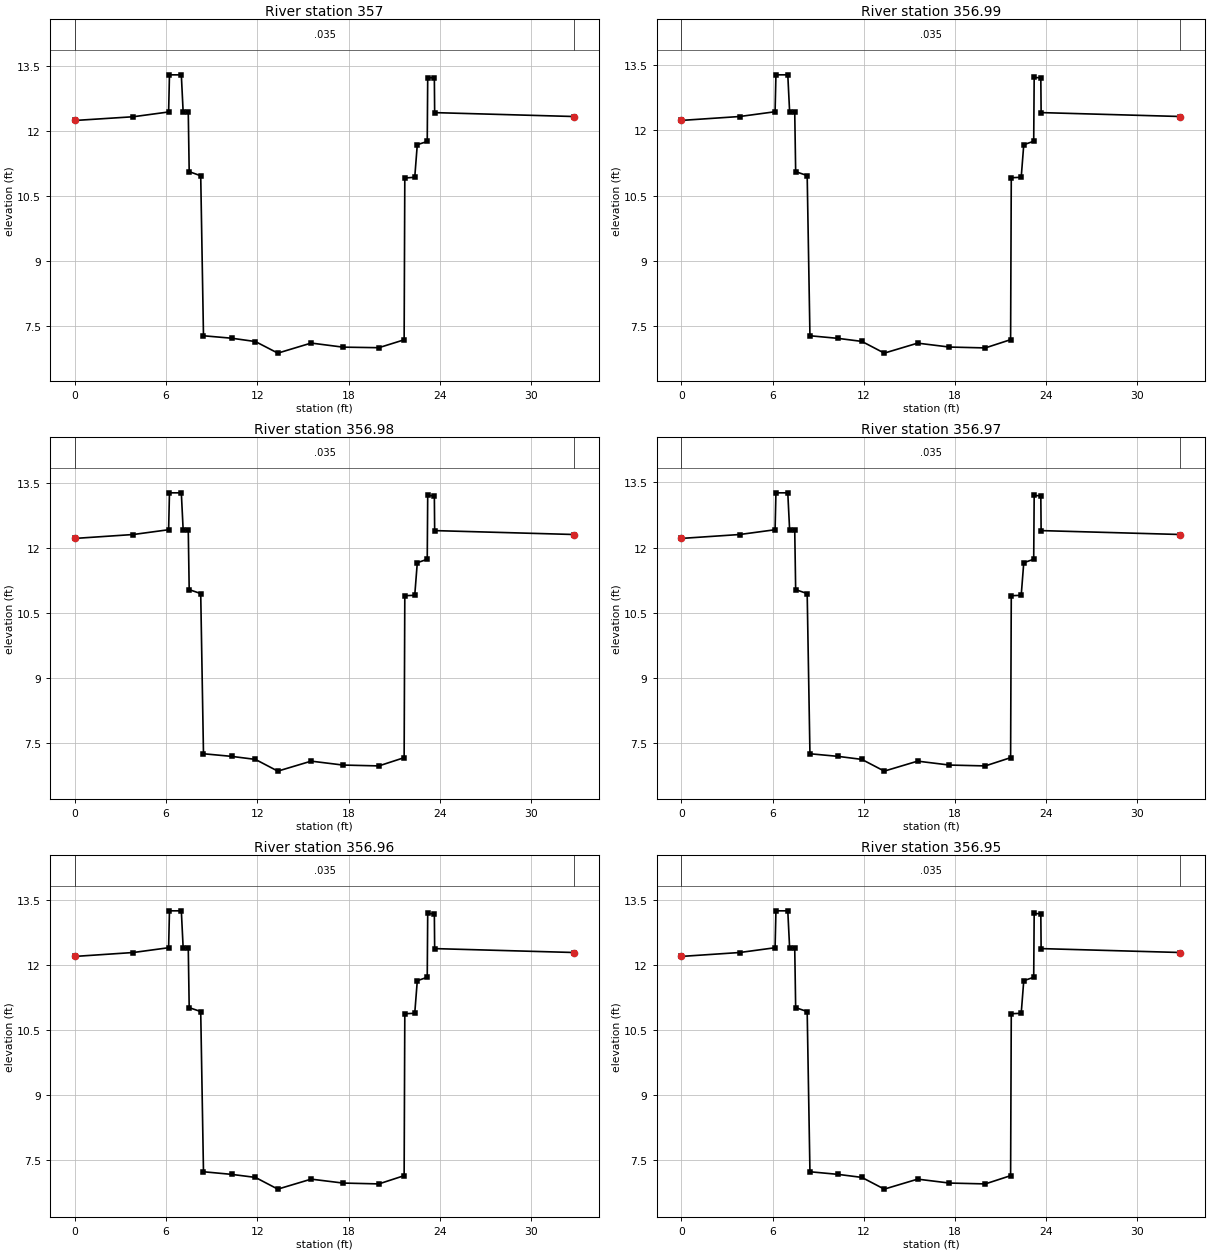
Type RM Length L Ch R = 1 ,357     ,118.9,118.9,118.9
XS GIS Cut Line= 3
      1613513.06      4851967.74      1613483.72      4851981.75
 1613483.7181962 4851981.7508613
#Sta/Elev= 25
       0  12.246   3.834  12.332    6.16  12.442   6.216  13.298   6.996  13.297
   7.116  12.444   7.453  12.438   7.514  11.067   8.272  10.971   8.454   7.284
  10.301   7.228  11.869   7.151  13.344   6.884  15.539   7.116  17.626   7.022
  19.989   7.009  21.656   7.191    21.7   10.92  22.354  10.937  22.521  11.688
  23.176  11.762  23.207  13.233  23.644  13.229  23.664  12.427  32.832  12.337
#Mann= 3 , 0 , 0
       0    .035       0       0    .035       0  32.832    .035       0
Bank Sta=0,32.832
XS Rating Curve= 0
Exp/Cntr=.3,.1

Type RM Length L Ch R = 1 ,356.99  ,118.9,118.9,118.9
#Sta/Elev= 25
       0   12.23   3.834   12.32    6.16   12.43   6.216   13.28   6.996   13.28
   7.116   12.43   7.453   12.42   7.514   11.05   8.272   10.96   8.454    7.27
  10.301    7.21  11.869    7.14  13.344    6.87  15.539     7.1  17.626    7.01
  19.989    6.99  21.656    7.18    21.7   10.91  22.354   10.92  22.521   11.67
  23.176   11.75  23.207   13.22  23.644   13.21  23.664   12.41  32.832   12.32
#Mann= 3 , 0 , 0
       0    .035       0       0    .035       0  32.832    .035       0
Bank Sta=0,32.832
XS Rating Curve= 0
Exp/Cntr=.3,.1

Type RM Length L Ch R = 1 ,356.98  ,118.9,118.9,118.9
#Sta/Elev= 25
       0   12.22   3.834   12.31    6.16   12.42   6.216   13.27   6.996   13.27
   7.116   12.42   7.453   12.41   7.514   11.04   8.272   10.95   8.454    7.26
  10.301     7.2  11.869    7.13  13.344    6.86  15.539    7.09  17.626       7
  19.989    6.98  21.656    7.17    21.7    10.9  22.354   10.91  22.521   11.66
  23.176   11.74  23.207   13.21  23.644    13.2  23.664    12.4  32.832   12.31
#Mann= 3 , 0 , 0
       0    .035       0       0    .035       0  32.832    .035       0
Bank Sta=0,32.832
XS Rating Curve= 0
Exp/Cntr=.3,.1

Type RM Length L Ch R = 1 ,356.97  ,118.9,118.9,118.9
#Sta/Elev= 25
       0   12.21   3.834    12.3    6.16   12.41   6.216   13.26   6.996   13.26
   7.116   12.41   7.453    12.4   7.514   11.03   8.272   10.94   8.454    7.25
  10.301    7.19  11.869    7.12  13.344    6.85  15.539    7.08  17.626    6.99
  19.989    6.97  21.656    7.16    21.7   10.89  22.354    10.9  22.521   11.65
  23.176   11.73  23.207    13.2  23.644   13.19  23.664   12.39  32.832    12.3
#Mann= 3 , 0 , 0
       0    .035       0       0    .035       0  32.832    .035       0
Bank Sta=0,32.832
XS Rating Curve= 0
Exp/Cntr=.3,.1

Type RM Length L Ch R = 1 ,356.96  ,118.9,118.9,118.9
#Sta/Elev= 25
       0    12.2   3.834   12.29    6.16    12.4   6.216   13.25   6.996   13.25
   7.116    12.4   7.453   12.39   7.514   11.02   8.272   10.93   8.454    7.24
  10.301    7.18  11.869    7.11  13.344    6.84  15.539    7.07  17.626    6.98
  19.989    6.96  21.656    7.15    21.7   10.88  22.354   10.89  22.521   11.64
  23.176   11.72  23.207   13.19  23.644   13.18  23.664   12.38  32.832   12.29
#Mann= 3 , 0 , 0
       0    .035       0       0    .035       0  32.832    .035       0
Bank Sta=0,32.832
XS Rating Curve= 0
Exp/Cntr=.3,.1

Type RM Length L Ch R = 1 ,356.95  ,118.9,118.9,118.9
#Sta/Elev= 25
       0   12.19   3.834   12.28    6.16   12.39   6.216   13.24   6.996   13.24
   7.116   12.39   7.453   12.38   7.514   11.01   8.272   10.92   8.454    7.23
  10.301    7.17  11.869     7.1  13.344    6.83  15.539    7.06  17.626    6.97
  19.989    6.95  21.656    7.14    21.7   10.87  22.354   10.88  22.521   11.63
  23.176   11.71  23.207   13.18  23.644   13.17  23.664   12.37  32.832   12.28
#Mann= 3 , 0 , 0
       0    .035       0       0    .035       0  32.832    .035       0
Bank Sta=0,32.832
XS Rating Curve= 0
Exp/Cntr=.3,.1

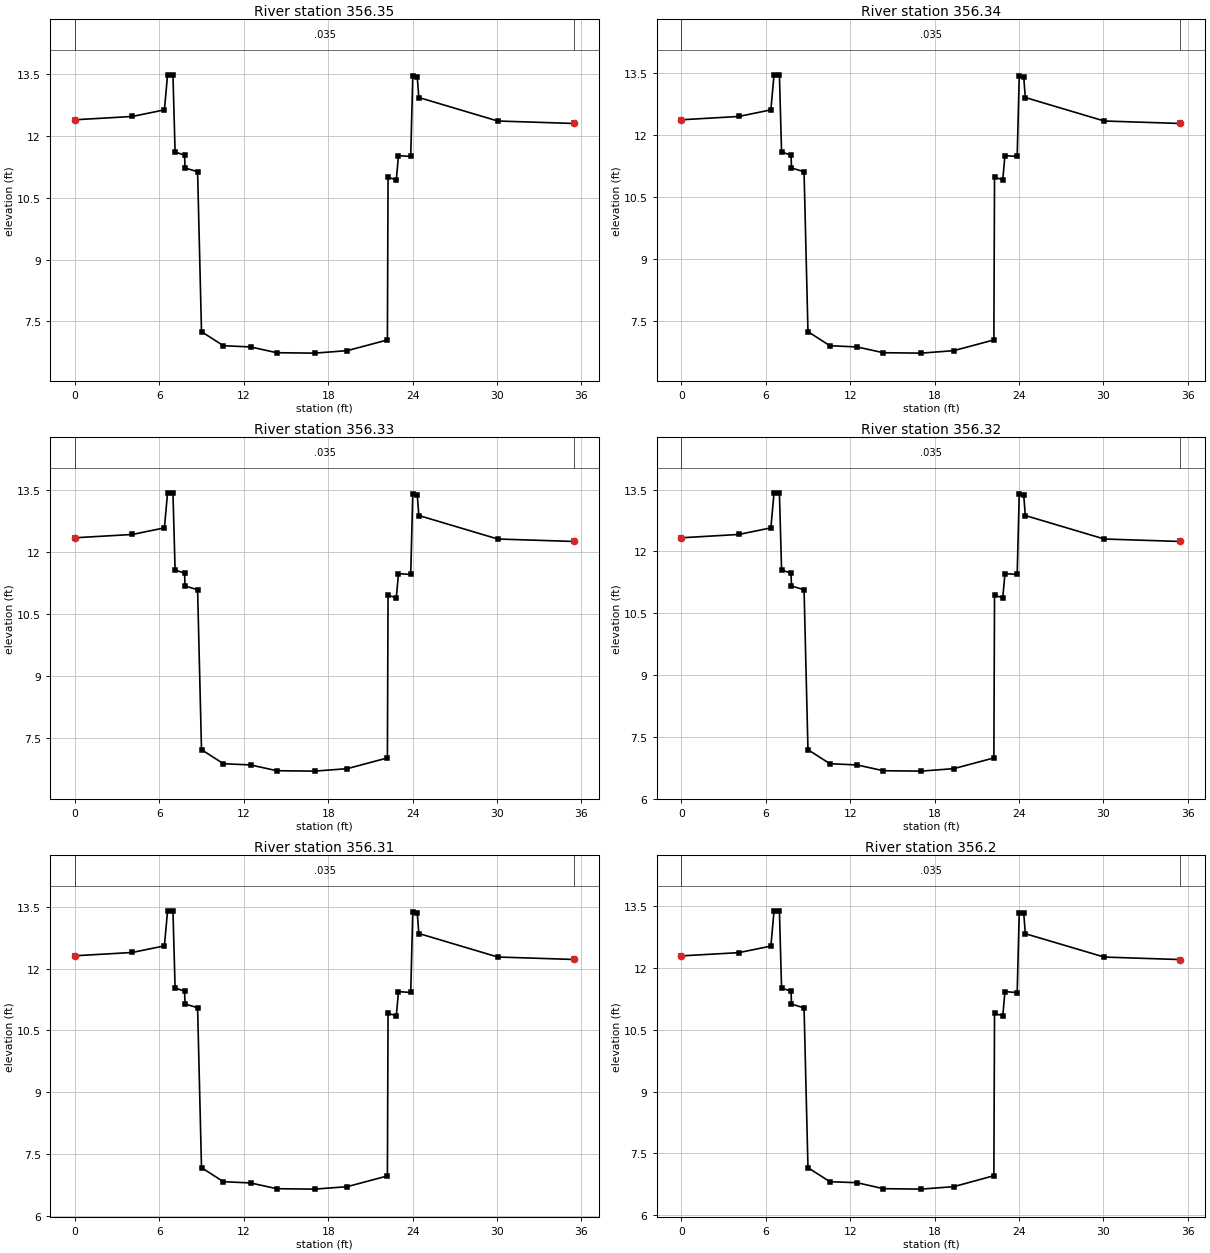
Type RM Length L Ch R = 1 ,356.35  ,118.9,118.9,118.9
#Sta/Elev= 25
       0   12.39   4.074   12.47   6.357   12.63   6.581   13.48   6.964   13.48
   7.117   11.61    7.79   11.53   7.823   11.22   8.716   11.13   8.994    7.25
  10.553    6.91   12.48    6.88  14.351    6.74  17.041    6.73  19.356    6.79
   22.21    7.05  22.257   10.99  22.845   10.94  22.998   11.52  23.868    11.5
  24.013   13.44  24.335   13.42  24.444   12.93  30.055   12.36  35.476    12.3
#Mann= 3 , 0 , 0
       0    .035       0       0    .035       0  35.476    .035       0
Bank Sta=0,35.476
XS Rating Curve= 0
Exp/Cntr=.3,.1

Type RM Length L Ch R = 1 ,356.34  ,118.9,118.9,118.9
#Sta/Elev= 25
       0   12.37   4.074   12.45   6.357   12.61   6.581   13.46   6.964   13.46
   7.117   11.59    7.79   11.51   7.823    11.2   8.716   11.11   8.994    7.23
  10.553    6.89   12.48    6.86  14.351    6.72  17.041    6.71  19.356    6.77
   22.21    7.03  22.257   10.97  22.845   10.92  22.998    11.5  23.868   11.48
  24.013   13.42  24.335    13.4  24.444   12.91  30.055   12.34  35.476   12.28
#Mann= 3 , 0 , 0
       0    .035       0       0    .035       0  35.476    .035       0
Bank Sta=0,35.476
XS Rating Curve= 0
Exp/Cntr=.3,.1

Type RM Length L Ch R = 1 ,356.33  ,118.9,118.9,118.9
#Sta/Elev= 25
       0   12.35   4.074   12.43   6.357   12.59   6.581   13.44   6.964   13.44
   7.117   11.57    7.79   11.49   7.823   11.18   8.716   11.09   8.994    7.21
  10.553    6.87   12.48    6.84  14.351     6.7  17.041    6.69  19.356    6.75
   22.21    7.01  22.257   10.95  22.845    10.9  22.998   11.48  23.868   11.46
  24.013    13.4  24.335   13.38  24.444   12.89  30.055   12.32  35.476   12.26
#Mann= 3 , 0 , 0
       0    .035       0       0    .035       0  35.476    .035       0
Bank Sta=0,35.476
XS Rating Curve= 0
Exp/Cntr=.3,.1

Type RM Length L Ch R = 1 ,356.32  ,118.9,118.9,118.9
#Sta/Elev= 25
       0   12.33   4.074   12.41   6.357   12.57   6.581   13.42   6.964   13.42
   7.117   11.55    7.79   11.47   7.823   11.16   8.716   11.07   8.994    7.19
  10.553    6.85   12.48    6.82  14.351    6.68  17.041    6.67  19.356    6.73
   22.21    6.99  22.257   10.93  22.845   10.88  22.998   11.46  23.868   11.44
  24.013   13.38  24.335   13.36  24.444   12.87  30.055    12.3  35.476   12.24
#Mann= 3 , 0 , 0
       0    .035       0       0    .035       0  35.476    .035       0
Bank Sta=0,35.476
XS Rating Curve= 0
Exp/Cntr=.3,.1

Type RM Length L Ch R = 1 ,356.31  ,118.9,118.9,118.9
#Sta/Elev= 25
       0   12.31   4.074   12.39   6.357   12.55   6.581    13.4   6.964    13.4
   7.117   11.53    7.79   11.45   7.823   11.14   8.716   11.05   8.994    7.17
  10.553    6.83   12.48     6.8  14.351    6.66  17.041    6.65  19.356    6.71
   22.21    6.97  22.257   10.91  22.845   10.86  22.998   11.44  23.868   11.42
  24.013   13.36  24.335   13.34  24.444   12.85  30.055   12.28  35.476   12.22
#Mann= 3 , 0 , 0
       0    .035       0       0    .035       0  35.476    .035       0
Bank Sta=0,35.476
XS Rating Curve= 0
Exp/Cntr=.3,.1

Type RM Length L Ch R = 1 ,356.2   ,8,8,8
XS GIS Cut Line= 2
      1612807.86      4850902.43 1612778.5138345 4850897.0407042
#Sta/Elev= 25
       0  12.294   4.074  12.372   6.357  12.531   6.581  13.382   6.964  13.387
   7.117  11.512    7.79  11.438   7.823  11.123   8.716  11.032   8.994   7.153
  10.553   6.813   12.48   6.789  14.351   6.644  17.041   6.633  19.356   6.693
   22.21   6.958  22.257  10.899  22.845   10.84  22.998  11.427  23.868  11.402
  24.013  13.343  24.335  13.328  24.444  12.832  30.055  12.265  35.476  12.204
#Mann= 3 , 0 , 0
       0    .035       0       0    .035       0  35.476    .035       0
Bank Sta=0,35.476
XS Rating Curve= 0
Exp/Cntr=.3,.1

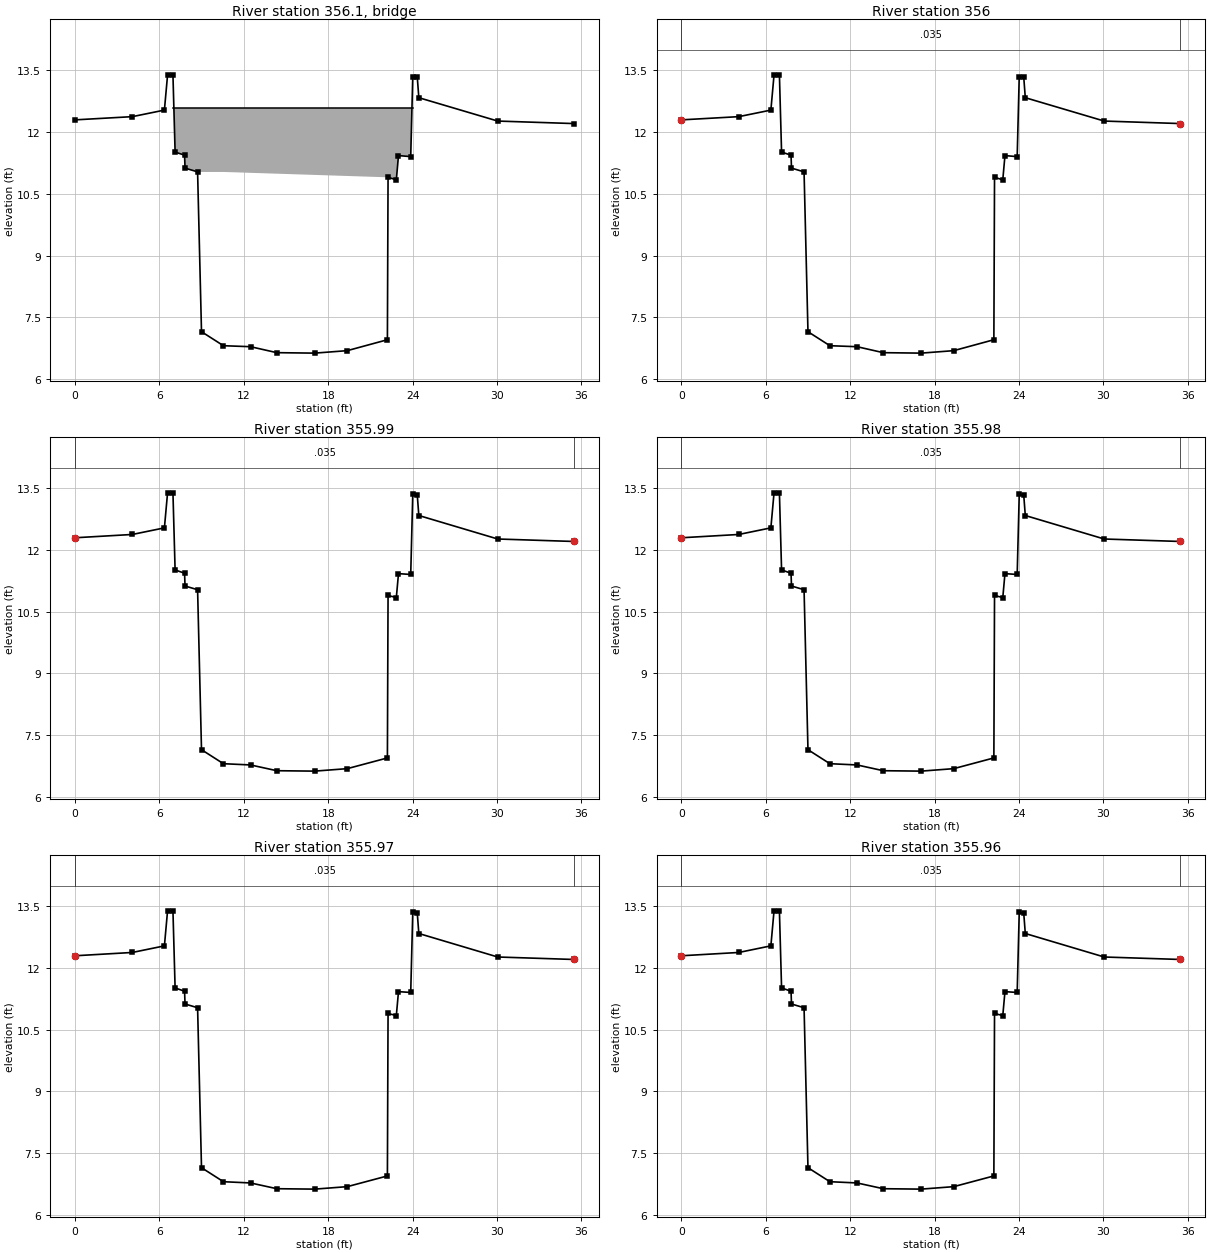
Type RM Length L Ch R = 3 ,356.1   ,,,
BEGIN DESCRIPTION:
Ponte di Colognore
END DESCRIPTION:
Bridge Culvert--1,0,-1,-1, 0
Deck Dist Width WeirC Skew NumUp NumDn MinLoCord MaxHiCord MaxSubmerge Is_Ogee
.5,7,1.44,0, 11, 11, , , .95, 0, 0,0,,
  6.9601  7.1201  7.7901  7.8199    8.72   10.55 22.2598 22.8499 22.9999 23.8701
   24.01
   12.58   12.58   12.58   12.58   12.58   12.58   12.58   12.58   12.58   12.58
   12.58
   12.58 11.5099 11.4401   11.12 11.0301 11.0301    10.9 10.8399   11.43 11.4001
   12.58
  6.9601  7.1201  7.7901  7.8199    8.72   10.55 22.2598 22.8499 22.9999 23.8701
   24.01
   12.58   12.58   12.58   12.58   12.58   12.58   12.58   12.58   12.58   12.58
   12.58
   12.58 11.5099 11.4401   11.12 11.0301 11.0301    10.9 10.8399   11.43 11.4001
   12.58
BR Coef=-1 , 0 , 0 ,1.25, 0 ,,,.8,-1,2,0,
WSPro=,,,, 1 ,,,, 0 ,,,, 0 ,,,,-1 ,-1 ,-1 , 0 , 0 , 0 , 0 , 0
BC Design=,, 0 ,, 0 ,,,,,,
BC HTab Sub Flow Pts= 40

Type RM Length L Ch R = 1 ,356     ,75,75,75
XS GIS Cut Line= 2
      1612807.86      4850902.43 1612810.4961669 4850902.9192885
#Sta/Elev= 25
       0  12.294   4.074  12.372   6.357  12.531   6.581  13.382   6.964  13.387
   7.117  11.512    7.79  11.438   7.823  11.123   8.716  11.032   8.994   7.153
  10.553   6.813   12.48   6.789  14.351   6.644  17.041   6.633  19.356   6.693
   22.21   6.958  22.257  10.899  22.845   10.84  22.998  11.427  23.868  11.402
  24.013  13.343  24.335  13.328  24.444  12.832  30.055  12.265  35.476  12.204
#Mann= 3 , 0 , 0
       0    .035       0       0    .035       0  35.476    .035       0
Bank Sta=0,35.476
XS Rating Curve= 0
Exp/Cntr=.3,.1

Type RM Length L Ch R = 1 ,355.99  ,75,75,75
#Sta/Elev= 25
       0   12.29   4.074   12.37   6.357   12.53   6.581   13.38   6.964   13.38
   7.117   11.51    7.79   11.43   7.823   11.12   8.716   11.03   8.994    7.15
  10.553    6.81   12.48    6.78  14.351    6.64  17.041    6.63  19.356    6.69
   22.21    6.95  22.257   10.89  22.845   10.84  22.998   11.42  23.868    11.4
  24.013   13.34  24.335   13.32  24.444   12.83  30.055   12.26  35.476    12.2
#Mann= 3 , 0 , 0
       0    .035       0       0    .035       0  35.476    .035       0
Bank Sta=0,35.476
XS Rating Curve= 0
Exp/Cntr=.3,.1

Type RM Length L Ch R = 1 ,355.98  ,75,75,75
#Sta/Elev= 25
       0   12.29   4.074   12.37   6.357   12.53   6.581   13.38   6.964   13.38
   7.117   11.51    7.79   11.43   7.823   11.12   8.716   11.03   8.994    7.15
  10.553    6.81   12.48    6.78  14.351    6.64  17.041    6.63  19.356    6.69
   22.21    6.95  22.257   10.89  22.845   10.84  22.998   11.42  23.868    11.4
  24.013   13.34  24.335   13.32  24.444   12.83  30.055   12.26  35.476    12.2
#Mann= 3 , 0 , 0
       0    .035       0       0    .035       0  35.476    .035       0
Bank Sta=0,35.476
XS Rating Curve= 0
Exp/Cntr=.3,.1

Type RM Length L Ch R = 1 ,355.97  ,75,75,75
#Sta/Elev= 25
       0   12.29   4.074   12.37   6.357   12.53   6.581   13.38   6.964   13.38
   7.117   11.51    7.79   11.43   7.823   11.12   8.716   11.03   8.994    7.15
  10.553    6.81   12.48    6.78  14.351    6.64  17.041    6.63  19.356    6.69
   22.21    6.95  22.257   10.89  22.845   10.84  22.998   11.42  23.868    11.4
  24.013   13.34  24.335   13.32  24.444   12.83  30.055   12.26  35.476    12.2
#Mann= 3 , 0 , 0
       0    .035       0       0    .035       0  35.476    .035       0
Bank Sta=0,35.476
XS Rating Curve= 0
Exp/Cntr=.3,.1

Type RM Length L Ch R = 1 ,355.96  ,75,75,75
#Sta/Elev= 25
       0   12.29   4.074   12.37   6.357   12.53   6.581   13.38   6.964   13.38
   7.117   11.51    7.79   11.43   7.823   11.12   8.716   11.03   8.994    7.15
  10.553    6.81   12.48    6.78  14.351    6.64  17.041    6.63  19.356    6.69
   22.21    6.95  22.257   10.89  22.845   10.84  22.998   11.42  23.868    11.4
  24.013   13.34  24.335   13.32  24.444   12.83  30.055   12.26  35.476    12.2
#Mann= 3 , 0 , 0
       0    .035       0       0    .035       0  35.476    .035       0
Bank Sta=0,35.476
XS Rating Curve= 0
Exp/Cntr=.3,.1

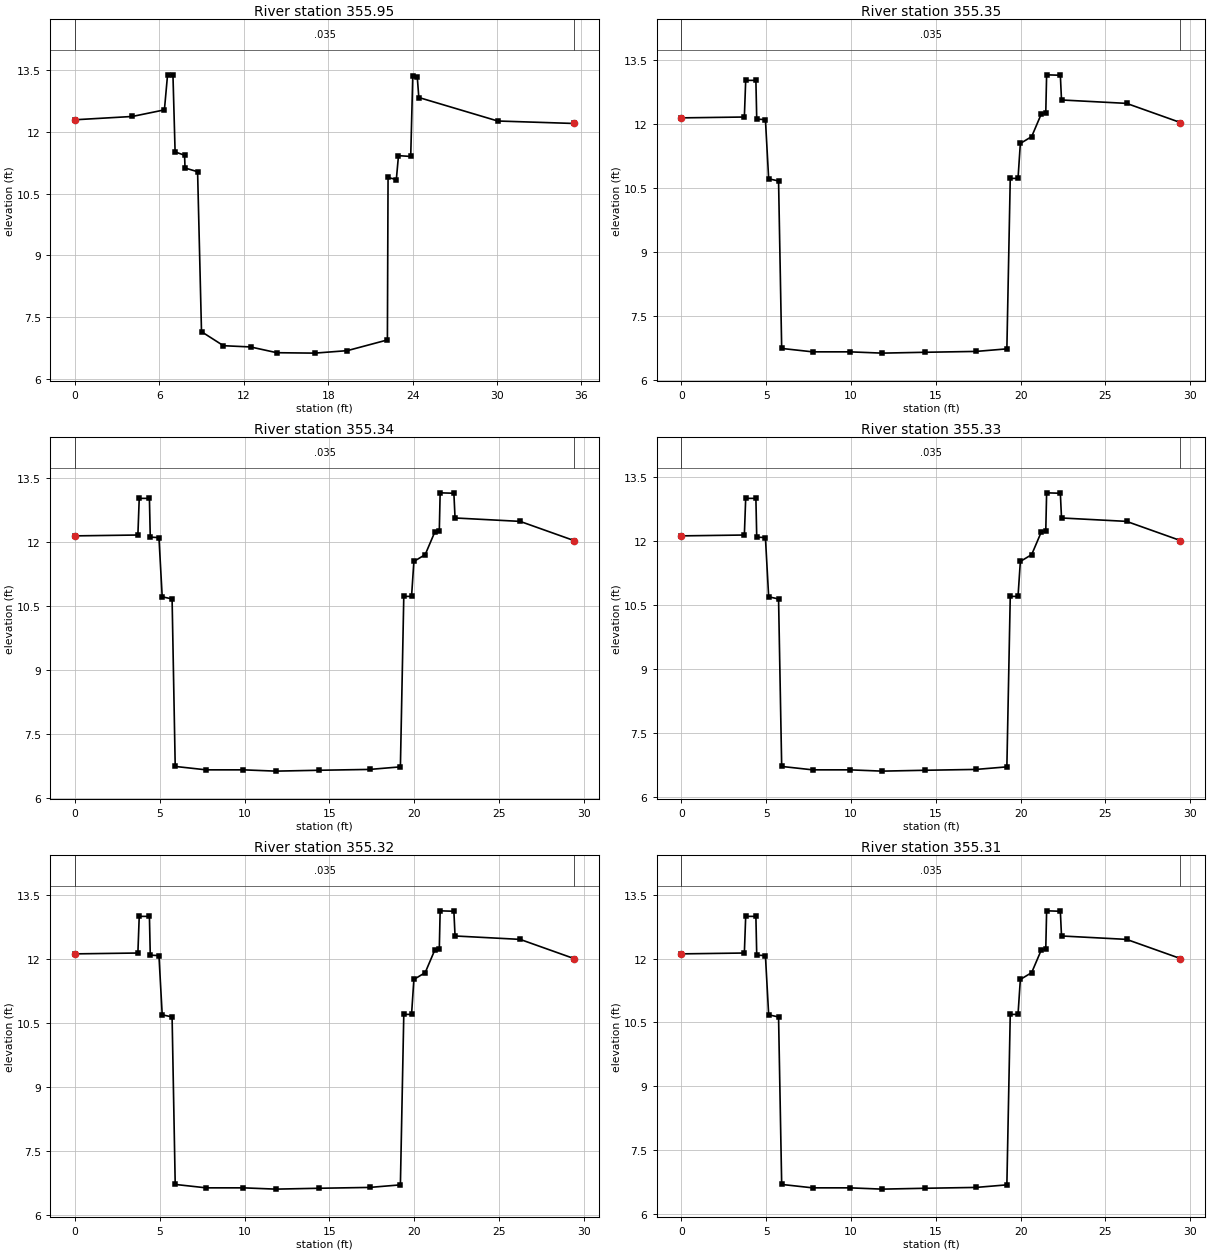
Type RM Length L Ch R = 1 ,355.95  ,75,75,75
#Sta/Elev= 25
       0   12.29   4.074   12.37   6.357   12.53   6.581   13.38   6.964   13.38
   7.117   11.51    7.79   11.43   7.823   11.12   8.716   11.03   8.994    7.15
  10.553    6.81   12.48    6.78  14.351    6.64  17.041    6.63  19.356    6.69
   22.21    6.95  22.257   10.89  22.845   10.84  22.998   11.42  23.868    11.4
  24.013   13.34  24.335   13.32  24.444   12.83  30.055   12.26  35.476    12.2
#Mann= 3 , 0 , 0
       0    .035       0       0    .035       0  35.476    .035       0
Bank Sta=0,35.476
XS Rating Curve= 0
Exp/Cntr=.3,.1

Type RM Length L Ch R = 1 ,355.35  ,75,75,75
#Sta/Elev= 26
       0   12.15   3.709   12.17   3.788   13.03   4.389   13.03   4.439   12.12
   4.951   12.11   5.143   10.72   5.726   10.67    5.91    6.74   7.739    6.66
   9.932    6.66  11.836    6.63   14.36    6.65  17.373    6.67  19.189    6.73
  19.389   10.73  19.847   10.73  19.984   11.55  20.651   11.71  21.228   12.25
  21.483   12.26  21.533   13.16  22.343   13.15  22.411   12.57  26.247   12.49
  29.426   12.04
#Mann= 3 , 0 , 0
       0    .035       0       0    .035       0  29.426    .035       0
Bank Sta=0,29.426
XS Rating Curve= 0
Exp/Cntr=.3,.1

Type RM Length L Ch R = 1 ,355.34  ,75,75,75
#Sta/Elev= 26
       0   12.14   3.709   12.16   3.788   13.02   4.389   13.02   4.439   12.11
   4.951    12.1   5.143   10.71   5.726   10.66    5.91    6.73   7.739    6.65
   9.932    6.65  11.836    6.62   14.36    6.64  17.373    6.66  19.189    6.72
  19.389   10.72  19.847   10.72  19.984   11.54  20.651    11.7  21.228   12.24
  21.483   12.25  21.533   13.15  22.343   13.14  22.411   12.56  26.247   12.48
  29.426   12.03
#Mann= 3 , 0 , 0
       0    .035       0       0    .035       0  29.426    .035       0
Bank Sta=0,29.426
XS Rating Curve= 0
Exp/Cntr=.3,.1

Type RM Length L Ch R = 1 ,355.33  ,75,75,75
#Sta/Elev= 26
       0   12.13   3.709   12.15   3.788   13.01   4.389   13.01   4.439    12.1
   4.951   12.09   5.143    10.7   5.726   10.65    5.91    6.72   7.739    6.64
   9.932    6.64  11.836    6.61   14.36    6.63  17.373    6.65  19.189    6.71
  19.389   10.71  19.847   10.71  19.984   11.53  20.651   11.69  21.228   12.23
  21.483   12.24  21.533   13.14  22.343   13.13  22.411   12.55  26.247   12.47
  29.426   12.02
#Mann= 3 , 0 , 0
       0    .035       0       0    .035       0  29.426    .035       0
Bank Sta=0,29.426
XS Rating Curve= 0
Exp/Cntr=.3,.1

Type RM Length L Ch R = 1 ,355.32  ,75,75,75
#Sta/Elev= 26
       0   12.12   3.709   12.14   3.788      13   4.389      13   4.439   12.09
   4.951   12.08   5.143   10.69   5.726   10.64    5.91    6.71   7.739    6.63
   9.932    6.63  11.836     6.6   14.36    6.62  17.373    6.64  19.189     6.7
  19.389    10.7  19.847    10.7  19.984   11.52  20.651   11.68  21.228   12.22
  21.483   12.23  21.533   13.13  22.343   13.12  22.411   12.54  26.247   12.46
  29.426   12.01
#Mann= 3 , 0 , 0
       0    .035       0       0    .035       0  29.426    .035       0
Bank Sta=0,29.426
XS Rating Curve= 0
Exp/Cntr=.3,.1

Type RM Length L Ch R = 1 ,355.31  ,75,75,75
#Sta/Elev= 26
       0   12.11   3.709   12.13   3.788   12.99   4.389   12.99   4.439   12.08
   4.951   12.07   5.143   10.68   5.726   10.63    5.91     6.7   7.739    6.62
   9.932    6.62  11.836    6.59   14.36    6.61  17.373    6.63  19.189    6.69
  19.389   10.69  19.847   10.69  19.984   11.51  20.651   11.67  21.228   12.21
  21.483   12.22  21.533   13.12  22.343   13.11  22.411   12.53  26.247   12.45
  29.426      12
#Mann= 3 , 0 , 0
       0    .035       0       0    .035       0  29.426    .035       0
Bank Sta=0,29.426
XS Rating Curve= 0
Exp/Cntr=.3,.1

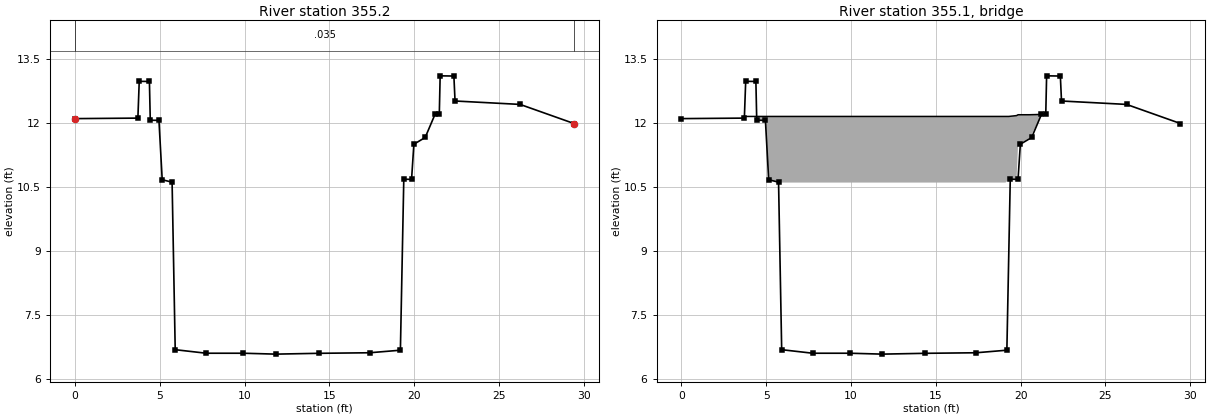
Type RM Length L Ch R = 1 ,355.2   ,8,8,8
XS GIS Cut Line= 3
      1613328.38      4850281.68      1613310.14      4850260.24
 1613310.1360475 4850260.2353541
#Sta/Elev= 26
       0  12.109   3.709  12.121   3.788  12.983   4.389   12.98   4.439  12.071
   4.951  12.069   5.143  10.676   5.726   10.62    5.91   6.693   7.739    6.61
   9.932    6.61  11.836   6.589   14.36   6.608  17.373   6.621  19.189   6.681
  19.389  10.689  19.847  10.685  19.984  11.509  20.651  11.667  21.228  12.207
  21.483  12.215  21.533  13.112  22.343  13.107  22.411  12.522  26.247  12.442
  29.426  11.994
#Mann= 3 , 0 , 0
       0    .035       0       0    .035       0  29.426    .035       0
Bank Sta=0,29.426
XS Rating Curve= 0
Exp/Cntr=.3,.1

Type RM Length L Ch R = 3 ,355.1   ,,,
BEGIN DESCRIPTION:
Ponte di Patrignone
END DESCRIPTION:
Bridge Culvert--1,0,-1,-1, 0
Deck Dist Width WeirC Skew NumUp NumDn MinLoCord MaxHiCord MaxSubmerge Is_Ogee
.5,7,1.44,0, 19, 19, , , .95, 0, 0,0,,
     3.7    3.76  4.3599  4.4102  4.9201    5.11    5.69    5.85    7.67    9.86
 11.7601 14.2899 17.3001   19.11 19.2999 19.7599 19.8501 20.5201 21.4799
   12.16   12.16   12.16   12.16   12.16   12.16   12.16   12.16   12.16   12.16
   12.16   12.16   12.16   12.16   12.16 12.1801 12.1999 12.1999   12.21
 10.6101 10.6101 10.6101 10.6101 10.6101 10.6101 10.6101 10.6101 10.6101 10.6101
 10.6101 10.6101 10.6101 10.6101 10.6799 10.6799 11.5001 11.6601   12.21
     3.7    3.76  4.3599  4.4102  4.9201    5.11    5.69    5.85    7.67    9.86
 11.7601 14.2899 17.3001   19.11 19.2999 19.7599 19.8501 20.5201 21.4799
   12.16   12.16   12.16   12.16   12.16   12.16   12.16   12.16   12.16   12.16
   12.16   12.16   12.16   12.16   12.16 12.1801 12.1999 12.1999   12.21
 10.6101 10.6101 10.6101 10.6101 10.6101 10.6101 10.6101 10.6101 10.6101 10.6101
 10.6101 10.6101 10.6101 10.6101 10.6799 10.6799 11.5001 11.6601   12.21
BR Coef=-1 , 0 , 0 ,1.25, 0 ,,,.8,-1,2,0,
WSPro=,,,, 1 ,,,, 0 ,,,, 0 ,,,,-1 ,-1 ,-1 , 0 , 0 , 0 , 0 , 0
BC Design=,, 0 ,, 0 ,,,,,,
BC HTab Sub Flow Pts= 40