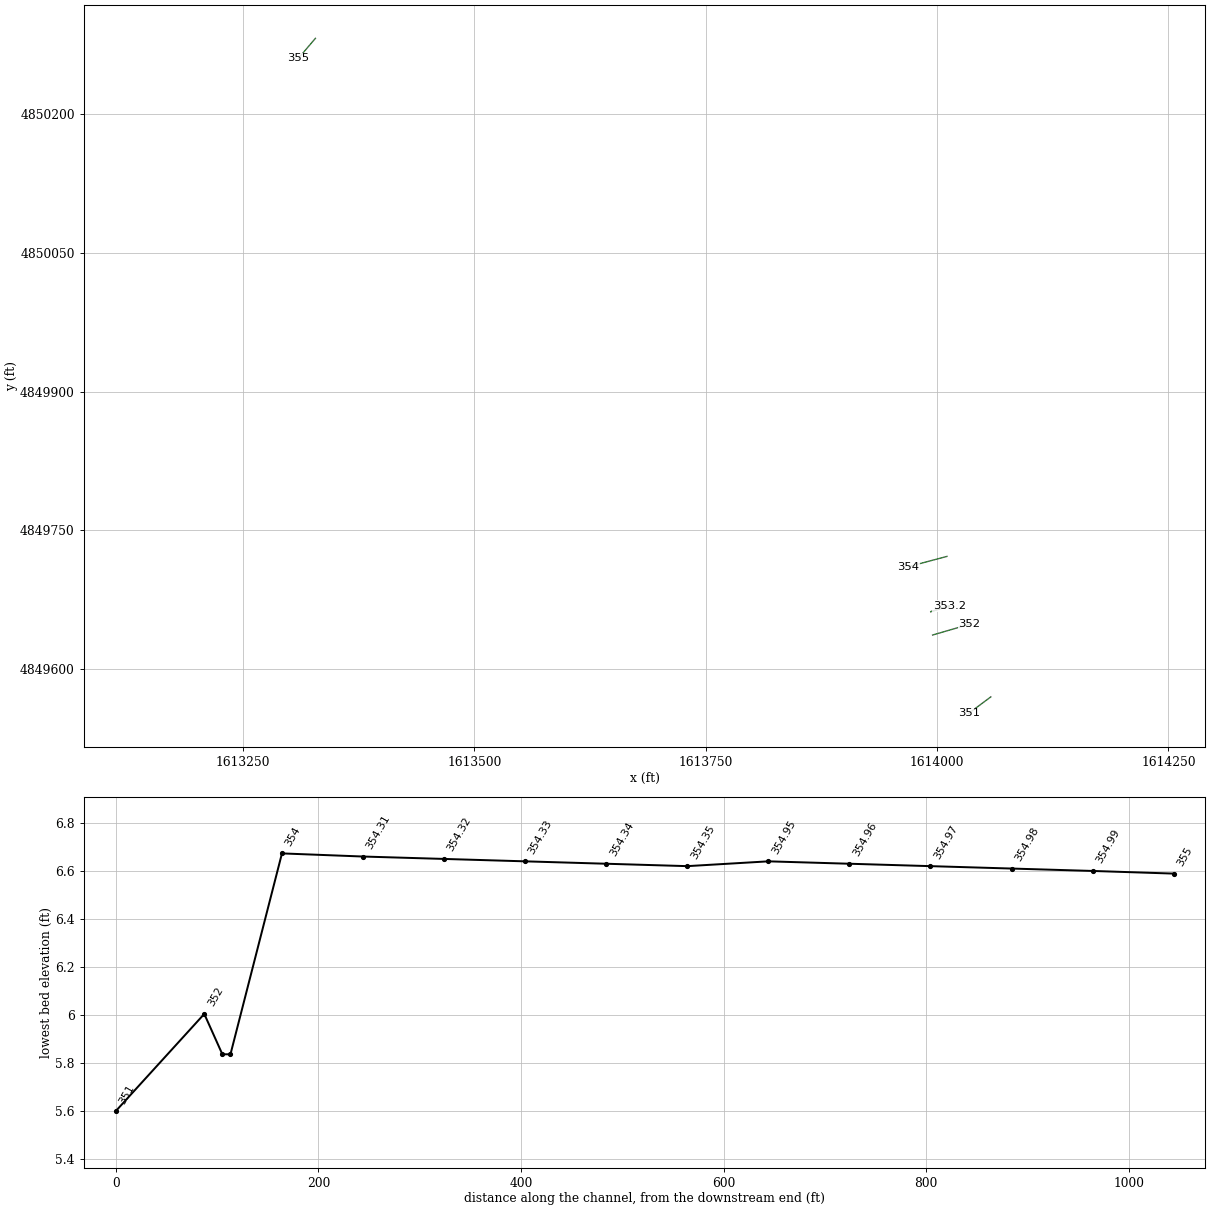
HEC-RAS study ozz_def.prj: ozzeri

--- ozz_def.g02 (geometry) --- (continued)

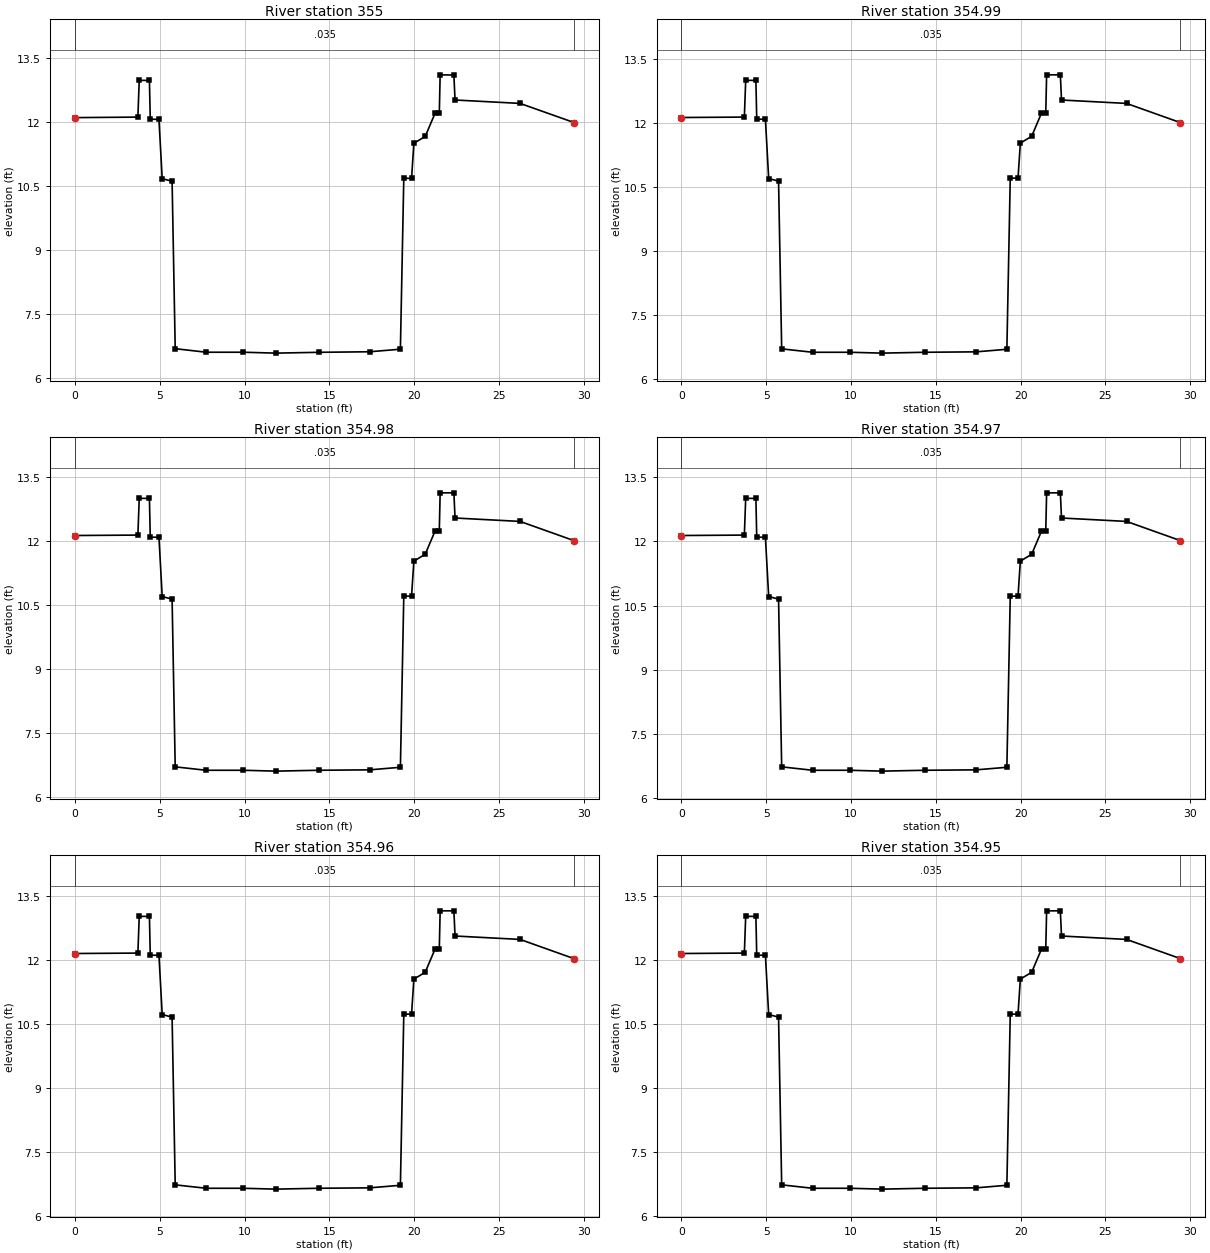
Type RM Length L Ch R = 1 ,355     ,80,80,80
XS GIS Cut Line= 3
      1613328.38      4850281.68      1613310.14      4850260.24
 1613310.1360475 4850260.2353541
#Sta/Elev= 26
       0  12.109   3.709  12.121   3.788  12.983   4.389   12.98   4.439  12.071
   4.951  12.069   5.143  10.676   5.726   10.62    5.91   6.693   7.739    6.61
   9.932    6.61  11.836   6.589   14.36   6.608  17.373   6.621  19.189   6.681
  19.389  10.689  19.847  10.685  19.984  11.509  20.651  11.667  21.228  12.207
  21.483  12.215  21.533  13.112  22.343  13.107  22.411  12.522  26.247  12.442
  29.426  11.994
#Mann= 3 , 0 , 0
       0    .035       0       0    .035       0  29.426    .035       0
Bank Sta=0,29.426
XS Rating Curve= 0
Exp/Cntr=.3,.1

Type RM Length L Ch R = 1 ,354.99  ,80,80,80
#Sta/Elev= 26
       0   12.12   3.709   12.13   3.788   12.99   4.389   12.99   4.439   12.08
   4.951   12.08   5.143   10.69   5.726   10.63    5.91     6.7   7.739    6.62
   9.932    6.62  11.836     6.6   14.36    6.62  17.373    6.63  19.189    6.69
  19.389    10.7  19.847    10.7  19.984   11.52  20.651   11.68  21.228   12.22
  21.483   12.23  21.533   13.12  22.343   13.12  22.411   12.53  26.247   12.45
  29.426      12
#Mann= 3 , 0 , 0
       0    .035       0       0    .035       0  29.426    .035       0
Bank Sta=0,29.426
XS Rating Curve= 0
Exp/Cntr=.3,.1

Type RM Length L Ch R = 1 ,354.98  ,80,80,80
#Sta/Elev= 26
       0   12.13   3.709   12.14   3.788      13   4.389      13   4.439   12.09
   4.951   12.09   5.143    10.7   5.726   10.64    5.91    6.71   7.739    6.63
   9.932    6.63  11.836    6.61   14.36    6.63  17.373    6.64  19.189     6.7
  19.389   10.71  19.847   10.71  19.984   11.53  20.651   11.69  21.228   12.23
  21.483   12.24  21.533   13.13  22.343   13.13  22.411   12.54  26.247   12.46
  29.426   12.01
#Mann= 3 , 0 , 0
       0    .035       0       0    .035       0  29.426    .035       0
Bank Sta=0,29.426
XS Rating Curve= 0
Exp/Cntr=.3,.1

Type RM Length L Ch R = 1 ,354.97  ,80,80,80
#Sta/Elev= 26
       0   12.14   3.709   12.15   3.788   13.01   4.389   13.01   4.439    12.1
   4.951    12.1   5.143   10.71   5.726   10.65    5.91    6.72   7.739    6.64
   9.932    6.64  11.836    6.62   14.36    6.64  17.373    6.65  19.189    6.71
  19.389   10.72  19.847   10.72  19.984   11.54  20.651    11.7  21.228   12.24
  21.483   12.25  21.533   13.14  22.343   13.14  22.411   12.55  26.247   12.47
  29.426   12.02
#Mann= 3 , 0 , 0
       0    .035       0       0    .035       0  29.426    .035       0
Bank Sta=0,29.426
XS Rating Curve= 0
Exp/Cntr=.3,.1

Type RM Length L Ch R = 1 ,354.96  ,80,80,80
#Sta/Elev= 26
       0   12.15   3.709   12.16   3.788   13.02   4.389   13.02   4.439   12.11
   4.951   12.11   5.143   10.72   5.726   10.66    5.91    6.73   7.739    6.65
   9.932    6.65  11.836    6.63   14.36    6.65  17.373    6.66  19.189    6.72
  19.389   10.73  19.847   10.73  19.984   11.55  20.651   11.71  21.228   12.25
  21.483   12.26  21.533   13.15  22.343   13.15  22.411   12.56  26.247   12.48
  29.426   12.03
#Mann= 3 , 0 , 0
       0    .035       0       0    .035       0  29.426    .035       0
Bank Sta=0,29.426
XS Rating Curve= 0
Exp/Cntr=.3,.1

Type RM Length L Ch R = 1 ,354.95  ,80,80,80
#Sta/Elev= 26
       0   12.16   3.709   12.17   3.788   13.03   4.389   13.03   4.439   12.12
   4.951   12.12   5.143   10.73   5.726   10.67    5.91    6.74   7.739    6.66
   9.932    6.66  11.836    6.64   14.36    6.66  17.373    6.67  19.189    6.73
  19.389   10.74  19.847   10.74  19.984   11.56  20.651   11.72  21.228   12.26
  21.483   12.27  21.533   13.16  22.343   13.16  22.411   12.57  26.247   12.49
  29.426   12.04
#Mann= 3 , 0 , 0
       0    .035       0       0    .035       0  29.426    .035       0
Bank Sta=0,29.426
XS Rating Curve= 0
Exp/Cntr=.3,.1

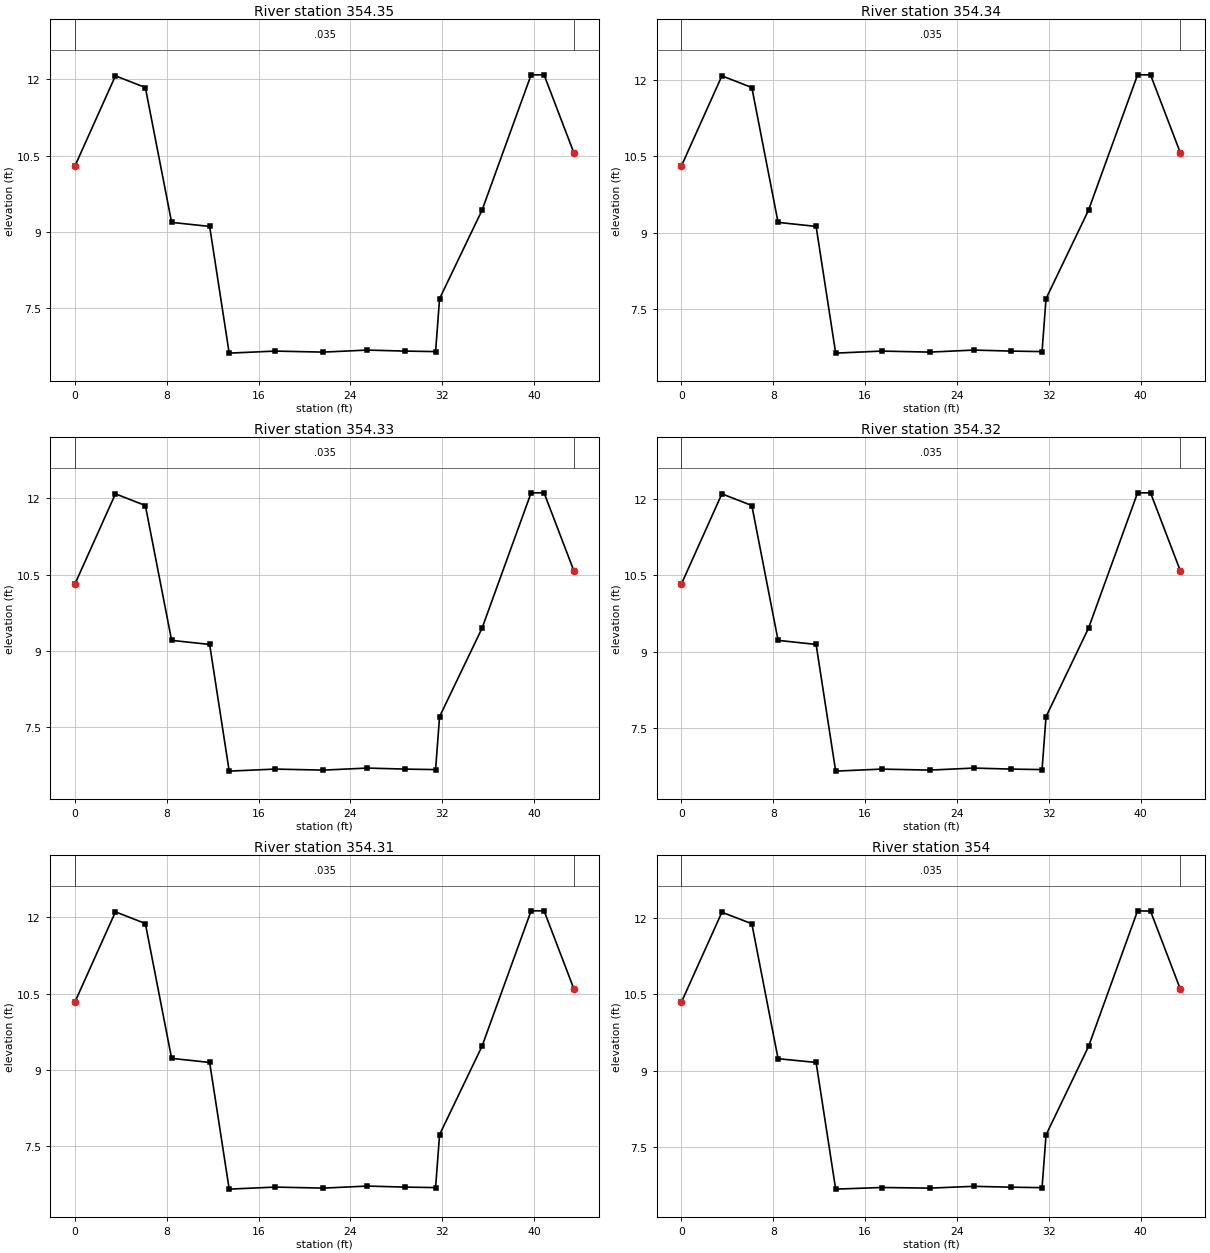
Type RM Length L Ch R = 1 ,354.35  ,80,80,80
#Sta/Elev= 16
       0    10.3   3.524   12.07   6.131   11.84   8.417    9.19  11.731    9.11
  13.434    6.62   17.43    6.66  21.638    6.64   25.46    6.68  28.741    6.66
  31.415    6.65  31.761    7.69  35.463    9.43  39.737   12.09  40.865   12.09
  43.473   10.55
#Mann= 3 , 0 , 0
       0    .035       0       0    .035       0  43.473    .035       0
Bank Sta=0,43.473
XS Rating Curve= 0
Exp/Cntr=.3,.1

Type RM Length L Ch R = 1 ,354.34  ,80,80,80
#Sta/Elev= 16
       0   10.31   3.524   12.08   6.131   11.85   8.417     9.2  11.731    9.12
  13.434    6.63   17.43    6.67  21.638    6.65   25.46    6.69  28.741    6.67
  31.415    6.66  31.761     7.7  35.463    9.44  39.737    12.1  40.865    12.1
  43.473   10.56
#Mann= 3 , 0 , 0
       0    .035       0       0    .035       0  43.473    .035       0
Bank Sta=0,43.473
XS Rating Curve= 0
Exp/Cntr=.3,.1

Type RM Length L Ch R = 1 ,354.33  ,80,80,80
#Sta/Elev= 16
       0   10.32   3.524   12.09   6.131   11.86   8.417    9.21  11.731    9.13
  13.434    6.64   17.43    6.68  21.638    6.66   25.46     6.7  28.741    6.68
  31.415    6.67  31.761    7.71  35.463    9.45  39.737   12.11  40.865   12.11
  43.473   10.57
#Mann= 3 , 0 , 0
       0    .035       0       0    .035       0  43.473    .035       0
Bank Sta=0,43.473
XS Rating Curve= 0
Exp/Cntr=.3,.1

Type RM Length L Ch R = 1 ,354.32  ,80,80,80
#Sta/Elev= 16
       0   10.33   3.524    12.1   6.131   11.87   8.417    9.22  11.731    9.14
  13.434    6.65   17.43    6.69  21.638    6.67   25.46    6.71  28.741    6.69
  31.415    6.68  31.761    7.72  35.463    9.46  39.737   12.12  40.865   12.12
  43.473   10.58
#Mann= 3 , 0 , 0
       0    .035       0       0    .035       0  43.473    .035       0
Bank Sta=0,43.473
XS Rating Curve= 0
Exp/Cntr=.3,.1

Type RM Length L Ch R = 1 ,354.31  ,80,80,80
#Sta/Elev= 16
       0   10.34   3.524   12.11   6.131   11.88   8.417    9.23  11.731    9.15
  13.434    6.66   17.43     6.7  21.638    6.68   25.46    6.72  28.741     6.7
  31.415    6.69  31.761    7.73  35.463    9.47  39.737   12.13  40.865   12.13
  43.473   10.59
#Mann= 3 , 0 , 0
       0    .035       0       0    .035       0  43.473    .035       0
Bank Sta=0,43.473
XS Rating Curve= 0
Exp/Cntr=.3,.1

Type RM Length L Ch R = 1 ,354     ,50.82,50.82,50.82
XS GIS Cut Line= 3
      1614010.73      4849721.96      1613968.87      4849710.81
 1613968.8671027 4849710.8092283
#Sta/Elev= 16
       0   10.35   3.524  12.116   6.131   11.89   8.417   9.237  11.731   9.163
  13.434   6.673   17.43   6.705  21.638   6.693   25.46   6.728  28.741   6.711
  31.415   6.702  31.761   7.738  35.463   9.477  39.737  12.144  40.865  12.139
  43.473  10.598
#Mann= 3 , 0 , 0
       0    .035       0       0    .035       0  43.473    .035       0
Bank Sta=0,43.473
XS Rating Curve= 0
Exp/Cntr=.3,.1

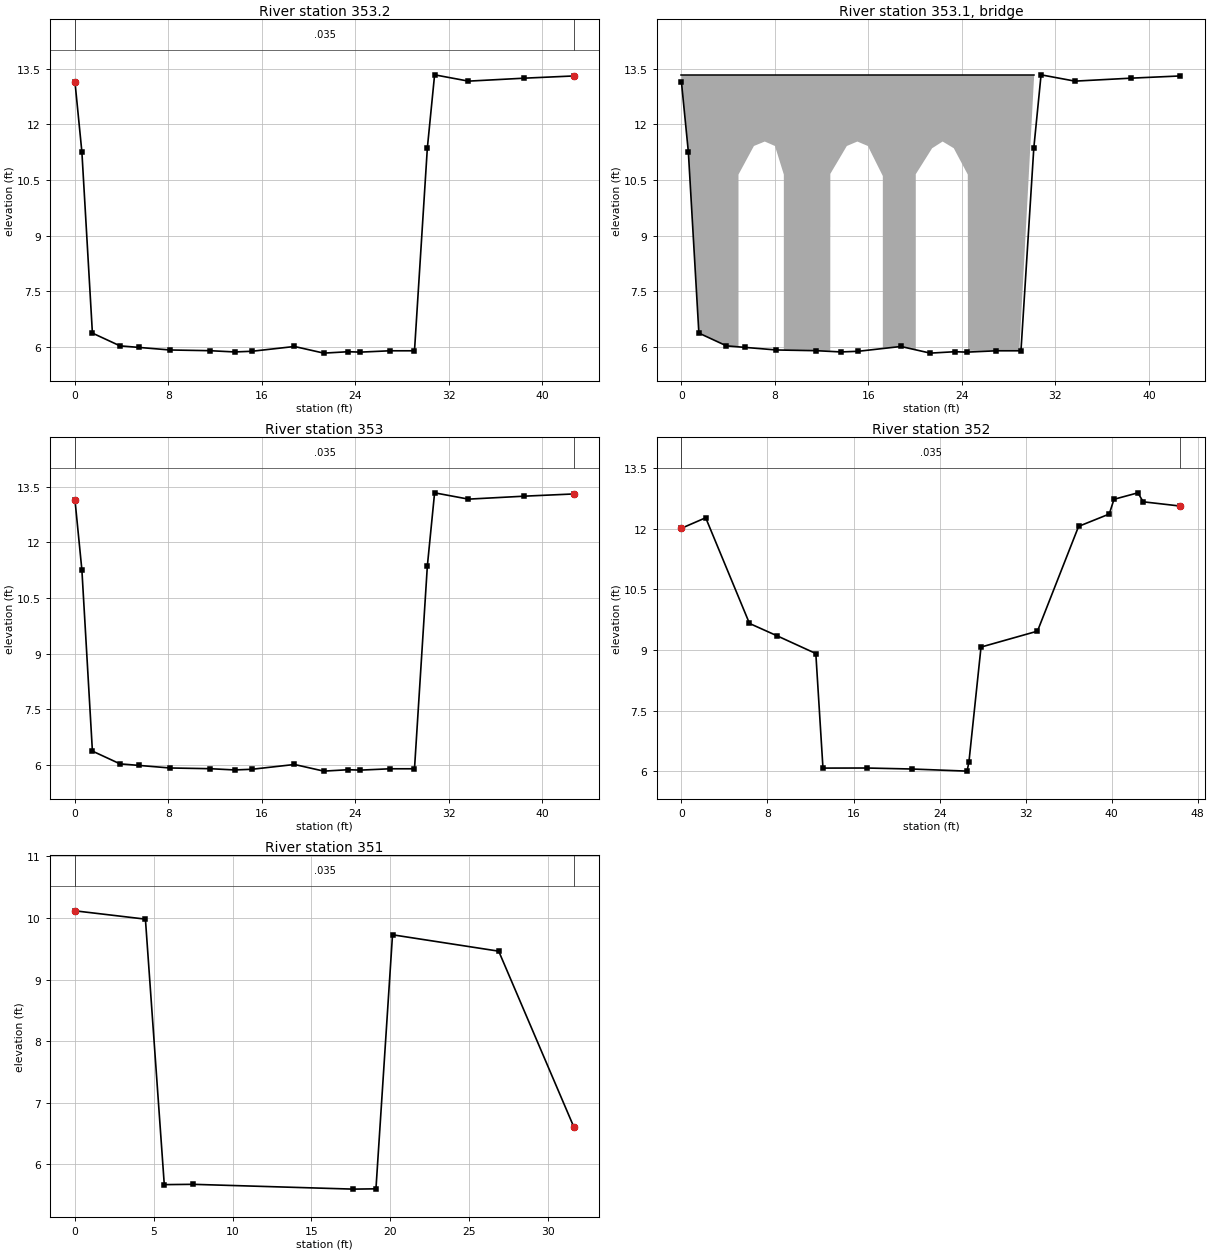
Type RM Length L Ch R = 1 ,353.2   ,8,8,8
XS GIS Cut Line= 3
      1613993.23      4849662.26      1614012.76      4849668.26
 1614013.3220739 4849668.4326801
#Sta/Elev= 20
       0  13.138     .59  11.258    1.49   6.377    3.85   6.033    5.47   5.991
    8.12   5.922   11.51   5.903   13.66   5.869   15.14   5.887   18.78   6.016
   21.29   5.837   23.39   5.875   24.42   5.864   26.94     5.9   29.05     5.9
   30.15  11.368   30.77  13.338   33.67  13.168   38.46  13.248  42.698  13.308
#Mann= 3 , 0 , 0
       0    .035       0       0    .035       0  42.698    .035       0
Bank Sta=0,42.698
XS Rating Curve= 0
Exp/Cntr=.3,.1

Type RM Length L Ch R = 3 ,353.1   ,,,
BEGIN DESCRIPTION:
Ponte di Rigoli
END DESCRIPTION:
Bridge Culvert--1,0,-1,-1, 0
Deck Dist Width WeirC Skew NumUp NumDn MinLoCord MaxHiCord MaxSubmerge Is_Ogee
.5,7,1.44,0, 26, 26, , , .95, 0, 0,0,,
       0     .89  3.2501  4.8798  4.8798  6.1999  7.1299  8.0001    8.76    8.76
   12.73   12.74   14.15 15.0501 15.9499   17.23   17.23   20.05   20.05   21.45
 22.3501 23.3001 24.5001 24.5199   28.91 30.1801
 13.3301 13.3301 13.3301 13.3301 13.3301 13.3301 13.3301 13.3301 13.3301 13.3301
 13.3301 13.3301 13.3301 13.3301 13.3301 13.3301 13.3301 13.3301 13.3301 13.3301
 13.3301 13.3301 13.3301 13.3301 13.3301 13.3301
 11.2499    6.37  6.0299    5.95   10.65 11.4199   11.54 11.4199   10.65     5.9
     5.9 10.6701 11.4199   11.54 11.4199 10.6101  5.9101     5.9 10.6601 11.3599
   11.54 11.3599   10.65     5.9     5.9 13.3301
       0     .89  3.2501  4.8798  4.8798  6.1999  7.1299  8.0001    8.76    8.76
   12.73   12.74   14.15 15.0501 15.9499   17.23   17.23   20.05   20.05   21.45
 22.3501 23.3001 24.5001 24.5199   28.91 30.1801
 13.3301 13.3301 13.3301 13.3301 13.3301 13.3301 13.3301 13.3301 13.3301 13.3301
 13.3301 13.3301 13.3301 13.3301 13.3301 13.3301 13.3301 13.3301 13.3301 13.3301
 13.3301 13.3301 13.3301 13.3301 13.3301 13.3301
 11.2499    6.37  6.0299    5.95   10.65 11.4199   11.54 11.4199   10.65     5.9
     5.9 10.6701 11.4199   11.54 11.4199 10.6101  5.9101     5.9 10.6601 11.3599
   11.54 11.3599   10.65     5.9     5.9 13.3301
BR Coef=-1 , 0 , 0 ,1.25, 0 ,,,.8,-1,2,0,
WSPro=,,,, 1 ,,,, 0 ,,,, 0 ,,,,-1 ,-1 ,-1 , 0 , 0 , 0 , 0 , 0
BC Design=,, 0 ,, 0 ,,,,,,
BC HTab Sub Flow Pts= 40

Type RM Length L Ch R = 1 ,353     ,17.84,17.84,17.84
XS GIS Cut Line= 3
      1613993.23      4849662.26      1614012.76      4849668.26
 1614013.3220739 4849668.4326801
#Sta/Elev= 20
       0  13.138     .59  11.258    1.49   6.377    3.85   6.033    5.47   5.991
    8.12   5.922   11.51   5.903   13.66   5.869   15.14   5.887   18.78   6.016
   21.29   5.837   23.39   5.875   24.42   5.864   26.94     5.9   29.05     5.9
   30.15  11.368   30.77  13.338   33.67  13.168   38.46  13.248  42.698  13.308
#Mann= 3 , 0 , 0
       0    .035       0       0    .035       0  42.698    .035       0
Bank Sta=0,42.698
XS Rating Curve= 0
Exp/Cntr=.3,.1

Type RM Length L Ch R = 1 ,352     ,87.46,87.46,87.46
XS GIS Cut Line= 2
       1613995.2      4849637.01 1614034.9276794 4849648.5972398
#Sta/Elev= 18
       0  12.015   2.253  12.275   6.323    9.66   8.863   9.357  12.493   8.915
  13.157    6.08  17.224   6.082  21.471   6.057  26.555   6.005  26.729   6.232
  27.853   9.075  33.101   9.469  36.926  12.062  39.775  12.367  40.216  12.732
  42.441  12.892  42.928   12.67  46.397  12.564
#Mann= 3 , 0 , 0
       0    .035       0       0    .035       0  46.397    .035       0
Bank Sta=0,46.397
XS Rating Curve= 0
Exp/Cntr=.3,.1

Type RM Length L Ch R = 1 ,351     ,0,0,0
XS GIS Cut Line= 2
      1614058.07      4849570.18 1614034.1823254 4849552.3617346
#Sta/Elev= 9
       0  10.118   4.469   9.983   5.666   5.673   7.495   5.678  17.657     5.6
  19.099   5.605   20.15   9.729  26.889   9.463  31.667   6.603
#Mann= 3 , 0 , 0
       0    .035       0       0    .035       0  31.667    .035       0
Bank Sta=0,31.667
XS Rating Curve= 0
Exp/Cntr=.3,.1

Storage Area=c01             ,1616720.49,4854737.02
Storage Area Surface Line= 8
      1616299.84      4854778.17               .
      1616532.47      4854890.54               .
      1616932.67      4854839.28               .
      1617167.27      4854450.91               .
      1617157.41      4854383.88               .
      1616739.47      4854539.63               .
      1616455.58      4854675.66               .
      1616299.84      4854784.09               .
Storage Area Type= 1
Storage Area Vol Elev= 8
   8.001       0  9.0007   .0093 10.0005   .1394 11.0002   .7897      12  3.6325
 12.9997 11.9938 13.9995 22.0831 14.9992 33.2314

Storage Area=c02             ,1616454.52,4854518.39
Storage Area Surface Line= 13
      1616224.92      4854709.17               .
      1616155.92      4854697.34               .
      1616106.63       4854638.2               .
      1616201.27      4854563.29               .
       1616475.3      4854435.14               .
      1616674.41      4854170.97               .
      1617119.95      4854257.71               .
      1617143.61       4854320.8               .
      1616745.38      4854421.34               .
      1616528.52      4854529.77               .
      1616372.78      4854632.28               .
      1616313.64       4854679.6               .
      1616209.15      4854709.17               .
Storage Area Type= 1
Storage Area Vol Elev= 7
  9.0007       0 10.0005   .0465 11.0002   .5017      12  2.7313 12.9997  8.7329
 13.9995 17.5029 14.9992 27.6851

--- ozz_def.g03 (geometry) ---

Geom Title=studio_ozz_mod2
Version=Version 3.0.1  Mar 2001

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
River Reach=OZZERI          ,tronco_1

Storage Area=c01             ,5304201.08,15927614.9
Storage Area Surface Line= 8
        5302821.      15927749.9               .
      5303584.22     15928118.57               .
      5304897.21     15927950.39               .
       5305666.9     15926676.21               .
      5305634.55      15926456.3               .
      5304263.35     15926967.29               .
      5303331.96     15927413.58               .
        5302821.     15927769.32               .
Storage Area Type= 1
Storage Area Vol Elev= 8
   26.25       0   29.53      .1   32.81     1.5   36.09     8.5   39.37    39.1
   42.65   129.1   45.93 237.701   49.21   357.7

Connection=hc_02_04        ,5305765.6462295,15926031.5608869
Connection Line= 4
 5305924.876327915925950.6197587 5305726.805428815926044.8947128
 5305509.816039415926085.9467595 5305525.754123815926079.9697853
Connection Up SA=c04
Connection Dn SA=c02
Conn Weir Coef=3
Conn Weir Is Ogee= 0
Conn Weir SE= 6
       0   49.18      10   49.18      10   44.26  173.93   44.26  173.93   49.18
  183.93   49.18
Connection Culv=1,.1,,10,.035,1,1,1,1,40,40, 1 ,Culvert #1  , 0 ,
     100     100
Conn Culv Bottom n=.035
Conn HTab HWMax=50